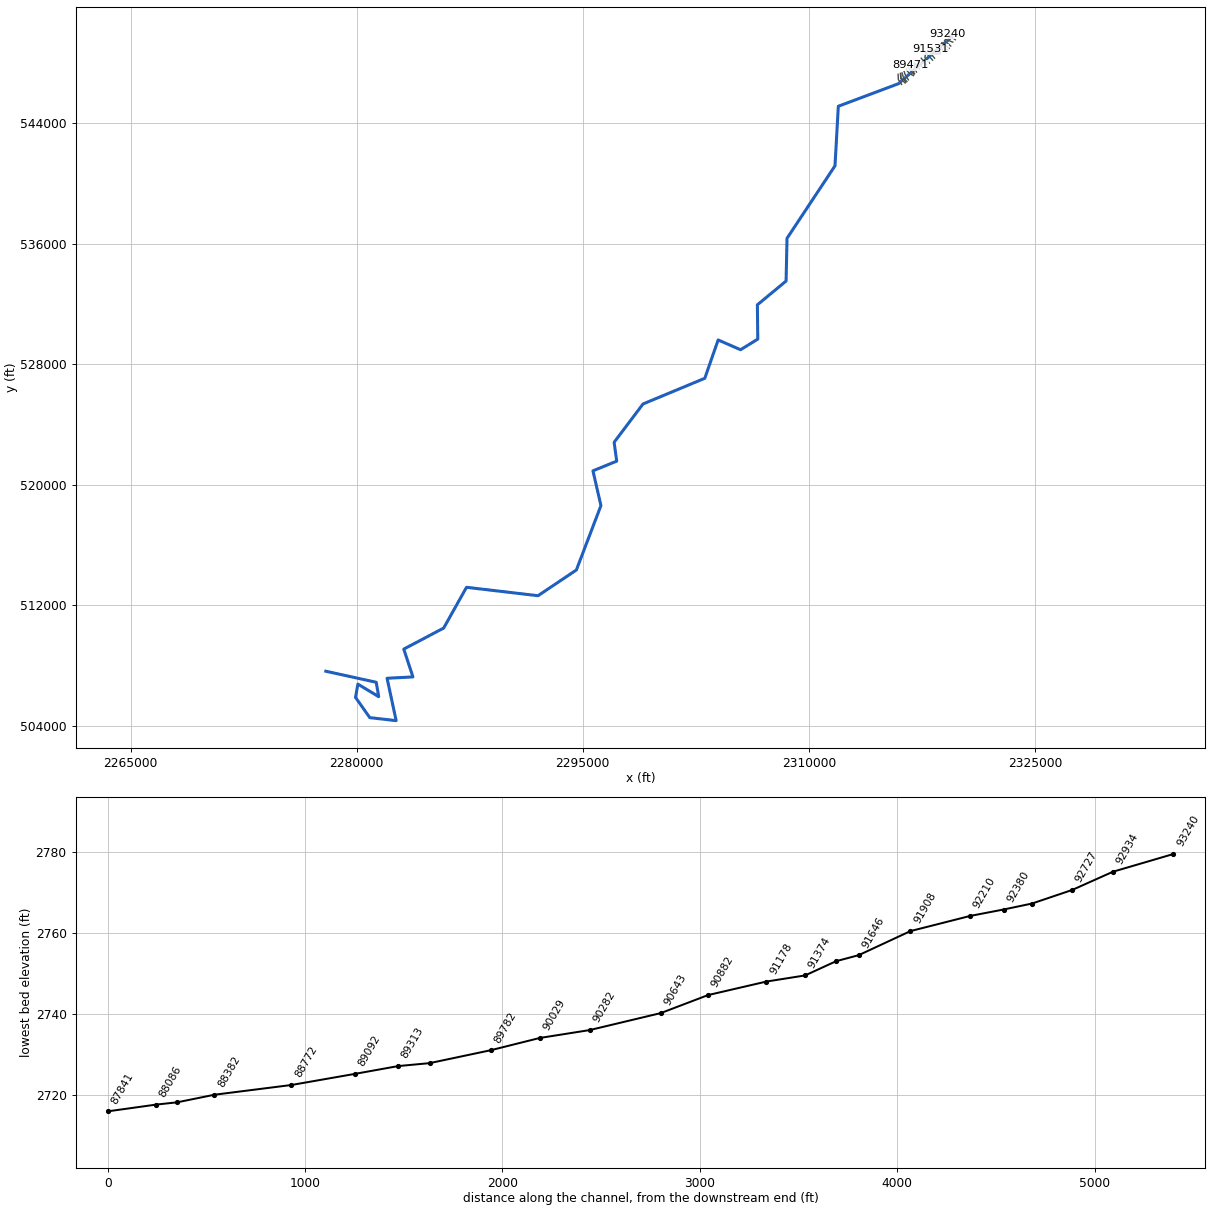
--- DEERCK.prj (project) ---

Proj Title=DEERCK
Current Plan=p01
Default Exp/Contr=0,0
English Units
Geom File=g01
Flow File=f01
Plan File=p01
Background Map Layer=FWY
Background Map Layer=Inundation Boundary (01pct Value_0)
Background Map Layer=Inundation Boundary (01pct Value_0)
Background Map Layer=FWY
BEGIN DESCRIPTION:
----------MODEL BY WOOD PLC 2021----------
Stream Name: Deer Creek
Flood Zone: Detailed between XS 39777 & 31909, and DS extent up to XS 2200; Approximate elsewhere
Pocahontas County, WV
HEC-RAS Version: RAS 6.1
Vertical Datum: NAVD88
Projection: NAD 1983 StatePlane West Virginia S FIPS 4702 (US Feet)
Terrain: 1-meter LIDAR (FEMA Region III 3DEP collected 2016-2018)
Land Use: 2019 NLCD
Hydrologic Method:
WV SIR2010-5033 regression equations
Model Notes:
Alternating A and AE sections. Floodway only developed for AE sections.
END DESCRIPTION:
DSS Export Rating Curves= 0
DSS Export Rating Curve Sorted= 0
DSS Export Volume Flow Curves= 0
DXF OffsetX= 0
DXF OffsetY= 0
DXF ScaleX= 0
DXF ScaleY= 0

--- DEERCK.p01 (plan) ---

Plan Title=Floodplain
Program Version=6.10
Short Identifier=Floodplain
Geom File=g01
Flow File=f01
Subcritical Flow
K Sum by GR= 0
Std Step Tol= 0.01
Critical Tol= 0.01
Num of Std Step Trials= 20
Max Error Tol= 0.3
Flow Tol Ratio= 0.001
Split Flow NTrial= 30
Split Flow Tol= 0.02
Split Flow Ratio= 0.02
Log Output Level= 0
Friction Slope Method= 1
Unsteady Friction Slope Method= 2
Unsteady Bridges Friction Slope Method= 1
Parabolic Critical Depth
Global Vel Dist= 0 , 0 , 0
Global Log Level= 0
CheckData=True
Encroach Param=-1 ,0,0, 2
Encroach River=DEERCK
Encroach Reach=Main
Encroach Node=39635
       1    1180    1551
Encroach Node=39410
       1    1150    1580
Encroach Node=38791
       1     950    1300
Encroach Node=38432
       1    1070    1400
Encroach Node=37975
       1  1219.4    1752
Encroach Node=37705
       1    1224    1604
Encroach Node=37589
       1  1002.2  1512.8
Encroach Node=37507
       1   935.3  1434.8
Encroach Node=37288
       1   909.8  1426.1
Encroach Node=37211
       1   907.4  1419.9
Encroach Node=37164
       1   912.6  1408.5
Encroach Node=36905
       1   904.5    1227
Encroach Node=36797
       1     844    1143
Encroach Node=36350
       1     540    1130
Encroach Node=35850
       1     350     881
Encroach Node=35405
       1     300     714
Encroach Node=35012
       1     384     770
Encroach Node=34799
       1     300     760
Encroach Node=34099
       1     260     730
Encroach Node=33550
       1     240     733
Encroach Node=33007
       1   307.5     683
Encroach Node=32535
       1   358.5     688
Encroach Node=32172
       1   471.9     940
Encroach Node=31909
       1   667.8    1235
Encroach Node=2200
       1     120     240
Encroach Node=1825
       1   209.3     345
Encroach Node=1436
       1   194.5     320
Encroach Node=1250
       1   173.4     320
Encroach Node=1069
       1   281.7     400
Encroach Node=768
       1   465.9     590
Encroach Node=423
       1     520   689.4
Encroach Node=269
       1     665     800
Mapping Interval=1HOUR
Computation Time Step Use Courant=        0
Computation Time Step Use Time Series=    0
Computation Time Step Count To Double=0
Computation Time Step Max Doubling=0
Computation Time Step Max Halving=0
Computation Time Step Residence Courant=0
Run HTab= 0
Run UNet= 0
Run Sediment= 0
Run PostProcess= 0
Run WQNet= 0
Run RASMapper=-1
UNET Theta= 0
UNET Theta Warmup= 0
UNET ZTol= 0
UNET ZSATol= 0
UNET MxIter= 0
UNET Max Iter WO Improvement= 0
UNET MaxInSteps= 0
UNET DtIC= 0
UNET DtMin= 0
UNET MaxCRTS= 0
UNET WFStab= 0
UNET SFStab= 0
UNET WFX= 1
UNET SFX= 1
UNET Gravity=32.174
UNET 1D Methodology=Finite Difference
UNET DSS MLevel= 1
UNET Pardiso=0
UNET DZMax Abort= 0
UNET Use Existing IB Tables= 0
UNET Froude Reduction=False
UNET Froude Limit= 0
UNET Froude Power= 0
UNET D1 Cores= 0
UNET WindReference=Eulerian
UNET WindDragFormulation=Hsu (1988)
UNET D2 Coriolis=0
UNET D2 Cores= 0
UNET D2 Theta= 1
UNET D2 Theta Warmup= 1
UNET D2 Z Tol= 0.01
UNET D2 Volume Tol= 0.01
UNET D2 Max Iterations= 20
UNET D2 Equation= 0
UNET D2 RampUpFraction=0.1
UNET D2 TimeSlices= 1
UNET D2 Turbulence Formulation=Non-Conservative (original)
UNET D2 Eddy Viscosity=0.3
UNET D2 Transverse Eddy Viscosity=0.1
UNET D2 Smagorinsky Mixing=0
UNET D2 BCVolumeCheck=0
UNET D2 Cores=0
UNET D2 SolverType=PARDISO (Direct)
UNET D2 Minimum Iterations= 2147483647
UNET D2 Maximum Iterations= 2147483647
UNET D2 Restart Number= 10
UNET D2 Relaxation Coeff=1.3
UNET D2 SOR Precondition Iterations= 10
UNET D2 ILUT Maximum Fill= 8
UNET D2 ILUT Tolerance=1E-08
UNET D1D2 MaxIter= 0
UNET D1D2 ZTol=0.01
UNET D1D2 QTol=0.1
UNET D1D2 MinQTol=1
Write IC File= 0
Write IC File at Fixed DateTime=0
Write IC File at Sim End=0
Echo Input=False
Echo Parameters=False
Echo Output=False
Write Detailed= 0
HDF Write Warmup=0
HDF Write Time Slices=0
HDF Flush=0
HDF Compression= 1
HDF Chunk Size= 1
HDF Spatial Parts= 1
HDF Use Max Rows=0
HDF Fixed Rows= 1
Calibration Method= 0
Calibration Iterations= 20
Calibration Max Change=0.05
Calibration Tolerance=0.2
Calibration Maximum=1.5
Calibration Minimum=0.5
Calibration Optimization Method= 1
WQ AD Non Conservative
WQ ULTIMATE=-1
WQ Max Comp Step=1HOUR
WQ Output Interval=15MIN
WQ Output Selected Increments= 0
WQ Output face flow=0
WQ Output face velocity=0
WQ Output face area=0
WQ Output face dispersion=0
WQ Output cell volume=0
WQ Output cell surface area=0
WQ Output cell continuity=0
WQ Output cumulative cell continuity=0
WQ Output face conc=0
WQ Output face dconc_dx=0
WQ Output face courant=0
WQ Output face peclet=0
WQ Output face adv mass=0
WQ Output face disp mass=0
WQ Output cell mass=0
WQ Output cell source sink temp=0
WQ Output nsm pathways=0
WQ Output nsm derived pathways=0
WQ Create Restart=0
WQ Fixed Restart=0
WQ System Summary=0
WQ Write To DSS=0
Sorting and Armoring Iterations= 10
XS Update Threshold= 0.02
Bed Roughness Predictor= 0
Hydraulics Update Threshold= 0.02
Energy Slope Method= 1
Volume Change Method= 1
Sediment Retention Method= 0
Sediment TS Multiplier= 1
Warm Up Method= 0
XS Weighting Method= 0
Number of US Weighted Cross Sections= 1
Number of DS Weighted Cross Sections= 1
Upstream XS Weight=0
Main XS Weight=1
Downstream XS Weight=0
Number of DS XS's Weighted with US Boundary= 1
Upstream Boundary Weight= 1
Weight of XSs Associated with US Boundary= 0
Number of US XS's Weighted with DS Boundary= 1
Downstream Boundary Weight= 0.5
Weight of XSs Associated with DS Boundary= 0.5
Percentile Method= 0
Sediment Output Level= 3
Mass or Volume Output= 0
Output Increment Type= 1
Profile and TS Output Increment= 1
Transport Output Increment 1
XS Output Flag= 0
XS Output Increment= 10
Read HDF5 Sediment Hotstart= 0
Sediment Hotstart Type= 0
Write Gradation File= 0
Read Gradation Hotstart= 0
Write HDF5 File= 1
Write Binary Output= 1
Write DSS Sediment File= 0
DSS Sediment Output Type= 1
SV Curve= 0
Specific Gage Flag= 0
Subcell Erosion Methods= 0
Subcell Deposition Methods= 0
Advection Scheme= 1
Matrix Solver= 0
Implicit Weighting Factor= 1
Maximum Outer Loop Convergence Iterations= 5
Convergence Maximum Absolute= 0.001
Convergence RMSE= 0.0001
Grain Fractions Max Abs Error= 0.001
Max Subgrid Regions= 1
Max Subgrid Length Scale= 3.402823E+38
Initial Layer Thickness= 3.402823E+38
Min Layer Thickness= 3.402823E+38
Max Layer Thickness= 3.402823E+38
Number of Layers= 5

--- DEERCK.f01 (steady flow) ---

Flow Title=Flow
Program Version=6.10
Number of Profiles= 7
Profile Names=01pct,FW,10pct,04pct,02pct,0_2pct,01plus
River Rch & RM=DEERCK,Main            ,93240
     837     837     449     593     711    1160    1240
River Rch & RM=DEERCK,Main            ,90643
     943     943     508     669     802    1310    1390
River Rch & RM=DEERCK,Main            ,86930
    1050    1050     565     744     890    1440    1550
River Rch & RM=DEERCK,Main            ,84449
    1230    1230     672     881    1050    1700    1830
River Rch & RM=DEERCK,Main            ,81510
    1370    1370     748     978    1170    1880    2020
River Rch & RM=DEERCK,Main            ,74328
    2350    2350    1310    1700    2010    3190    3470
River Rch & RM=DEERCK,Main            ,67922
    3130    3130    1770    2280    2690    4240    4630
River Rch & RM=DEERCK,Main            ,62450
    3610    3610    2050    2630    3100    4870    5330
River Rch & RM=DEERCK,Main            ,60719
    4120    4120    2350    3010    3550    5550    6090
River Rch & RM=DEERCK,Main            ,54335
    4610    4610    2640    3370    3970    6190    6810
River Rch & RM=DEERCK,Main            ,35850
    7920    7920    4630    5860    6860   10500   11700
River Rch & RM=DEERCK,Main            ,29239
    8510    8510    4990    6310    7370   11300   12600
Boundary for River Rch & Prof#=DEERCK,Main            , 1
Up Type= 0
Dn Type= 3
Dn Slope=0.005382
Boundary for River Rch & Prof#=DEERCK,Main            , 2
Up Type= 0
Dn Type= 3
Dn Slope=0.005382
Boundary for River Rch & Prof#=DEERCK,Main            , 3
Up Type= 0
Dn Type= 3
Dn Slope=0.005382
Boundary for River Rch & Prof#=DEERCK,Main            , 4
Up Type= 0
Dn Type= 3
Dn Slope=0.005382
Boundary for River Rch & Prof#=DEERCK,Main            , 5
Up Type= 0
Dn Type= 3
Dn Slope=0.005382
Boundary for River Rch & Prof#=DEERCK,Main            , 6
Up Type= 0
Dn Type= 3
Dn Slope=0.005382
DSS Import GetInterval= 0
DSS Import GetPeak= 0
DSS Import FillOption= 0

--- DEERCK.g01 (geometry) ---

Geom Title=Geometry
Program Version=6.10

River Reach=DEERCK          ,Main
Reach XY= 30
2319466.81799763549726.1269875622315945.77385864546616.165031642
2311951.05284546545115.334043816 2311729.3636563541163.442997471
 2308547.1278948536355.8738724742308485.37998681533520.551131055
 2306581.3641098 531945.422063472306607.64292863529668.193022147
2305463.82795906528964.2341282222303979.45494355529614.346016973
2303092.99411805527071.4626513122298995.34516114 525366.32892248
2297078.01697481522824.9888608162297249.35587098521573.108162478
 2295674.7756868520932.448026478 2296203.0659688518623.373904482
2294574.06364939514353.5012106452292029.88107371512647.334019303
2287285.96339622513204.7623663992285771.31485072510501.481355637
2283125.03011705509105.7361156492283731.95180348507260.907784313
2282015.75083956507170.958161056 2282620.2663628504360.039242223
2280870.49033481504558.5463911442279924.35410371505902.802888975
 2280080.3915213 506783.457623722281460.88515139505948.890067145
2281297.22931072506904.8687982262277955.55784447507637.069105476

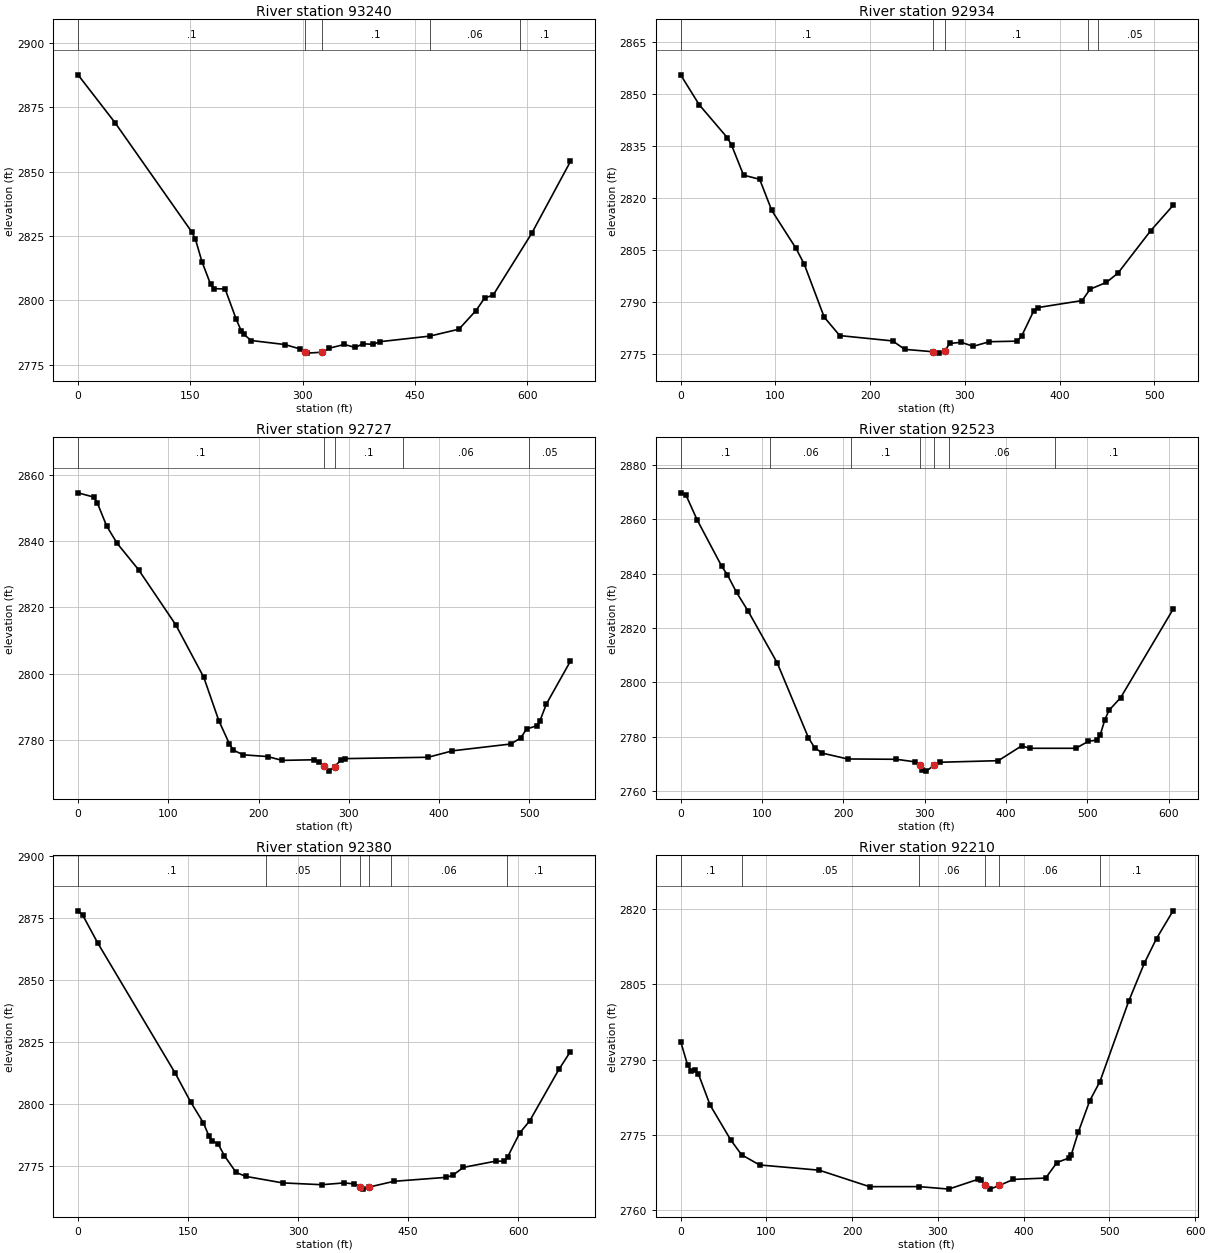
Type RM Length L Ch R = 1 ,93240   ,306.2,306.2,306.2
XS GIS Cut Line= 2
2319714.28323125549527.8235235412319185.10867076549918.478860839
#Sta/Elev= 30
       0 2887.56    49.4 2868.99   151.8 2826.63   156.9 2823.68   165.5 2815.06
     177 2806.32   181.6 2804.58   196.5 2804.42   211.4 2792.61   217.8 2788.31
   221.4 2786.84   231.3 2784.44   276.1 2782.88     296 2781.21   302.8 2779.79
   305.7 2779.54   326.5 2779.89   335.7 2781.45   355.6  2782.9   370.5 2781.74
   380.5 2783.18   394.3 2782.94   402.9 2783.97     470 2786.15   508.8 2788.83
   531.6 2796.06   543.1 2800.91   554.5 2802.06     606 2826.02   657.8 2853.95
#Mann= 5 ,-1,0
       0      .1       0   302.8    .045       0   326.5      .1       0
     470     .06       0     590      .1       0
Bank Sta=302.8,326.5
XS Rating Curve= 0 ,0
Exp/Cntr(USF)=0,0
Exp/Cntr=0.3,0.1

Type RM Length L Ch R = 1 ,92934   ,216.8,207,196.6
XS GIS Cut Line= 2
2319546.65464933549372.7596674662319057.79073919549549.254947345
#Sta/Elev= 30
       0 2855.47    19.6 2846.84    49.4 2837.28    53.7 2835.22    66.4 2826.52
    83.4 2825.33    96.2 2816.32   121.7 2805.41   130.4 2800.86   151.5 2785.55
   167.9 2780.22   223.8 2778.68   236.5 2776.25   266.3 2775.56   272.2 2775.16
   279.1 2775.91   283.9 2777.95   296.1 2778.28   308.8 2777.13   325.8 2778.45
   355.3 2778.62   359.9  2780.1   372.6 2787.33   376.9  2788.3   423.7 2790.33
   432.2 2793.62   449.4 2795.58   461.6 2798.27   495.9 2810.43   519.7 2817.79
#Mann= 5 ,-1,0
       0      .1       0   266.3    .045       0   279.1      .1       0
     430     .06       0     440     .05       0
Bank Sta=266.3,279.1
XS Rating Curve= 0 ,0
Exp/Cntr(USF)=0,0
Exp/Cntr=0.3,0.1

Type RM Length L Ch R = 1 ,92727   ,201.8,203.9,205.8
XS GIS Cut Line= 2
2319407.97978657549112.219016216 2319003.1612478549477.816381679
#Sta/Elev= 30
       0 2854.52    17.5 2853.23    21.3 2851.51    31.7 2844.53    43.2 2839.34
    67.1 2831.32   108.2 2814.76   139.3 2798.91     156 2785.82   167.6  2778.9
   172.2 2776.93     183 2775.56   209.9 2775.03   226.1 2773.88   261.1 2774.06
   266.8 2773.49   272.4 2772.04   278.1 2770.64   284.22771.945   290.8  2773.9
   296.2 2774.41   387.8 2774.82   414.8 2776.76   479.2 2778.81   490.2 2780.58
   496.8 2783.31   508.7 2784.37   511.8 2785.89   518.8 2790.86   545.5  2803.8
#Mann= 5 ,-1,0
       0      .1       0   272.4    .045       0   284.2      .1       0
     360     .06       0     500     .05       0
Bank Sta=272.4,284.2
XS Rating Curve= 0 ,0
Exp/Cntr(USF)=0,0
Exp/Cntr=0.3,0.1

Type RM Length L Ch R = 1 ,92523   ,157.9,143.5,126.8
XS GIS Cut Line= 2
2319301.29503812548961.7723336762318826.43868987549337.174992466
#Sta/Elev= 30
       0 2869.76     6.5 2868.98    20.3 2859.78    50.6 2842.65    57.5 2839.55
    68.7  2833.1      83 2826.18   118.7 2807.15     157 2779.64   164.6 2775.94
   174.1 2773.91   205.2 2771.76   265.2 2771.64     288  2770.7   293.7 2769.36
   297.2 2767.82   302.2 2767.28   311.52769.459   319.3 2770.55   390.5 2771.13
     419 2776.55   429.7 2775.69   485.8 2775.69   501.1 2778.26   511.3 2778.71
   515.8 2780.66   521.5 2786.27   526.6 2789.69   540.8  2794.3   605.3 2826.88
#Mann= 7 ,-1,0
       0      .1       0     110     .06       0     210      .1       0
   293.7    .045       0   311.5      .1       0     330     .06       0
     460      .1       0
Bank Sta=293.7,311.5
XS Rating Curve= 0 ,0
Exp/Cntr(USF)=0,0
Minor Loss Coefficient=0
Exp/Cntr=0.3,0.1

Type RM Length L Ch R = 1 ,92380   ,169.8,169.3,168.5
XS GIS Cut Line= 4
2319238.48828764548853.079121156 2319003.1612478  548927.3191992
2318912.11209548549190.6613628292318795.84933175549278.909002768
#Sta/Elev= 30
       0 2877.91     6.6 2876.04    26.9 2864.93   132.7 2812.41   153.4 2800.99
   170.9 2792.51   178.6 2787.12   182.8 2785.35   191.2 2783.89   199.6 2779.25
   215.5 2772.53   228.9 2770.93   278.9 2768.32   332.3 2767.59     363 2768.32
   376.4 2767.91   384.2 2766.74   388.4 2765.81   397.32766.666   430.7 2768.96
   502.2 2770.56   511.1 2771.43   525.4 2774.57   570.5 2777.14   581.4 2776.97
   585.6 2778.72   602.3 2788.46   615.7 2793.25   655.6 2814.01   671.4 2821.24
#Mann= 7 ,-1,0
       0      .1       0  256.76     .05       0  356.76      .1       0
   384.2    .045       0   397.3      .1       0  426.76     .06       0
   585.4      .1       0
Bank Sta=384.2,397.3
XS Rating Curve= 0 ,0
Exp/Cntr(USF)=0,0
Exp/Cntr=0.3,0.1

Type RM Length L Ch R = 1 ,92210   ,288.4,302.6,313.1
XS GIS Cut Line= 3
2319007.94331563548769.7155826242318857.91673322548817.173684365
2318731.41454703549214.474218051
#Sta/Elev= 30
       0  2793.6     8.1 2788.94    12.3 2787.82    16.5 2787.86    20.7 2787.15
    34.4 2780.94    58.5 2773.99    71.1 2771.05    92.1 2769.03   161.6 2767.99
   220.3 2764.71   277.9 2764.72   312.7 2764.23   346.6 2766.16   350.5 2766.07
   355.2 2765.02   360.9 2764.22   371.62764.948   388.2 2766.16   425.7 2766.42
   438.9 2769.52   453.1 2770.43   455.4 2770.95   463.8 2775.57   477.1 2781.81
     489 2785.63   522.6 2801.65   540.8  2809.2     555 2814.11   574.3 2819.62
#Mann= 6 ,-1,0
       0      .1       0    71.1     .05       0   277.9     .06       0
   355.2    .045       0   371.6     .06       0     489      .1       0
Bank Sta=355.2,371.6
XS Rating Curve= 0 ,0
Exp/Cntr(USF)=0,0
Exp/Cntr=0.3,0.1

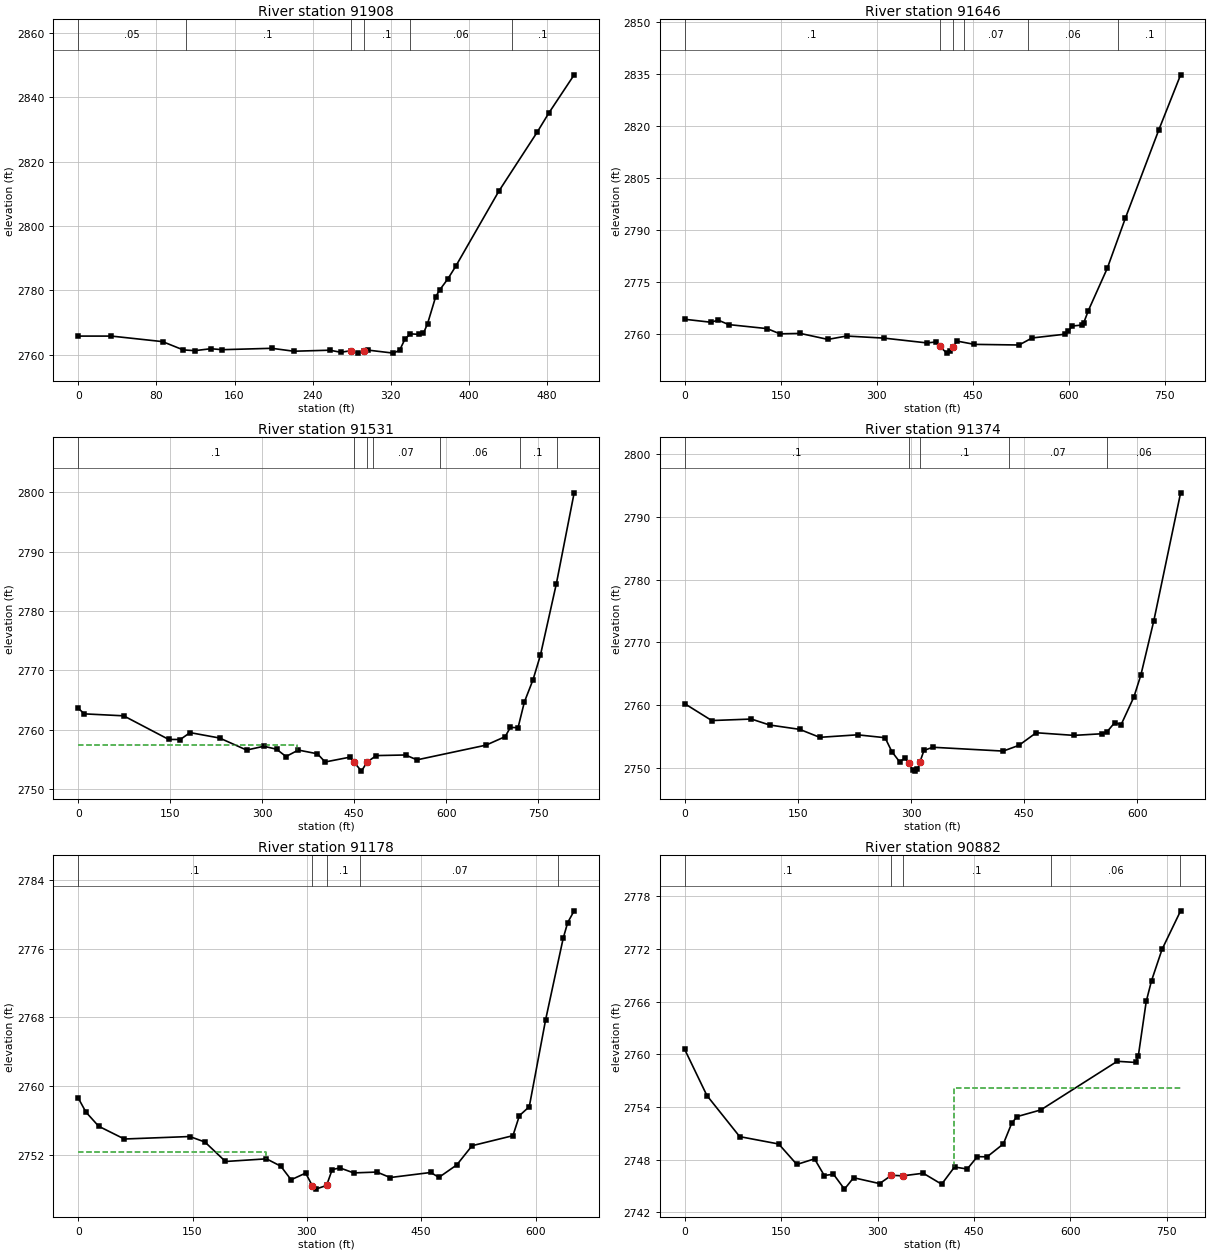
Type RM Length L Ch R = 1 ,91908   ,261.7,262,261.3
XS GIS Cut Line= 3
2318721.60925371548690.5914031732318484.88145768548939.926004906
2318442.85877199549098.211454321
#Sta/Elev= 30
       0 2765.77      34 2765.77    86.3 2764.05   107.5 2761.47   119.4 2761.24
   135.7 2761.84   147.3 2761.54   198.1 2761.97   220.7 2761.06   257.5 2761.38
   268.8 2760.73     2792761.225   286.7 2760.66   292.6  2761.2   297.1 2761.39
   322.6 2760.47     329 2761.38   334.5 2764.88     340 2766.46   349.2  2766.3
   353.4 2766.71   357.5 2769.57   365.8 2777.94   369.9 2780.08   378.4 2783.59
   386.5 2787.54   430.4 2810.78   469.7 2829.16   481.7 2835.15   507.6 2847.02
#Mann= 6 ,-1,0
       0     .05       0     110      .1       0     279    .045       0
   292.6      .1       0     340     .06       0  443.81      .1       0
Bank Sta=279,292.6
XS Rating Curve= 0 ,0
Exp/Cntr(USF)=0,0
Exp/Cntr=0.3,0.1

Type RM Length L Ch R = 1 ,91646   ,115.3,114.7,112.6
XS GIS Cut Line= 4
2318708.74689166548624.7558622652318413.44289201548637.362667971
2318196.32568264548874.0904639992318178.11585217549030.975157224
#Sta/Elev= 30
       0 2764.27    40.6 2763.42    52.6 2764.01    68.6 2762.74   128.7 2761.58
   148.7 2760.08   180.7 2760.19   223.7 2758.47   252.8 2759.44   311.6 2758.84
   378.4 2757.46   392.1 2757.72   398.4 2756.43   409.6 2754.52   414.7 2755.06
   418.92756.334   425.6 2757.98   452.7 2757.04   522.3 2756.86   542.6 2758.88
   593.6 2759.96   599.3 2760.75   604.9 2762.31   619.9 2762.59   623.3 2763.22
   630.5 2766.75   660.2 2778.98   688.4 2793.38   740.7 2818.83   774.7 2834.65
#Mann= 6 ,-1,0
       0      .1       0   398.4    .045       0   418.9      .1       0
  435.57     .07       0  535.57     .06       0  676.79      .1       0
Bank Sta=398.4,418.9
XS Rating Curve= 0 ,0
Exp/Cntr(USF)=0,0
Exp/Cntr=0.3,0.1

Type RM Length L Ch R = 1 ,91531   ,157.2,157.1,157
XS GIS Cut Line= 3
2318690.11997848548592.9567369942318321.11219298548566.599038029
2318039.96340402 548903.39185813
#Sta/Elev= 30
       0 2763.62      10 2762.67    74.1 2762.34   147.6 2758.36   166.4 2758.35
   182.4 2759.51   230.5  2758.6   274.6 2756.57   302.7 2757.21   323.5 2756.71
   338.8 2755.48   358.9 2756.57   390.1 2755.94   402.6 2754.56   443.4 2755.38
   449.62754.547   461.9 2753.02   470.9 2754.53     486 2755.64   533.7 2755.74
   552.4 2754.92     665  2757.4   696.2 2758.83   704.7 2760.39   717.2 2760.34
   727.6 2764.69   741.6 2768.41   753.7 2772.56   779.7 2784.61   808.7 2799.92
#Mann= 7 ,-1,0
       0      .1       0   449.6    .045       0   470.9      .1       0
  479.95     .07       0  589.95     .06       0  719.95      .1       0
  779.95     .06       0
#XS Ineff= 2 , 0
          355.95  2757.4
Permanent Ineff=
       F       F
Bank Sta=449.6,470.9
XS Rating Curve= 0 ,0
Exp/Cntr(USF)=0,0
Exp/Cntr=0.3,0.1

Type RM Length L Ch R = 1 ,91374   ,194.6,195.6,196.6
XS GIS Cut Line= 2
 2318335.0005454548305.3834510562317913.37293236548809.655679281
#Sta/Elev= 30
       0 2760.24    35.9 2757.55    88.4 2757.79   112.6 2756.84   152.4 2756.15
     179 2754.88   229.1 2755.28   265.6 2754.82   274.5 2752.62     285 2750.96
   291.7 2751.57   296.9 2750.87   302.1 2749.66   305.7  2749.5   308.5 2749.76
   311.62750.875   317.1 2752.79   328.7  2753.3   422.2 2752.69   442.9  2753.6
   465.9 2755.61   515.8 2755.19   553.2 2755.45   559.4 2755.71   569.8  2757.2
   578.5 2756.91   595.4 2761.31   604.6 2764.79   621.8 2773.45   657.3  2793.8
#Mann= 5 ,-1,0
       0      .1       0   296.9    .045       0   311.6      .1       0
     430     .07       0     560     .06       0
Bank Sta=296.9,311.6
XS Rating Curve= 0 ,0
Exp/Cntr(USF)=0,0
Exp/Cntr=0.3,0.1

Type RM Length L Ch R = 1 ,91178   ,297.2,296.2,292.3
XS GIS Cut Line= 2
2318206.13097596548173.7123692422317770.49580103548656.973254624
#Sta/Elev= 30
       0 2758.61    10.1 2756.97    26.8 2755.32    60.5 2753.83   146.3 2754.12
   166.2 2753.48   193.2 2751.21     247 2751.52   265.8 2750.66   279.3 2749.08
   298.4 2749.86   306.9 2748.41   311.6 2747.99   325.8 2748.42   333.2 2750.27
   343.4 2750.46   361.4 2749.88   391.9 2749.98   409.2 2749.34   462.4 2749.93
   473.2 2749.36   496.6 2750.81   516.7 2753.05   570.3 2754.22   578.8 2756.56
   591.7 2757.59   613.2 2767.74   636.2 2777.21   642.1 2779.05   650.6 2780.42
#Mann= 5 ,-1,0
       0      .1       0   306.9    .045       0   325.8      .1       0
     370     .07       0     630     .06       0
#XS Ineff= 2 , 0
          246.05 2752.35
Permanent Ineff=
       F       F
Bank Sta=306.9,325.8
XS Rating Curve= 0 ,0
Exp/Cntr(USF)=0,0
Exp/Cntr=0.3,0.1

Type RM Length L Ch R = 1 ,90882   ,238.9,239,238.6
XS GIS Cut Line= 3
2317997.41830373 547977.606502712317690.65269822548372.619748153
2317750.88521437548637.362667971
#Sta/Elev= 30
       0 2760.56    34.6  2755.3    85.6 2750.62   146.3 2749.78   174.5 2747.45
     202 2748.09   217.2 2746.19   231.5 2746.34   248.6 2744.64   262.8 2745.94
   303.3 2745.27   321.6 2746.21   339.8 2746.16   371.2 2746.45   399.8  2745.2
   419.8 2747.16   439.6 2746.93   455.3 2748.34   470.5 2748.32   495.8 2749.79
   508.9 2752.16   517.1  2752.9     554 2753.66     673  2759.2   701.7 2759.07
   705.8 2759.82   718.1 2766.02   726.3 2768.37   742.7 2771.95   771.6 2776.34
#Mann= 5 ,-1,0
       0      .1       0   321.6    .045       0   339.8      .1       0
  570.14     .06       0  770.14      .1       0
#XS Ineff= 2 , 0
                          419.37         2756.21
Permanent Ineff=
       F       F
Bank Sta=321.6,339.8
XS Rating Curve= 0 ,0
Exp/Cntr(USF)=0,0
Exp/Cntr=0.3,0.1

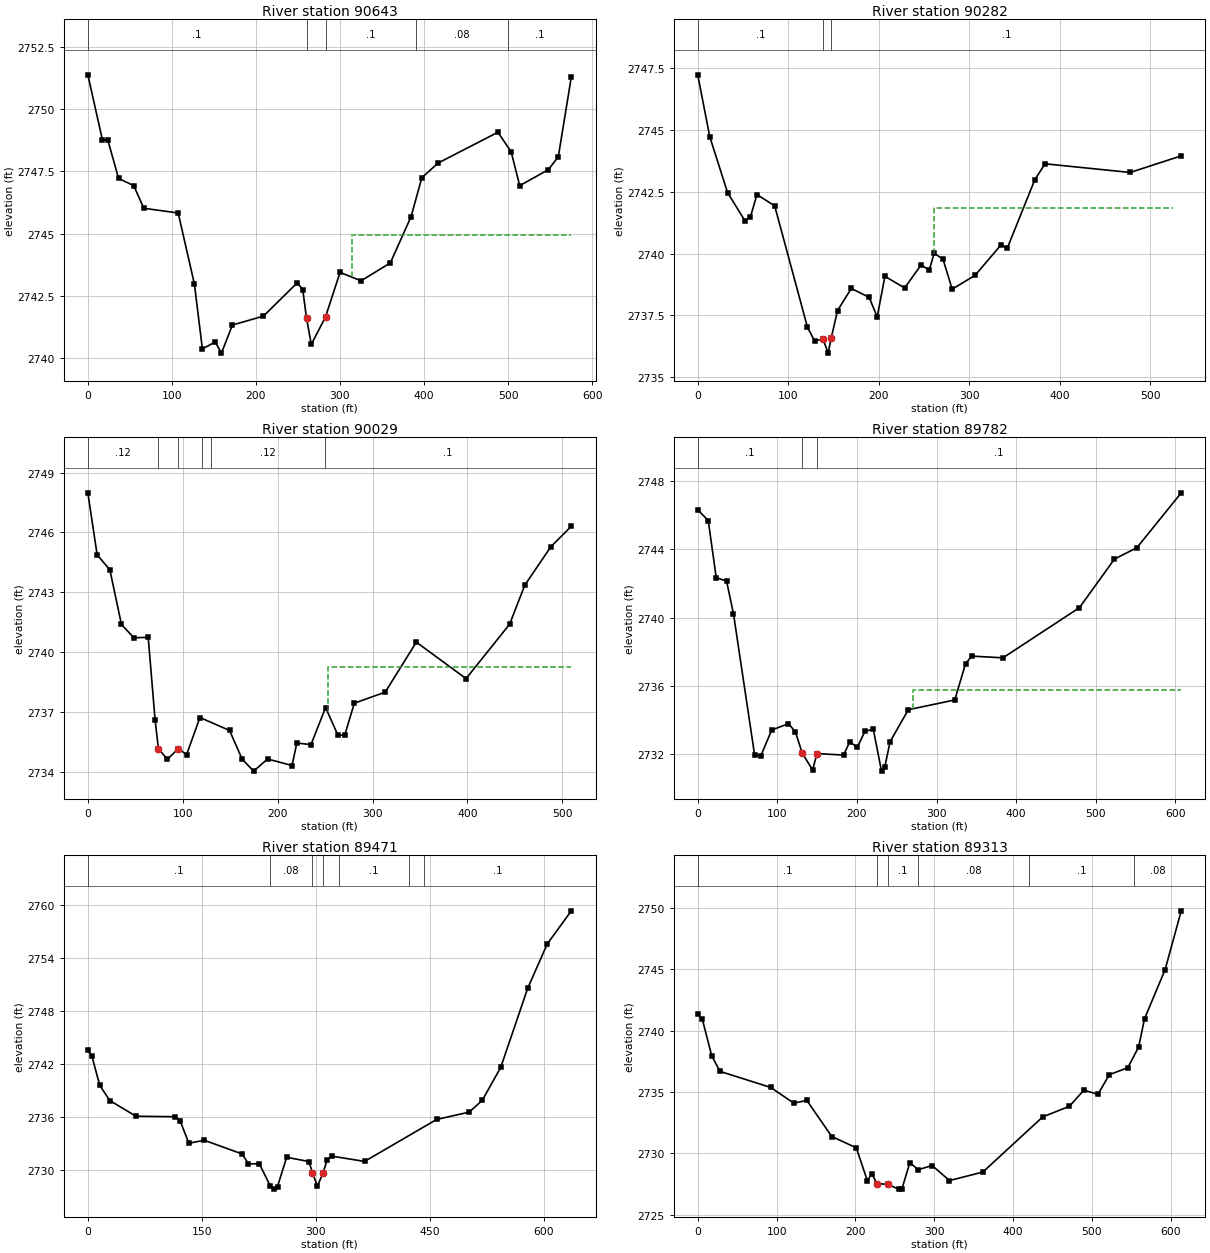
Type RM Length L Ch R = 1 ,90643   ,357.1,361,361.6
XS GIS Cut Line= 2
2317806.91546195547854.3399580332317449.72263363548305.383451056
#Sta/Elev= 30
       0 2751.39    17.3 2748.78    23.9 2748.75    36.6 2747.22    54.6 2746.93
    66.6 2746.02   107.5 2745.83   126.8 2742.97   136.3 2740.36   151.6 2740.64
     159 2740.19     172 2741.32     209 2741.68   249.2 2743.02   255.7 2742.75
   260.2  2741.6   265.9 2740.54   282.82741.646   300.1 2743.44   325.1  2743.1
   359.9 2743.82   384.6 2745.68   397.4 2747.25   416.8 2747.84     488 2749.08
   503.7 2748.29   513.9 2746.93   547.8 2747.57   559.8 2748.09   575.3 2751.31
#Mann= 5 ,-1,0
       0      .1       0   260.2    .045       0   282.8      .1       0
     390     .08       0     500      .1       0
#XS Ineff= 2 , 0
                          314.74         2744.94
Permanent Ineff=
       F       F
Bank Sta=260.2,282.8
XS Rating Curve= 0 ,0
Exp/Cntr(USF)=0,0
Exp/Cntr=0.3,0.1

Type RM Length L Ch R = 1 ,90282   ,252.6,252.7,251.8
XS GIS Cut Line= 2
2317556.26408066547679.1772895922317228.85791409548101.041000647
#Sta/Elev= 30
       0 2747.21    13.2 2744.72    32.9 2742.46    52.3 2741.31    58.2 2741.48
    65.4 2742.38      85 2741.92   121.2 2737.02   129.1 2736.47   138.3 2736.55
     144 2735.98  147.48  2736.6   154.4  2737.7   169.6 2738.59   189.3 2738.23
   198.2 2737.44   206.7 2739.08   228.5 2738.61   246.7 2739.54   255.7 2739.33
   261.1 2740.01   270.9 2739.77     281 2738.56   306.3 2739.12     335 2740.35
   341.8 2740.21   372.2 2742.97   383.5 2743.62   477.6 2743.27     534 2743.94
#Mann= 3 ,-1,0
       0      .1       0   138.3    .045       0  147.48      .1       0
#XS Ineff= 1 ,-1
   260.9   525.3 2741.84
Permanent Ineff=
       F
Bank Sta=138.3,147.48
XS Rating Curve= 0 ,0
Exp/Cntr(USF)=0,0
Exp/Cntr=0.3,0.1

Type RM Length L Ch R = 1 ,90029   ,254.9,247.3,238.8
XS GIS Cut Line= 2
2317347.46743179547558.7804020452317036.49955772547962.198184625
#Sta/Elev= 30
       0 2747.99     9.8 2744.88    23.2 2744.13    35.4 2741.39    48.5 2740.72
    63.6 2740.74    70.9 2736.58   74.33 2735.16    83.8 2734.62    95.3 2735.16
     104 2734.85   118.1 2736.72   149.3 2736.07   162.6 2734.63   174.7 2734.03
   189.4 2734.64   215.1 2734.31   220.2 2735.44   235.1 2735.36   250.5 2737.22
   263.6 2735.82   270.7 2735.84   280.8 2737.44   313.3 2737.99   346.1  2740.5
   398.5 2738.67   444.4  2741.4   460.4 2743.36   487.9 2745.29   509.4 2746.31
#Mann= 6 ,-1,0
       0     .12       0   74.33    .045       0    95.3     .12       0
     120      .1       0     130     .12       0     250      .1       0
#XS Ineff= 2 , 0
                          252.63         2739.26
Permanent Ineff=
       F       F
Bank Sta=74.33,95.3
XS Rating Curve= 0 ,0
Exp/Cntr(USF)=0,0
Exp/Cntr=0.3,0.1

Type RM Length L Ch R = 1 ,89782   ,325.1,311.1,303.6
XS GIS Cut Line= 3
2317135.95324718547383.6858783562317004.28216536547704.459045755
2316993.07611584547964.999697004
#Sta/Elev= 30
       0 2746.33    13.2 2745.69    23.2 2742.35    36.2 2742.15    44.9 2740.23
    71.5 2731.94    79.4 2731.92    92.9 2733.42     114 2733.79   122.7 2733.31
   131.3 2732.06   144.3 2731.08   149.8 2732.04   183.2 2731.95     191 2732.73
   200.5  2732.4   210.1 2733.35   220.6 2733.46   230.9 2731.01   235.1 2731.28
   241.7 2732.74   264.6 2734.61   322.9 2735.18   336.5 2737.31   344.3 2737.75
   383.5 2737.65   479.6 2740.59   523.6 2743.44   551.7  2744.1   607.5 2747.32
#Mann= 3 ,-1,0
       0      .1       0   131.3    .045       0   149.8      .1       0
#XS Ineff= 2 , 0
                          270.85         2735.74
Permanent Ineff=
       F       F
Bank Sta=131.3,149.8
XS Rating Curve= 0 ,0
Exp/Cntr(USF)=0,0
Exp/Cntr=0.3,0.1

Type RM Length L Ch R = 1 ,89471   ,121.3,158.5,160.7
XS GIS Cut Line= 3
2317007.08367774547280.0299203322316781.56193123547626.016699142
2316701.71882843547834.729371379
#Sta/Elev= 30
       0 2743.56     5.3 2742.88    15.7 2739.56    28.9 2737.84    63.4 2736.06
   115.2 2736.01   121.4 2735.57     133    2733   153.2 2733.34   203.1 2731.79
   211.5 2730.67   225.8 2730.67     240  2728.2   244.9  2727.8   249.7 2728.09
   261.7 2731.41     291 2730.93   295.7 2729.67   302.2 2728.12  309.81 2729.68
   315.1 2731.14   321.3 2731.54   364.3 2730.94   459.2  2735.7     502 2736.53
   519.2 2737.86   543.5 2741.59   579.1 2750.58   604.8 2755.59   636.5 2759.35
#Mann= 7 ,-1,0
       0      .1       0     240     .08       0   295.7    .045       0
  309.81     .08       0     330      .1       0     423     .08       0
     443      .1       0
Bank Sta=295.7,309.81
XS Rating Curve= 0 ,0
Exp/Cntr(USF)=0,0
Exp/Cntr=0.3,0.1

Type RM Length L Ch R = 1 ,89313   ,219.8,220.5,222.1
XS GIS Cut Line= 3
2316967.49562818547232.2374396722316664.47110986547555.463592542
2316587.91754734547707.507473662
#Sta/Elev= 30
       0 2741.32     5.8 2740.93    17.7 2737.95    28.2 2736.68    92.6 2735.37
   121.8 2734.09   138.4 2734.31     170 2731.37   201.1 2730.45   215.1 2727.78
   220.9 2728.34   227.1 2727.53   240.7 2727.47   254.9 2727.08     259  2727.1
     269 2729.23   279.7 2728.67   297.4    2729   319.3 2727.78   361.6 2728.47
   437.6 2732.97   471.4 2733.83   489.8 2735.15   507.7 2734.81     522 2736.41
   545.5 2736.98   559.3 2738.67   566.7 2740.97   592.8 2744.97   613.3 2749.77
#Mann= 6 ,-1,0
       0      .1       0   227.1    .045       0   240.7      .1       0
     280     .08       0     420      .1       0  553.06     .08       0
Bank Sta=227.1,240.7
XS Rating Curve= 0 ,0
Exp/Cntr(USF)=0,0
Exp/Cntr=0.3,0.1

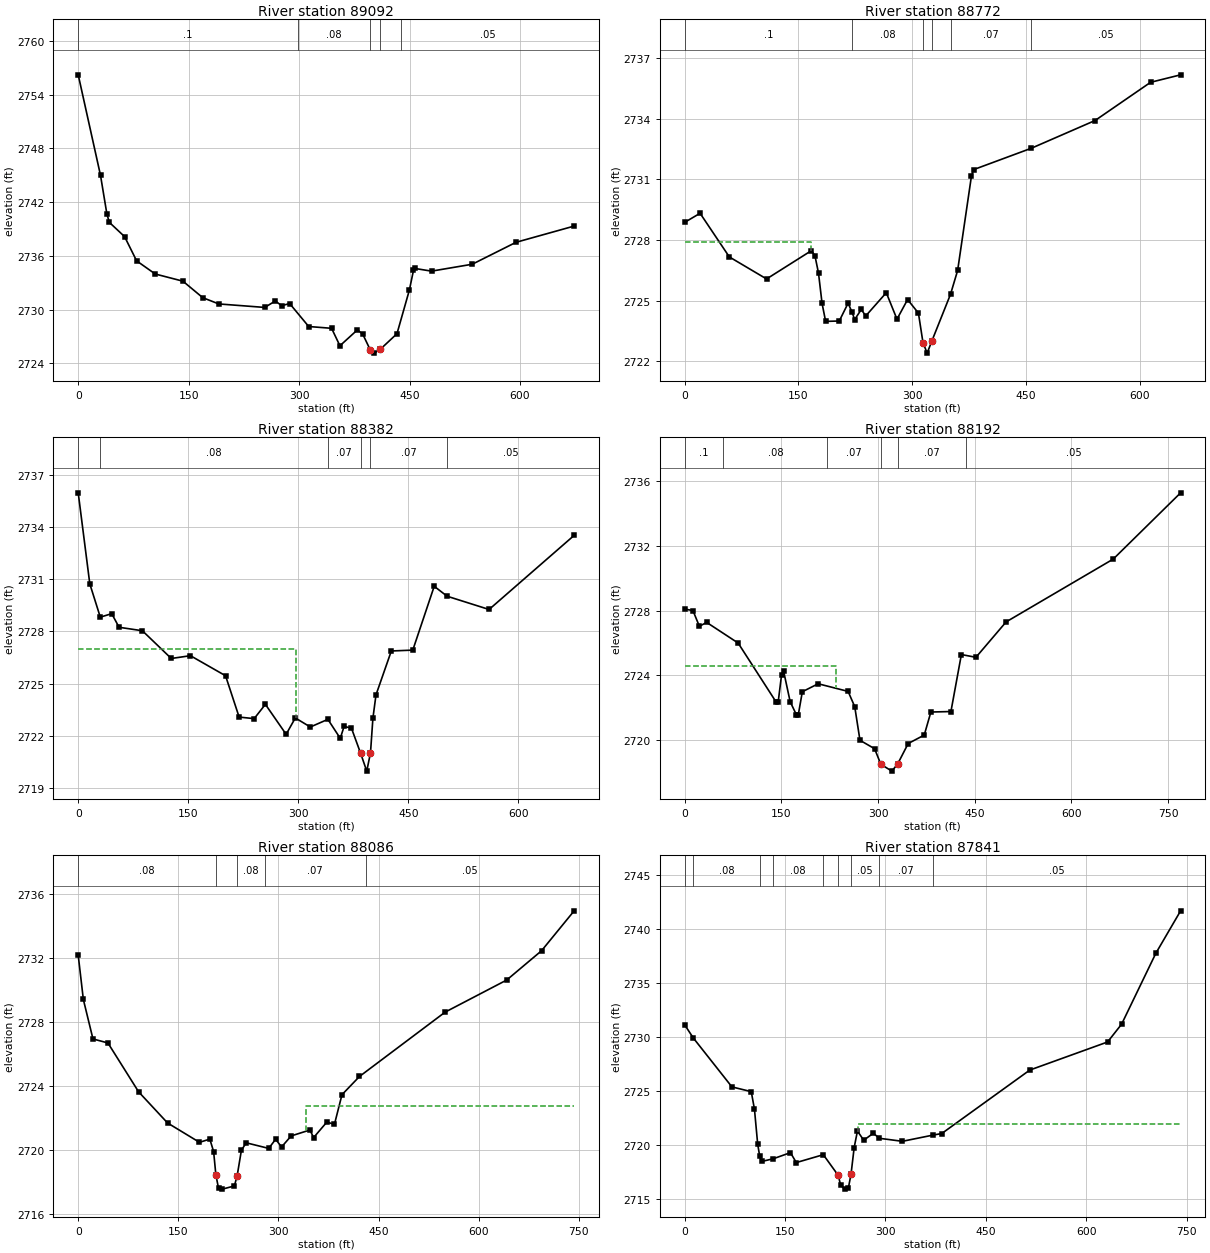
Type RM Length L Ch R = 1 ,89092   ,324,320.4,312.1
XS GIS Cut Line= 4
2316938.87132484 547147.178348462316709.12735467547264.134757389
2316539.00832684547431.0640534442316452.97366885 547586.18704031
#Sta/Elev= 30
       0  2756.2    30.3 2744.97    38.9 2740.69    42.2 2739.74      63 2738.14
    79.3 2735.44   104.6 2733.97   142.2 2733.17   169.1 2731.33   190.9 2730.63
   253.3 2730.24   267.7 2730.96   276.2 2730.44   287.2 2730.67     313 2728.11
   344.1 2727.91   355.4 2725.96   379.2 2727.74   386.5 2727.24   396.4 2725.54
   402.1 2725.14   410.4 2725.58   432.9 2727.31   449.7 2732.17   455.3 2734.37
   457.2 2734.59   479.8 2734.29   535.1 2735.06   594.6 2737.51   673.5 2739.32
#Mann= 5 ,-1,0
       0      .1       0   297.8     .08       0   396.4    .045       0
   410.4     .07       0   437.8     .05       0
Bank Sta=396.4,410.4
XS Rating Curve= 0 ,0
Exp/Cntr(USF)=0,0
Exp/Cntr=0.3,0.1

Type RM Length L Ch R = 1 ,88772   ,382.5,390.2,257.8
XS GIS Cut Line= 3
2316598.87060589546867.1565929492316384.85177167547212.416726996
2316310.12691136547448.821217378
#Sta/Elev= 30
       0 2728.87    20.3 2729.32    58.9 2727.16     108 2726.07   167.1 2727.47
   171.8 2727.22   176.5 2726.36   181.2 2724.86   185.9 2723.97   203.9 2723.99
   215.5 2724.87   220.8 2724.42   224.2 2724.06   232.9 2724.56   238.8 2724.24
   265.9 2725.39     280 2724.08     294 2725.05   308.3 2724.38   314.3 2722.92
   319.8  2722.4   325.9 2722.99   350.6 2725.31     360 2726.49   378.2 2731.16
   381.1 2731.48   457.4 2732.54   541.3 2733.91   614.5  2735.8   654.1 2736.17
#Mann= 6 ,-1,0
       0      .1       0   220.8     .08       0   314.3    .045       0
   325.9     .08       0   350.6     .07       0   457.4     .05       0
#XS Ineff= 2 , 0
          166.78 2727.91
Permanent Ineff=
       F       F
Bank Sta=314.3,325.9
XS Rating Curve= 0 ,0
Exp/Cntr(USF)=0,0
Exp/Cntr=0.3,0.1

Type RM Length L Ch R = 1 ,88382   ,130.7,189.3,232.4
XS GIS Cut Line= 3
2316498.61585657546745.3607065092316267.47636887547036.360129425
2316178.17917571547327.549954146
#Sta/Elev= 30
       0 2735.95    15.8 2730.73    30.1 2728.82    45.7 2729.02    55.7 2728.24
    87.5 2728.04   126.9 2726.45     153 2726.61   200.9 2725.46   219.4 2723.09
   239.9    2723   255.2 2723.82   283.5  2722.1     296 2723.04   316.5 2722.52
   340.4 2722.96   357.3 2721.87   362.5 2722.55   372.5 2722.46     385 2721.02
   393.4 2719.99  398.52 2721.04   401.8 2723.02     406 2724.36   426.9 2726.88
   456.2 2726.93   485.4 2730.59     503 2730.02   560.2 2729.26   676.2 2733.51
#Mann= 6 ,-1,0
       0      .1       0    30.1     .08       0   340.4     .07       0
     385    .045       0  398.52     .07       0     503     .05       0
#XS Ineff= 2 , 0
           296.9    2727
Permanent Ineff=
       F       F
Bank Sta=385,398.52
XS Rating Curve= 0 ,0
Exp/Cntr(USF)=0,0
Exp/Cntr=0.3,0.1

Type RM Length L Ch R = 1 ,88192   ,146.8,106,62.3
XS GIS Cut Line= 6
 2316428.2950081546725.2387002712316255.92658328546935.472238955
2316231.67003335546924.5870989772316164.37144802546913.428031163
2316116.33300783  546971.6389974 2316084.1200087547297.159830733
#Sta/Elev= 30
       0 2728.09    12.8    2728    22.8 2727.03    34.1 2727.27    82.9    2726
   142.1 2722.35     145 2722.35   150.3 2724.05   153.5 2724.26   163.6 2722.39
   173.4 2721.57   176.2 2721.57   182.5    2723   207.1 2723.49   253.5 2723.02
   263.8 2722.08   271.9 2720.01   294.6 2719.49   304.3 2718.53   321.4 2718.11
   330.5 2718.56   346.7 2719.81   371.6 2720.33   381.9 2721.75     413 2721.78
   429.2 2725.29   451.8 2725.12   498.6  2727.3   664.8 2731.17   769.3 2735.25
#Mann= 6 ,-1,0
       0      .1       0      60     .08       0   221.3     .07       0
   304.3    .045       0   330.5     .07       0   436.7     .05       0
#XS Ineff= 2 , 0
          235.27 2724.56
Permanent Ineff=
       F       F
Bank Sta=304.3,330.5
XS Rating Curve= 0 ,0
Exp/Cntr(USF)=0,0
Minor Loss Coefficient=0
Exp/Cntr=0.3,0.1

Type RM Length L Ch R = 1 ,88086   ,240.7,245.4,223.7
XS GIS Cut Line= 3
2316383.65031672546657.7455575312316095.71709999546950.347961563
2316069.25837197547281.860259748
#Sta/Elev= 30
       0 2732.19     7.7 2729.42    22.1 2726.95    44.5  2726.7    90.5 2723.64
   133.9 2721.69   181.7 2720.48   197.2 2720.68   202.9  2719.9  206.23 2718.45
   210.3 2717.59     216 2717.55     234 2717.75   238.22718.396   244.5 2719.98
   251.7 2720.45   285.4  2720.1   295.8 2720.67   304.7 2720.19   319.1 2720.88
   347.1 2721.25   352.8 2720.78   372.6 2721.75   383.9  2721.6   395.2 2723.46
   421.4  2724.6   549.8 2728.63   642.1 2730.64   694.2 2732.47   743.1 2734.97
#Mann= 5 ,-1,0
       0     .08       0  206.23    .045       0   238.2     .08       0
     280     .07       0  430.51     .05       0
#XS Ineff= 2 , 0
                          341.03         2722.77
Permanent Ineff=
       F       F
Bank Sta=206.23,238.2
XS Rating Curve= 0 ,0
Exp/Cntr(USF)=0,0
Exp/Cntr=0.3,0.1

Type RM Length L Ch R = 1 ,87841   ,413.7,396.8,371.5
XS GIS Cut Line= 3
 2316148.7874533546562.4584095822315934.61811171546883.108569738
2315916.73158689547238.281178297
#Sta/Elev= 30
       0  2731.1    12.9 2729.88    70.6 2725.35    99.5 2724.91   104.3 2723.28
   109.1 2720.05     112 2718.98   114.9 2718.44   132.2 2718.69   158.1 2719.26
   166.8 2718.34   207.2 2719.07   229.4 2717.16   233.1 2716.26   238.9 2715.88
   244.7 2716.01   248.6 2717.25   253.3 2719.73   258.2 2721.26   267.6 2720.41
     282 2721.06   290.8 2720.59   325.4 2720.31   371.5 2720.89   384.2 2721.03
   515.8 2726.91     632 2729.51     653 2731.16   704.1 2737.72   741.2 2741.66
#Mann= 9 ,-1,0
       0      .1       0    12.9     .08       0     112      .1       0
   132.2     .08       0   207.2     .08       0   229.4    .045       0
   248.6     .05       0   290.8     .07       0   371.5     .05       0
#XS Ineff= 2 , 0
                           258.8         2721.88
Permanent Ineff=
       F       F
Bank Sta=229.4,248.6
XS Rating Curve= 0 ,0
Exp/Cntr(USF)=0,0
Exp/Cntr=0.3,0.1