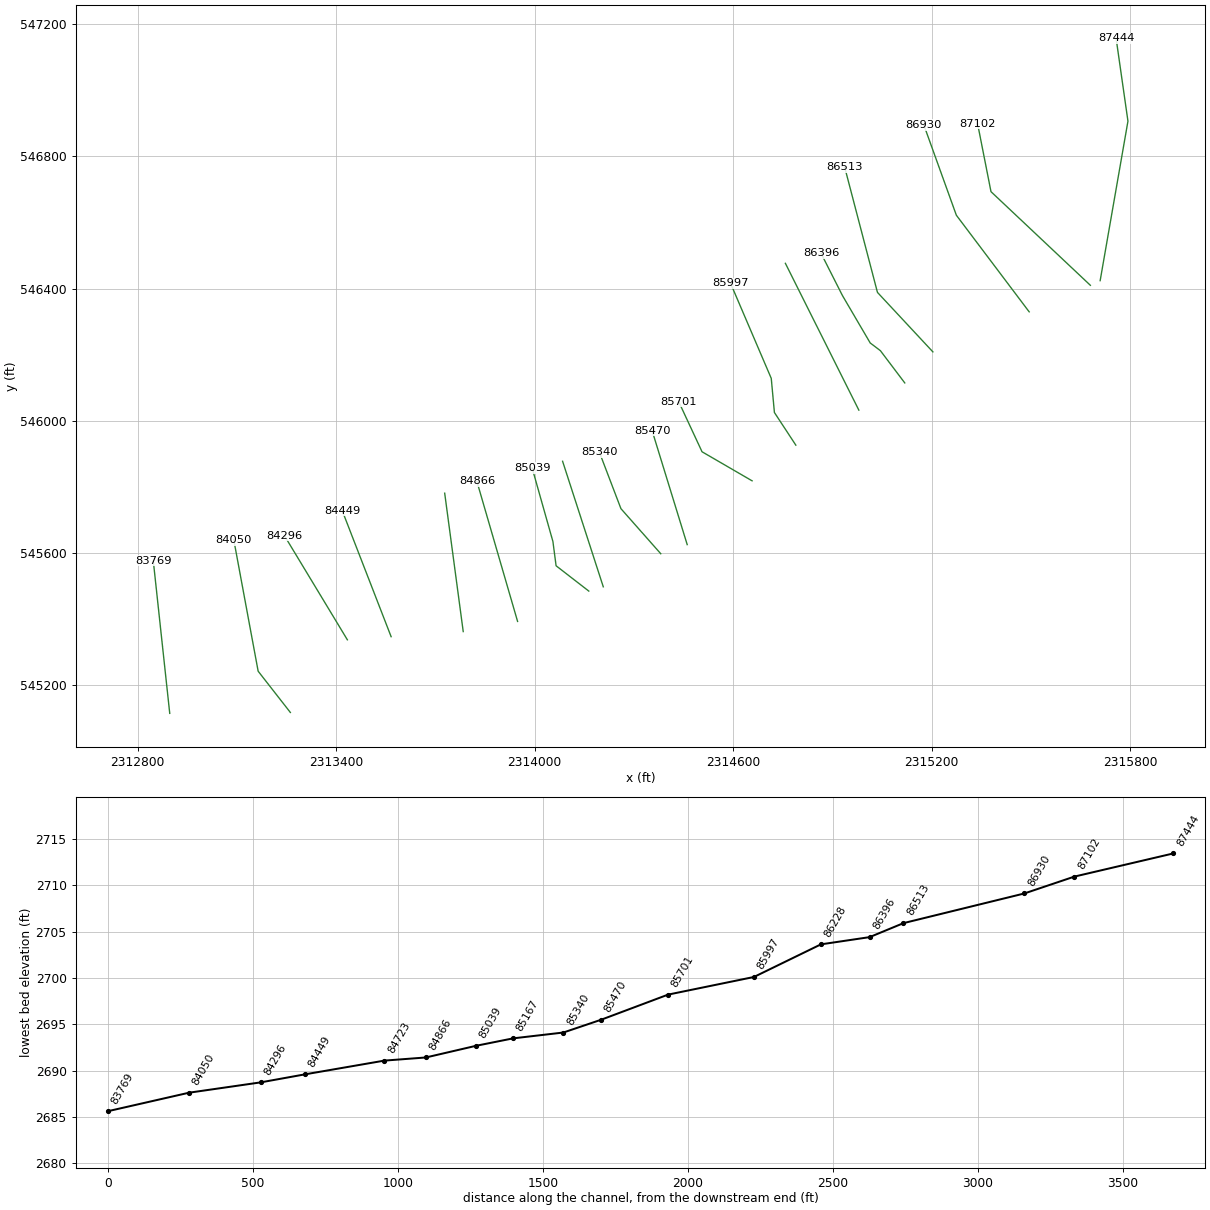
HEC-RAS study DEERCK.prj: DEERCK

--- DEERCK.g01 (geometry) --- (continued)

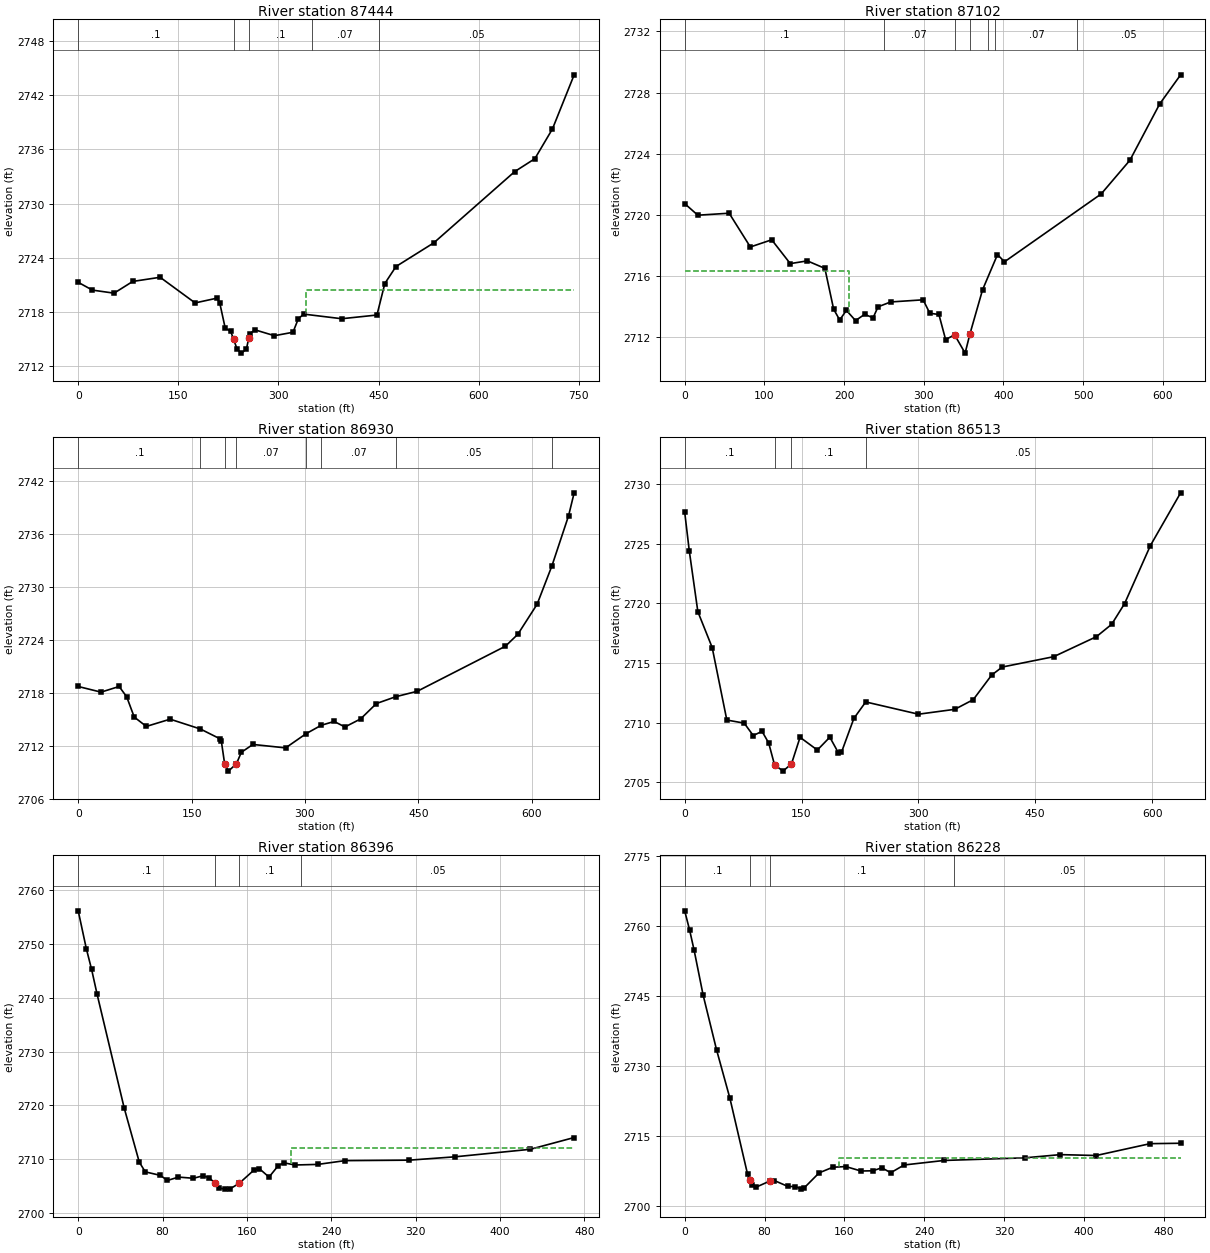
Type RM Length L Ch R = 1 ,87444   ,310.3,341.5,368.6
XS GIS Cut Line= 3
2315709.73094999546424.2861926122315793.77632136546906.768880111
2315757.97921874547157.348598458
#Sta/Elev= 30
       0 2721.28    21.2 2720.42    53.7 2720.08    81.7 2721.38   122.7 2721.84
   175.1    2719     208 2719.53     212    2719   220.2 2716.21   228.3 2715.86
   232.72714.999     238 2713.87   244.5 2713.44   251.9 2713.88   255.42715.069
   256.7 2715.57   264.8 2716.02   293.9 2715.37   321.7 2715.75   329.8 2717.26
   337.9 2717.76   394.7 2717.25   447.5 2717.66   459.3 2721.15     476 2723.03
   532.6 2725.65   653.8 2733.54     684 2734.97   710.4 2738.27   742.9 2744.26
#Mann= 5 ,-1,0
       0      .1       0   232.7    .045       0   255.4      .1       0
     350     .07       0     450     .05       0
#XS Ineff= 2 , 0
                          340.98         2720.44
Permanent Ineff=
       F       F
Bank Sta=232.7,255.4
XS Rating Curve= 0 ,0
Exp/Cntr(USF)=0,0
Exp/Cntr=0.3,0.1

Type RM Length L Ch R = 1 ,87102   ,176.5,172.6,168.2
XS GIS Cut Line= 3
2315680.15943043546410.2786307172315379.77504757546693.542660152
2315339.30875765546898.986901281
#Sta/Elev= 30
       0 2720.73    16.5 2719.97    55.8  2720.1    82.4 2717.89   109.2 2718.36
   132.5  2716.8   153.9 2716.98   175.9 2716.49   186.9 2713.82   194.5 2713.11
   202.9 2713.74   214.4 2713.07   225.8 2713.48   236.4 2713.25   242.6 2713.97
   258.4 2714.29   299.2 2714.43   307.6 2713.55     319 2713.47   327.4 2711.83
   338.72712.135   351.9 2710.94   357.92712.192   373.8 2715.09   392.5 2717.39
   401.3 2716.92   522.6 2721.36   558.7 2723.57     596 2727.25   622.3 2729.16
#Mann= 7 ,-1,0
       0      .1       0     250     .07       0   338.7    .045       0
   357.9     .07       0     380      .1       0     390     .07       0
  492.88     .05       0
#XS Ineff= 2 , 0
          205.66 2716.33
Permanent Ineff=
       F       F
Bank Sta=338.7,357.9
XS Rating Curve= 0 ,0
Exp/Cntr(USF)=0,0
Exp/Cntr=0.3,0.1

Type RM Length L Ch R = 1 ,86930   ,392.6,416.8,393.4
XS GIS Cut Line= 3
2315495.22555724546329.9896369022315275.03615439546622.328093459
2315176.80627087546895.317520947
#Sta/Elev= 30
       0  2718.7    30.2 2718.06    54.1  2718.7    64.1 2717.54    74.1 2715.24
    90.1 2714.18   121.6    2715   161.6 2713.89   187.3 2712.79   189.3 2712.54
   193.72709.956   198.7 2709.12   209.3 2709.95   215.8 2711.25   231.1 2712.14
   274.4 2711.75   301.5 2713.36   321.5 2714.31   338.6 2714.74   352.9 2714.12
   373.6 2715.03   394.5 2716.77     420 2717.54   448.6 2718.16   565.2 2723.26
   581.6 2724.61   607.1 2728.01   626.8 2732.38   648.7 2738.02   656.1 2740.62
#Mann= 8 ,-1,0
       0      .1       0   161.6     .07       0   193.7    .045       0
   209.3     .07       0   301.5      .1       0   321.5     .07       0
     420     .05       0   626.8      .1       0
Bank Sta=193.7,209.3
XS Rating Curve= 0 ,0
Exp/Cntr(USF)=0,0
Exp/Cntr=0.3,0.1

Type RM Length L Ch R = 1 ,86513   ,115.8,116.8,118
XS GIS Cut Line= 3
2315204.21669988546208.8181438032315036.55713178546388.868840547
2314937.75864999 546766.69326116
#Sta/Elev= 30
       0 2727.68     5.9 2724.42    16.9 2719.31    35.3  2716.3    54.1 2710.21
    76.4 2709.95      88 2708.91    99.3 2709.26   107.8 2708.29   115.3 2706.46
   126.2 2705.92   137.1 2706.53   148.1 2708.76   170.3 2707.69   186.3 2708.77
   197.3 2707.46   201.2 2707.49   217.2 2710.35   232.4 2711.73   300.1  2710.7
   346.7 2711.11   370.4 2711.92   394.1 2713.99   407.6 2714.66   473.7 2715.53
   528.5 2717.21   548.1 2718.25   564.7 2719.99   597.8 2724.86   636.6 2729.29
#Mann= 4 ,-1,0
       0      .1       0   115.3    .045       0   137.1      .1       0
   232.4     .05       0
Bank Sta=115.3,137.1
XS Rating Curve= 0 ,0
Exp/Cntr(USF)=0,0
Exp/Cntr=0.3,0.1

Type RM Length L Ch R = 1 ,86396   ,178.4,168,160.5
XS GIS Cut Line= 5
2315119.12470673 546115.005932522315045.48403002546212.541465929
2315014.64995623546235.9328322552314930.65368624546379.470761983
2314866.08366149546507.043415666
#Sta/Elev= 30
       0 2756.19     7.7 2749.14    12.7 2745.29    17.9 2740.67    43.6  2719.5
    57.9 2709.43    63.6 2707.62    77.9 2706.97    84.6 2706.02      95 2706.65
   109.3 2706.43     118 2706.88   123.9 2706.57   129.3  2705.6   133.9 2704.61
   138.9 2704.41   143.9 2704.45   152.72705.502     167 2708.02   171.6 2708.24
   180.9 2706.65   189.6 2708.76   194.8 2709.32   205.4  2708.9   227.2 2709.01
   252.9 2709.71   313.9  2709.8   357.1 2710.42   428.6 2711.82   470.2 2714.01
#Mann= 4 ,-1,0
       0      .1       0   129.3    .045       0   152.7      .1       0
  210.92     .05       0
#XS Ineff= 2 , 0
                          201.39         2712.15
Permanent Ineff=
       F       F
Bank Sta=129.3,152.7
XS Rating Curve= 0 ,0
Exp/Cntr(USF)=0,0
Exp/Cntr=0.3,0.1

Type RM Length L Ch R = 1 ,86228   ,243.5,231,221.2
XS GIS Cut Line= 2
2314980.30899284546032.6694331222314758.27173676546476.743945274
#Sta/Elev= 30
       0 2763.32       5 2759.14     9.5 2754.82    18.5 2745.22    31.9 2733.52
    45.3  2723.1    62.9 2706.88   65.35 2705.54    67.7 2704.49    71.9 2704.09
    85.5 2705.39    89.9 2705.46   103.4  2704.2   110.8 2704.19   116.8 2703.63
   119.7 2703.91   134.6 2707.12   148.2 2708.32   161.3 2708.47   176.4 2707.52
   188.4 2707.56   197.3 2708.21   206.3 2707.15   219.7 2708.81   259.7 2709.78
   340.5 2710.34   376.1 2711.03     412 2710.84   465.9 2713.38   496.5 2713.47
#Mann= 4 ,-1,0
       0      .1       0   65.35    .045       0    85.5      .1       0
     270     .05       0
#XS Ineff= 2 , 0
                          154.91         2710.22
Permanent Ineff=
       F       F
Bank Sta=65.35,85.5
XS Rating Curve= 0 ,0
Exp/Cntr(USF)=0,0
Exp/Cntr=0.3,0.1

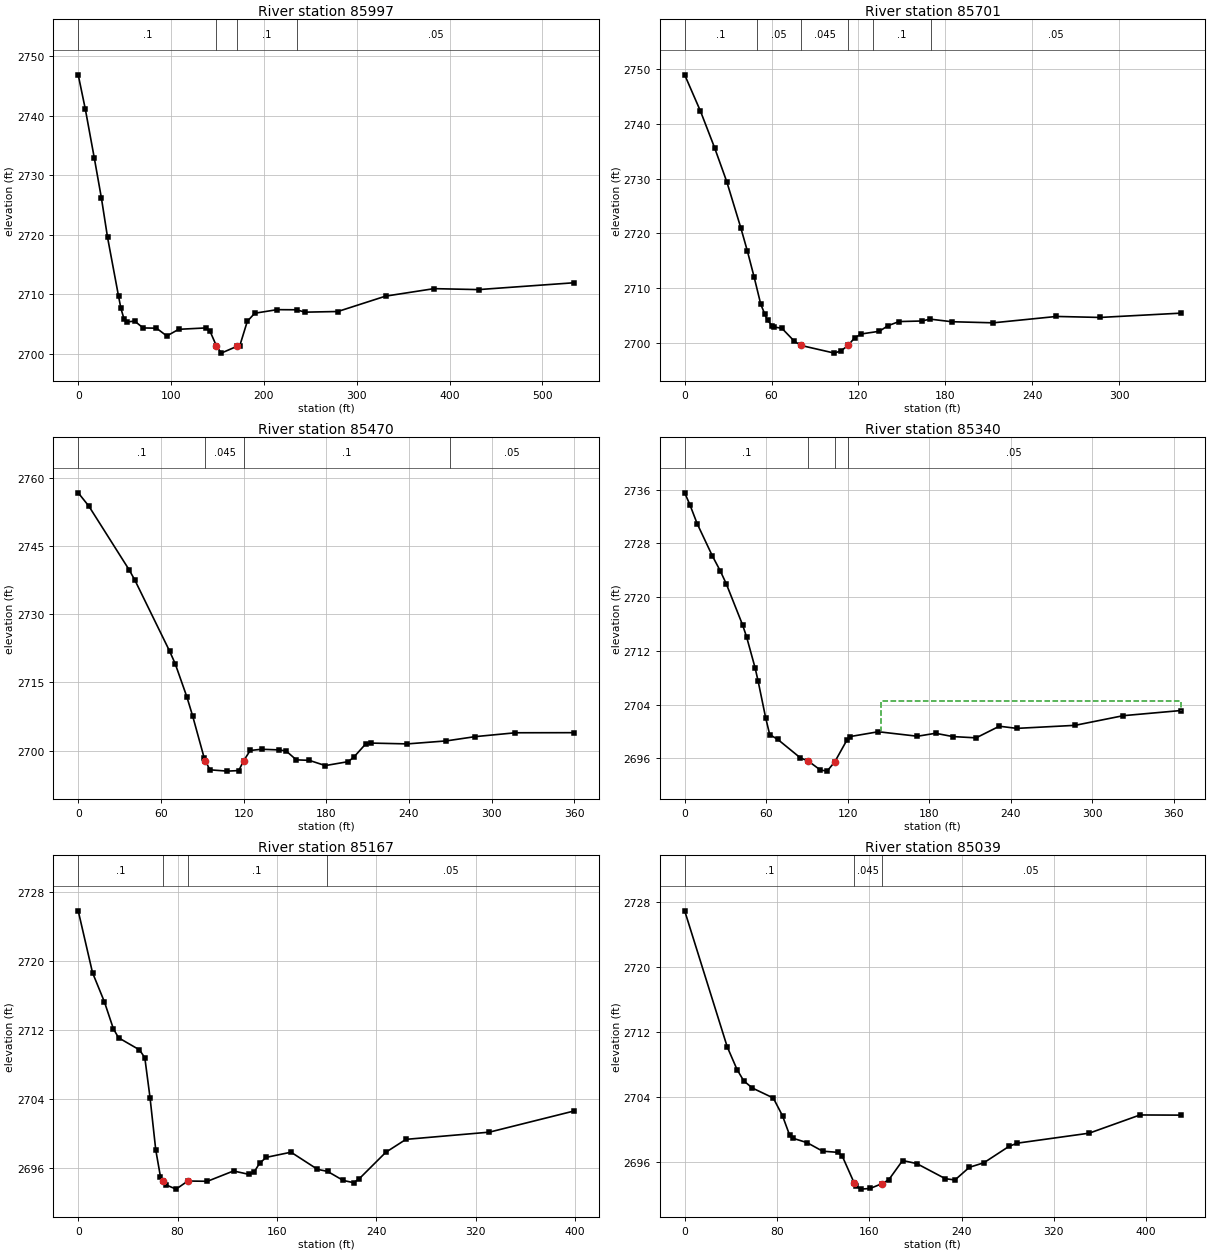
Type RM Length L Ch R = 1 ,85997   ,256.2,295.9,321.5
XS GIS Cut Line= 4
2314789.86841987545926.7153979472314725.10271335546025.505352383
2314715.57226444546128.7432458482314592.77680326546415.878666514
#Sta/Elev= 30
       0 2746.85     7.7 2741.05    17.4 2732.81      25 2726.14    31.6 2719.54
    43.4  2709.7      46 2707.61    49.2 2705.92    52.1 2705.34    60.8 2705.49
    69.9 2704.34    84.3  2704.3    95.4 2702.99   108.2 2704.11   137.1 2704.34
   141.9  2703.8   148.82701.343     154 2700.11   170.92701.249     174 2701.35
   182.1 2705.45   190.1 2706.81   214.2 2707.41   235.3 2707.39     244 2706.99
   279.6  2707.1     331 2709.68   383.2 2710.94   431.1 2710.78   534.1 2711.93
#Mann= 4 ,-1,0
       0      .1       0   148.8    .045       0   170.9      .1       0
   235.3     .05       0
Bank Sta=148.8,170.9
XS Rating Curve= 0 ,0
Exp/Cntr(USF)=0,0
Exp/Cntr=0.3,0.1

Type RM Length L Ch R = 1 ,85701   ,255.2,230.9,201.4
XS GIS Cut Line= 3
2314657.60741209545818.8482395882314506.34485006545906.705989772
2314435.67903967546058.550267362
#Sta/Elev= 30
       0  2748.9    10.9 2742.28    20.6 2735.66    29.1  2729.4    38.7 2721.08
    43.3 2716.79    47.9 2712.12    52.5 2707.14    55.4 2705.25    57.2 2704.18
    60.4 2703.22    61.8 2702.96    67.1 2702.74    75.7 2700.38    80.3 2699.61
   103.4 2698.21   108.2 2698.67     1132699.655   117.3    2701   121.9  2701.7
   134.4 2702.19   140.4 2703.21     148 2703.96   163.6 2704.06   169.5  2704.4
   184.4 2703.93     213 2703.73   256.7 2704.89   286.8 2704.71   342.4 2705.49
#Mann= 6 ,-1,0
       0      .1       0      50     .05       0    80.3    .045       0
     113     .05       0     130      .1       0     170     .05       0
Bank Sta=80.3,113
XS Rating Curve= 0 ,0
Exp/Cntr(USF)=0,0
Exp/Cntr=0.3,0.1

Type RM Length L Ch R = 1 ,85470   ,115.1,130.3,141.9
XS GIS Cut Line= 2
2314461.50154556545625.8551645882314355.66663346545969.818628902
#Sta/Elev= 30
       0 2756.73     7.7 2753.81      37 2739.77    41.1 2737.53    66.3 2721.92
    70.4 2719.12    78.8 2711.88      83 2707.68    91.4 2698.42    92.32697.809
    95.5 2695.79   108.1  2695.5   116.5 2695.62     120 2697.74   124.8 2700.05
   133.2 2700.31   145.8 2700.17   150.9 2699.93   158.3 2697.98   167.7 2697.87
   179.3 2696.72     196 2697.59   200.2 2698.64   208.5 2701.44   212.7 2701.67
   238.8 2701.49   267.1 2702.15   288.1 2703.09   317.3 2703.94   359.9 2703.96
#Mann= 4 ,-1,0
       0      .1       0    92.3    .045       0     120      .1       0
     270     .05       0
Bank Sta=92.3,120
XS Rating Curve= 0 ,0
Exp/Cntr(USF)=0,0
Exp/Cntr=0.3,0.1

Type RM Length L Ch R = 1 ,85340   ,183.6,173.4,159.5
XS GIS Cut Line= 3
2314381.58916516545598.2690716522314261.16772607545734.649978569
2314195.87899404545905.851542572
#Sta/Elev= 30
       0 2735.52     3.9 2733.72     9.2 2730.93    20.3 2726.17    26.3 2723.87
    30.6    2722    42.7 2715.84    45.6 2714.08    51.9 2709.45    54.1 2707.49
    59.7 2701.99    62.6 2699.56    68.6 2698.83    85.2 2696.09    90.9 2695.63
    99.9 2694.29   104.9 2694.12   110.6 2695.52   119.3 2698.68   122.1 2699.27
   142.6 2699.98   171.4 2699.31   184.7 2699.75   197.5 2699.26   214.6 2699.07
   231.7  2700.8   244.6 2700.48   287.4 2700.93     323 2702.37   365.2 2703.13
#Mann= 4 ,-1,0
       0      .1       0    90.9    .045       0   110.6      .1       0
     120     .05       0
#XS Ineff= 2 , 0
                          144.23         2704.51
Permanent Ineff=
       F       F
Bank Sta=90.9,110.6
XS Rating Curve= 0 ,0
Exp/Cntr(USF)=0,0
Exp/Cntr=0.3,0.1

Type RM Length L Ch R = 1 ,85167   ,131.3,127.5,121.5
XS GIS Cut Line= 2
2314207.80903568545498.2307117662314084.85377015545877.991278701
#Sta/Elev= 30
       0 2725.82    11.5 2718.64    21.1 2715.24    28.3 2712.12    32.5 2711.07
    49.3 2709.67    53.6 2708.76    57.8 2704.13    62.4 2698.06    66.2 2694.93
   67.98 2694.49    70.4    2694    78.8 2693.49    88.22694.432     104  2694.4
     125  2695.6   137.6  2695.2   141.7 2695.51     146 2696.49   151.3 2697.18
   171.3 2697.78   192.6 2695.79   200.7 2695.55   213.3  2694.5   221.7 2694.24
   225.9 2694.65   247.6 2697.77   263.8 2699.27     331 2700.11   399.2 2702.57
#Mann= 4 ,-1,0
       0      .1       0   67.98    .045       0    88.2      .1       0
     200     .05       0
Bank Sta=67.98,88.2
XS Rating Curve= 0 ,0
Exp/Cntr(USF)=0,0
Exp/Cntr=0.3,0.1

Type RM Length L Ch R = 1 ,85039   ,168.1,173.1,175.8
XS GIS Cut Line= 4
 2314164.0548171545485.2826219712314065.17313217545561.836184492
2314055.60393686545635.2000152432313992.87254535545857.417995341
#Sta/Elev= 30
       0 2726.95    36.9  2710.2    45.4 2707.41    51.2 2706.02    58.6 2705.14
    76.8 2703.91    84.8 2701.72    90.9 2699.36    93.9 2698.95   106.1 2698.41
   119.6 2697.36   132.5 2697.22   136.5 2696.79   146.8 2693.49   148.6 2693.05
   152.6 2692.69   160.7 2692.77   170.92693.354   176.8 2693.82   188.9 2696.21
   201.1 2695.84     226 2693.97   234.3 2693.82   246.8 2695.38   259.3 2695.93
   281.2 2697.96   288.4 2698.35   350.7 2699.58   394.7 2701.82   429.9  2701.8
#Mann= 3 ,-1,0
       0      .1       0   146.8    .045       0   170.9     .05       0
Bank Sta=146.8,170.9
XS Rating Curve= 0 ,0
Exp/Cntr(USF)=0,0
Exp/Cntr=0.3,0.1

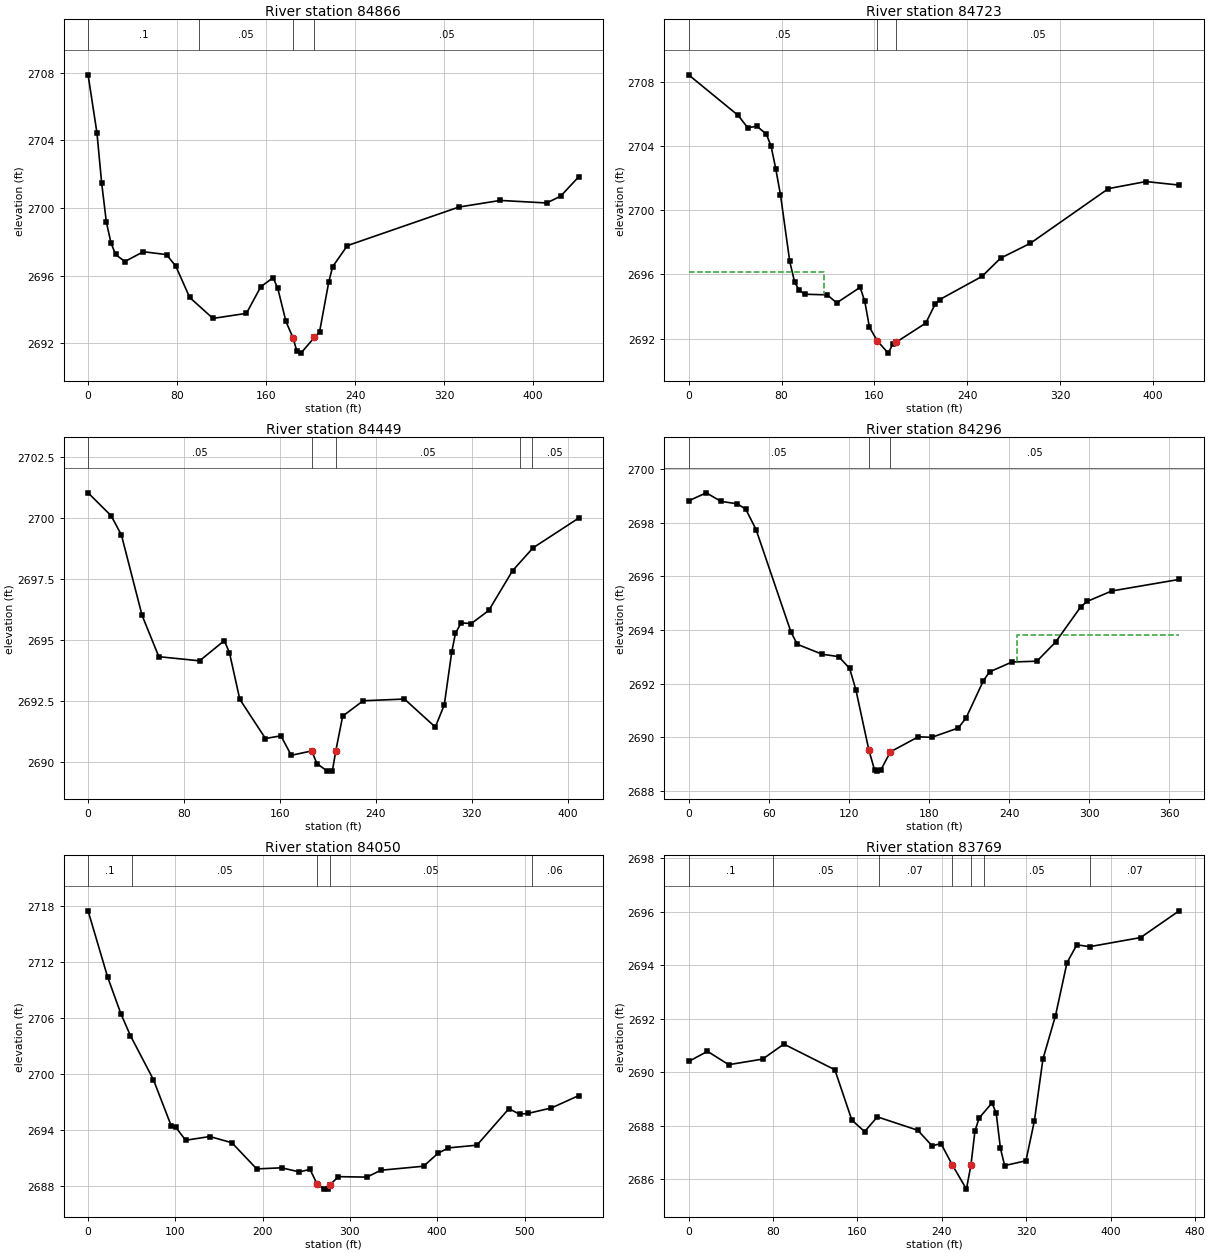
Type RM Length L Ch R = 1 ,84866   ,146.1,143.2,137.8
XS GIS Cut Line= 2
2313948.81111636545393.4547465822313825.85585084545816.794394969
#Sta/Elev= 30
       0 2707.87       8 2704.43    12.2 2701.49    16.4 2699.19    20.5 2697.96
    24.7 2697.26      33 2696.84    49.7 2697.42    70.5 2697.25    78.9 2696.56
    91.3 2694.72   112.2 2693.48   142.3 2693.78   155.2 2695.35   166.3 2695.89
   170.5 2695.25   177.8  2693.3   184.3 2692.31   187.5 2691.57   191.3 2691.43
   203.42692.358     208 2692.68   216.3 2695.64   219.8 2696.54     233 2697.78
   333.3 2700.06   370.4 2700.45   412.1  2700.3   424.6  2700.7   440.8 2701.84
#Mann= 4 ,-1,0
       0      .1       0     100     .05       0   184.3    .045       0
   203.4     .05       0
Bank Sta=184.3,203.4
XS Rating Curve= 0 ,0
Exp/Cntr(USF)=0,0
Exp/Cntr=0.3,0.1

Type RM Length L Ch R = 1 ,84723   ,264.2,273.6,279
XS GIS Cut Line= 2
2313784.46938729545362.8242801132313728.43913971545781.494741201
#Sta/Elev= 30
       0 2708.43    42.7  2705.9    50.8 2705.14    58.9 2705.22    66.9 2704.74
      71 2703.99      75 2702.59    79.1 2700.96    87.1  2696.8    91.2 2695.54
    95.2    2695   100.2 2694.76   119.4 2694.72   127.5 2694.22   147.7 2695.19
   151.7 2694.31   155.7 2692.71   162.5 2691.85   171.9 2691.09   175.9 2691.66
     1792691.783   204.2 2692.96   212.2 2694.13   216.3 2694.43   252.6 2695.87
   268.7 2697.01   294.2 2697.93   361.5 2701.34   393.8 2701.78   422.4 2701.56
#Mann= 3 ,-1,0
       0     .05       0   162.5    .045       0     179     .05       0
#XS Ineff= 2 , 0
          116.45 2696.15
Permanent Ineff=
       F       F
Bank Sta=162.5,179
XS Rating Curve= 0 ,0
Exp/Cntr(USF)=0,0
Exp/Cntr=0.3,0.1

Type RM Length L Ch R = 1 ,84449   ,148.2,153.6,158.3
XS GIS Cut Line= 2
2313566.57398003545347.2603224512313418.71638225545728.577285153
#Sta/Elev= 30
       0 2701.04    19.2  2700.1    27.8 2699.31      45 2696.01      59 2694.31
      93 2694.14   113.6 2694.97   117.9 2694.47   126.5 2692.56   147.9 2690.95
   160.8 2691.06   169.4 2690.26   186.5 2690.44   190.8 2689.92   199.4 2689.61
   203.7 2689.62  206.53 2690.44   212.3 2691.87   229.4  2692.5   263.8 2692.57
   289.5 2691.42     297 2692.33   303.2  2694.5   306.3 2695.27     311  2695.7
   319.5 2695.67   334.1 2696.21   353.9 2697.84     371 2698.78     409    2700
#Mann= 5 ,-1,0
       0     .05       0   186.5    .045       0  206.53     .05       0
     360     .06       0     370     .05       0
Bank Sta=186.5,206.53
XS Rating Curve= 0 ,0
Exp/Cntr(USF)=0,0
Exp/Cntr=0.3,0.1

Type RM Length L Ch R = 1 ,84296   ,257.6,246.3,236.8
XS GIS Cut Line= 2
2313434.28033991545337.9219478542313244.40005644545652.313892612
#Sta/Elev= 30
       0 2698.82    13.2 2699.12    24.3  2698.8    36.5 2698.71    42.8 2698.51
    50.5 2697.75    76.7 2693.92    81.4 2693.47     100  2693.1   112.4 2693.01
   120.6 2692.57   125.3 2691.76     135 2689.52   139.3 2688.77   140.8 2688.74
     144 2688.79   151.1 2689.46     172 2690.02     182    2690     202 2690.35
   207.8 2690.73   220.7 2692.11   225.3 2692.44   242.1 2692.81   260.8 2692.84
   274.9 2693.56   293.5 2694.86   298.4 2695.07   316.9 2695.46   367.3 2695.89
#Mann= 3 ,-1,0
       0     .05       0     135    .045       0   151.1     .05       0
#XS Ineff= 2 , 0
                          245.73         2693.81
Permanent Ineff=
       F       F
Bank Sta=135,151.1
XS Rating Curve= 0 ,0
Exp/Cntr(USF)=0,0
Exp/Cntr=0.3,0.1

Type RM Length L Ch R = 1 ,84050   ,283.1,280.4,278.6
XS GIS Cut Line= 3
2313262.00989017545118.0400137992313164.60552862545242.863007318
2313091.02692873545639.754275839
#Sta/Elev= 30
       0 2717.52    22.5 2710.38    37.7 2706.44    48.5 2704.12    74.8  2699.4
    95.3 2694.42   100.4 2694.28   111.8 2692.88   139.5 2693.28   164.8 2692.61
   193.2  2689.8   221.7 2689.92     242 2689.48   254.3 2689.75   262.4 2688.17
   270.5 2687.63   274.6 2687.64   277.4 2688.12   286.8 2688.97   319.3 2688.92
   335.6 2689.66   384.4 2690.09   400.9 2691.48   412.9 2692.06   445.5 2692.35
   482.1 2696.27   494.3 2695.68   503.9 2695.76   530.9 2696.35     562 2697.67
#Mann= 5 ,-1,0
       0      .1       0      50     .05       0   262.4    .045       0
   277.4     .05       0  508.33     .06       0
Bank Sta=262.4,277.4
XS Rating Curve= 0 ,0
Exp/Cntr(USF)=0,0
Exp/Cntr=0.3,0.1

Type RM Length L Ch R = 1 ,83769   ,147.9,150.6,152.8
XS GIS Cut Line= 2
 2312897.3238006545115.3573532982312847.51913608545577.606895838
#Sta/Elev= 30
       0  2690.4    17.9 2690.78      38 2690.28    70.2 2690.49    90.3 2691.05
   138.6 2690.09   154.7 2688.21   166.8 2687.78   178.9 2688.33   217.2 2687.83
   230.7 2687.25   239.2 2687.33   249.7 2686.55   263.3 2685.63   267.62686.537
   271.4 2687.81   275.4 2688.29   287.5 2688.85   291.5 2688.47   295.5 2687.16
   299.5 2686.51   319.7 2686.69   327.7 2688.18   335.8 2690.49   347.7 2692.11
   358.6 2694.09   367.9 2694.76     380 2694.69   428.3 2695.03   464.9 2696.03
#Mann= 7 ,-1,0
       0      .1       0      80     .05       0     180     .07       0
   249.7    .045       0   267.6     .07       0     280     .05       0
     380     .07       0
Bank Sta=249.7,267.6
XS Rating Curve= 0 ,0
Exp/Cntr(USF)=0,0
Exp/Cntr=0.3,0.1