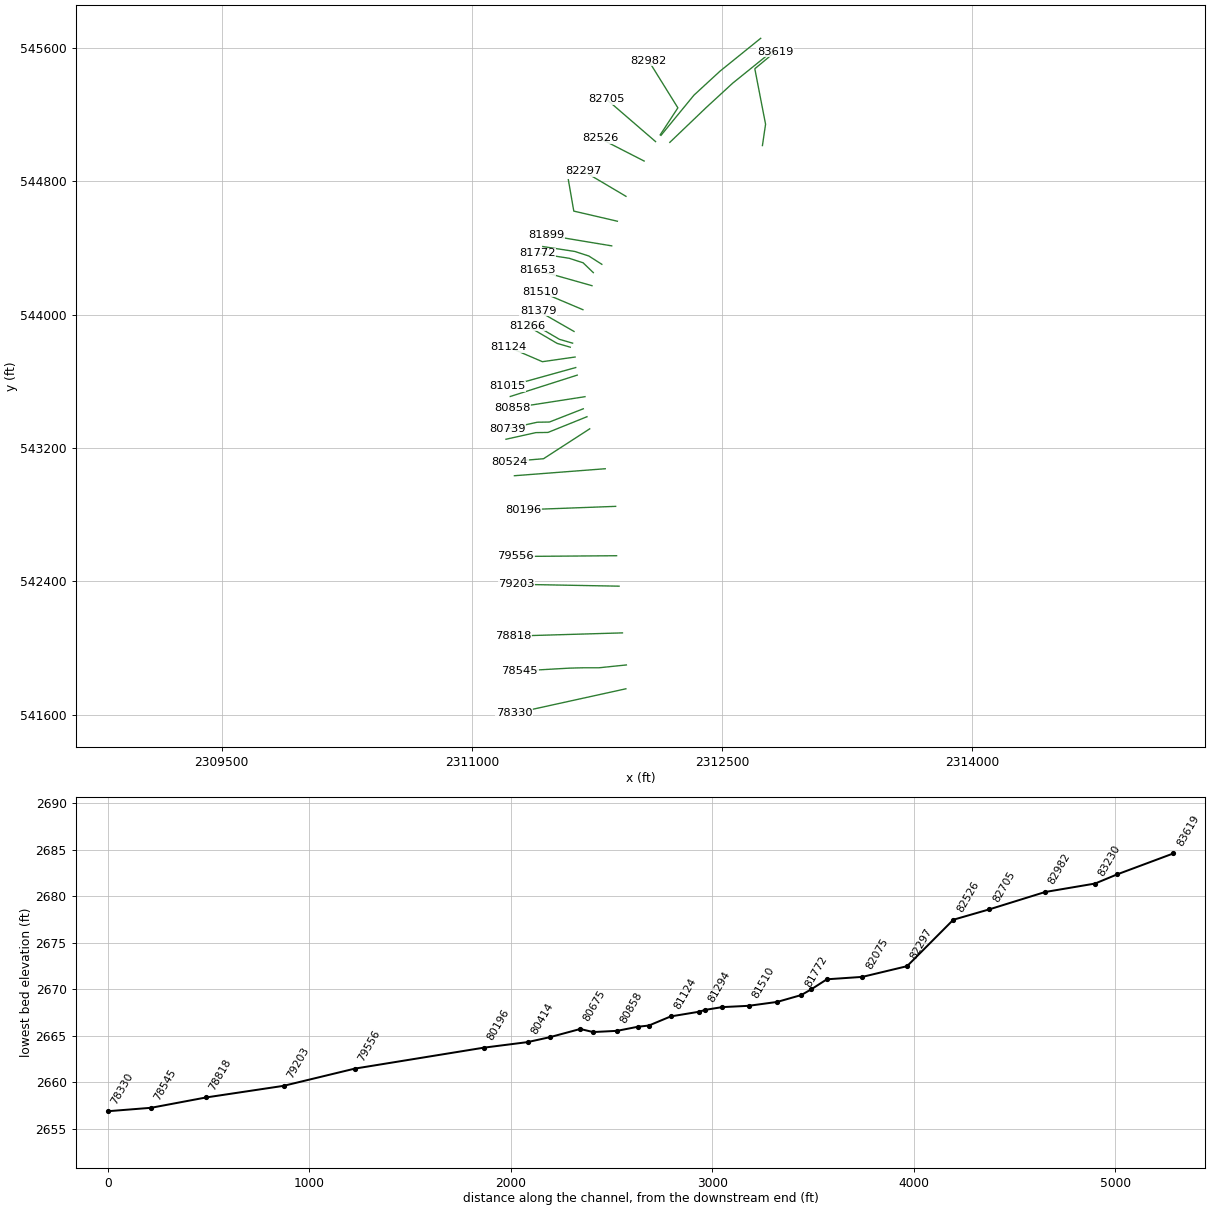
HEC-RAS study DEERCK.prj: DEERCK

--- DEERCK.g01 (geometry) --- (continued)

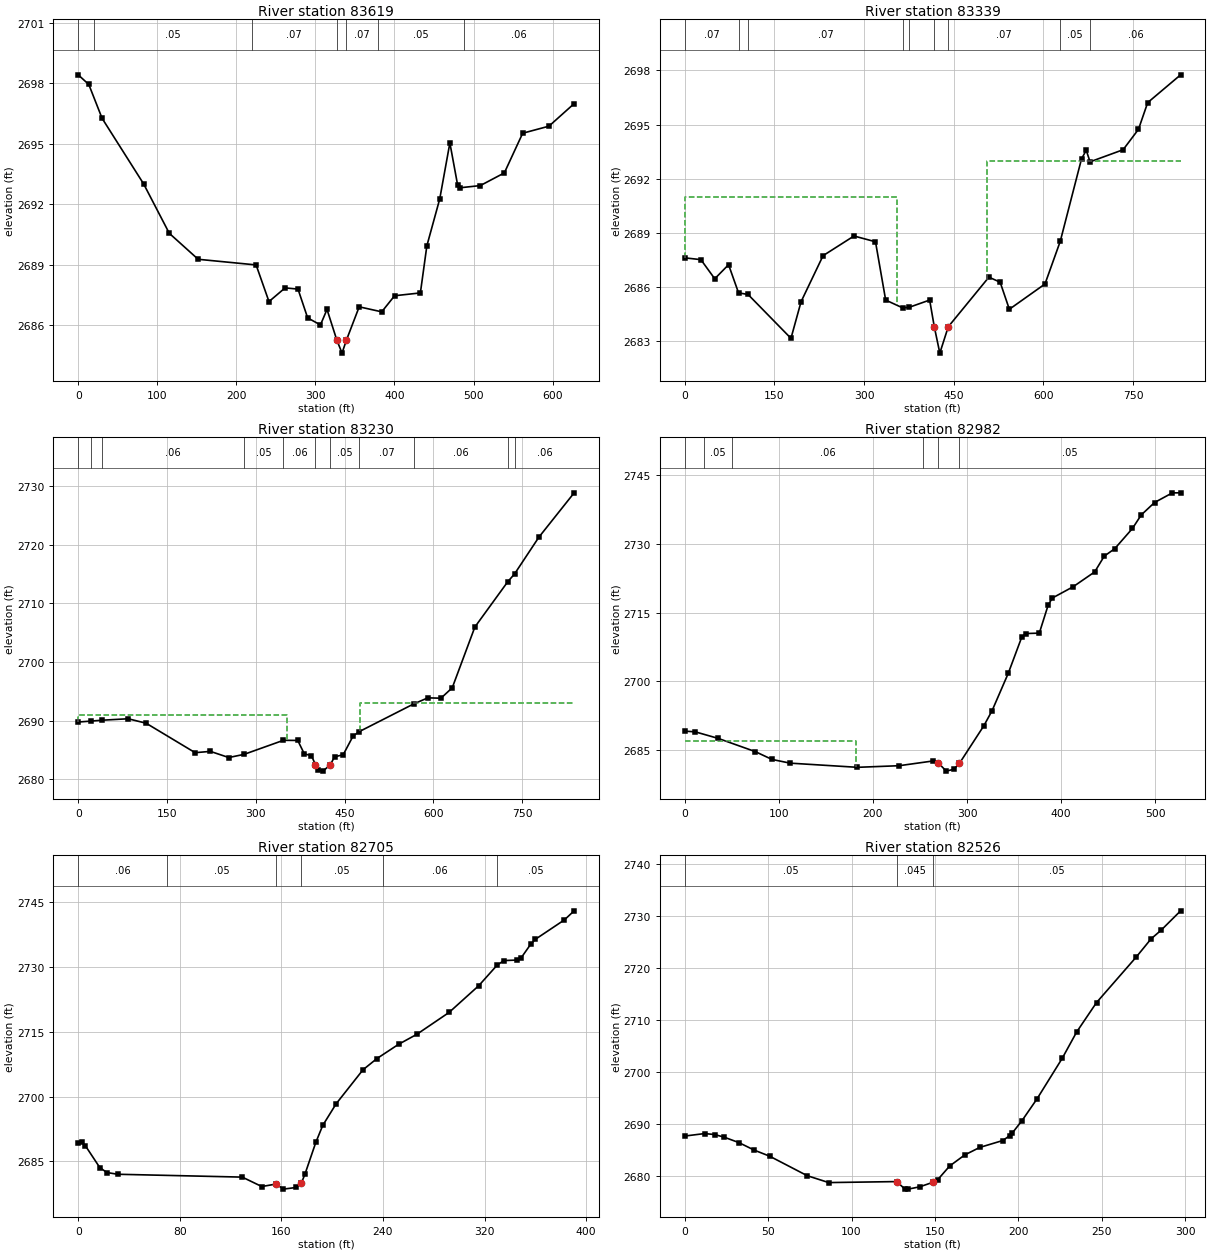
Type RM Length L Ch R = 1 ,83619   ,309.6,280,246.4
XS GIS Cut Line= 4
2312742.86899349545015.2510743562312761.66603335 545143.15581942
2312697.19577909545476.0249594372312819.50401229545577.606895838
#Sta/Elev= 30
       0 2698.42    13.4 2697.94    30.2 2696.26    82.8    2693   115.2 2690.55
   151.7 2689.26     225 2688.98   241.3 2687.16   261.7 2687.84     278 2687.78
   290.2 2686.35   306.4    2686   314.7 2686.77     327 2685.26   333.7  2684.6
   339.1 2685.23   355.4  2686.9   383.9 2686.65   400.2 2687.45   432.8 2687.59
     441 2689.93   457.3 2692.26   470.1 2695.04   479.8 2692.97   482.6 2692.81
   508.6 2692.92     539 2693.55   562.2 2695.52   595.4 2695.87   627.3 2696.99
#Mann= 7 ,-1,0
       0     .06       0      20     .05       0  219.28     .07       0
     327    .045       0   339.1     .07       0  379.28     .05       0
  488.33     .06       0
Bank Sta=327,339.1
XS Rating Curve= 0 ,0
Exp/Cntr(USF)=0,0
Exp/Cntr=0.3,0.1

Type RM Length L Ch R = 1 ,83339   ,112.1,109,108
XS GIS Cut Line= 4
2312187.60733124545034.4247734592312407.05913427545244.538201887
2312564.25510665545389.2830081372312807.05284616545585.388874669
#Sta/Elev= 30
       0 2687.62    27.1 2687.52    50.3 2686.46    73.4 2687.24    90.1 2685.68
     106 2685.59   177.8 2683.16   194.7 2685.19   231.5 2687.74   283.2 2688.83
   319.2 2688.51   336.2 2685.28   364.5 2684.85   375.6 2684.88   409.8 2685.28
   417.5 2683.81   426.8 2682.34   440.9  2683.8   508.9 2686.55   527.7 2686.27
   543.1 2684.77   602.7 2686.17   628.3 2688.54   663.8  2693.1   671.7 2693.58
   678.1 2692.94   733.4 2693.61   759.1 2694.74   774.5 2696.22   829.6 2697.76
#Mann= 9 ,-1,0
       0     .07       0    90.1     .06       0     106     .07       0
   364.5     .05       0   375.6     .07       0   417.5    .045       0
   440.9     .07       0   628.3     .05       0   678.1     .06       0
#XS Ineff= 2 , 0
             355    2691     505            2693
Permanent Ineff=
       F       F
Bank Sta=417.5,440.9
XS Rating Curve= 0 ,0
Exp/Cntr(USF)=0,0
Exp/Cntr=0.3,0.1

Type RM Length L Ch R = 1 ,83230   ,202.3,248,291
XS GIS Cut Line= 4
 2312134.6898752545076.4474591452312332.35213749545317.688802895
2312489.54810987545462.4336091452312732.34584939545658.539475677
#Sta/Elev= 30
       0 2689.74    21.3  2689.9    40.2 2690.05    84.4  2690.3   114.7 2689.54
   197.5 2684.51   223.3 2684.73   254.3 2683.68   280.1 2684.22   346.6 2686.62
   370.8  2686.6     382 2684.29   393.8 2684.02  400.76 2682.47   405.6 2681.54
   413.3 2681.36   425.42682.397   433.1  2683.8   447.6 2684.16   464.3 2687.35
   474.8 2688.11   566.4 2692.82   590.6 2693.87   612.7 2693.81   631.8 2695.59
     670 2705.96   725.6  2713.7     737 2715.02   778.2 2721.31   837.7 2728.87
#Mann= 11 ,-1,0
       0     .06       0    21.3     .05       0    40.2     .06       0
   280.1     .05       0   346.6     .06       0  400.76    .045       0
   425.4     .05       0   474.8     .07       0   566.4     .06       0
   725.6      .1       0     737     .06       0
#XS Ineff= 2 , 0
           353.3    2691   476.7            2693
Permanent Ineff=
       F       F
Bank Sta=400.76,425.4
XS Rating Curve= 0 ,0
Exp/Cntr(USF)=0,0
Exp/Cntr=0.3,0.1

Type RM Length L Ch R = 1 ,82982   ,266.7,276.2,285.3
XS GIS Cut Line= 3
 2312130.0206879545079.5602506772312235.85559999545241.425410354
2312059.98287842 545524.68943979
#Sta/Elev= 30
       0 2689.16    11.2 2689.01    35.4 2687.59      75  2684.7    92.7    2683
   111.9 2682.19   183.5 2681.28   227.8 2681.63   263.7 2682.66   269.12682.297
   277.9 2680.45   285.9 2680.86   291.92682.152   317.9 2690.37   326.6 2693.65
   343.8  2701.8   357.9 2709.56   362.6 2710.42   376.7 2710.51   386.1 2716.61
   390.5 2718.15   412.7 2720.62   435.5 2723.84   445.7 2727.28   456.8  2728.9
   475.6  2733.3     485 2736.26   499.1 2738.96     518 2741.06   526.8 2741.07
#Mann= 6 ,-1,0
       0     .06       0      20     .05       0      50     .06       0
  253.39     .05       0   269.1    .045       0   291.9     .05       0
#XS Ineff= 2 , 0
          182.05 2686.97
Permanent Ineff=
       F       F
Bank Sta=269.1,291.9
XS Rating Curve= 0 ,0
Exp/Cntr(USF)=0,0
Exp/Cntr=0.3,0.1

Type RM Length L Ch R = 1 ,82705   ,171.6,179.1,185.7
XS GIS Cut Line= 2
2312102.00556411545039.0939607582311806.29036854545294.342866403
#Sta/Elev= 30
       0 2689.37     2.8 2689.43     5.6 2688.65      17 2683.58    22.6 2682.43
    31.1 2682.03   129.2 2681.37   144.6 2679.19   155.9 2679.77   161.6 2678.59
   171.5 2678.97   175.8 2680.02   178.6 2682.07   187.1 2689.38   192.6 2693.34
   203.2 2698.36   224.3 2706.21   235.3 2708.81   252.3  2712.1   266.6  2714.4
   292.1 2719.48   315.4 2725.65     330 2730.44   335.3 2731.48   345.9  2731.6
   348.8 2732.09   356.4 2735.27   360.1 2736.41   382.9 2740.89   390.6 2742.99
#Mann= 6 ,-1,0
       0     .06       0      70     .05       0   155.9    .045       0
   175.8     .05       0     240     .06       0     330     .05       0
Bank Sta=155.9,175.8
XS Rating Curve= 0 ,0
Exp/Cntr(USF)=0,0
Exp/Cntr=0.3,0.1

Type RM Length L Ch R = 1 ,82526   ,231.7,229.5,227.5
XS GIS Cut Line= 2
 2312033.5241504544922.3642782982311768.93687016545057.770709951
#Sta/Elev= 30
       0 2687.68      12 2688.16      18 2687.97    23.7 2687.46    32.5 2686.42
    41.7 2684.97    50.9 2683.81    73.4 2680.06    86.3 2678.73   127.12678.922
   131.8 2677.53   133.9 2677.47   140.8 2677.91   149.12678.821   151.7 2679.31
   158.8 2681.92   167.8 2684.04   176.8 2685.49   190.6 2686.82   194.7 2687.73
   196.3 2688.26   202.2 2690.67   211.2 2694.86   226.2 2702.61   234.9  2707.7
   246.8 2713.36   270.6 2722.12   279.5 2725.62   285.5 2727.28   297.2 2731.01
#Mann= 3 ,-1,0
       0     .05       0   127.1    .045       0   149.1     .05       0
Bank Sta=127.1,149.1
XS Rating Curve= 0 ,0
Exp/Cntr(USF)=0,0
Exp/Cntr=0.3,0.1

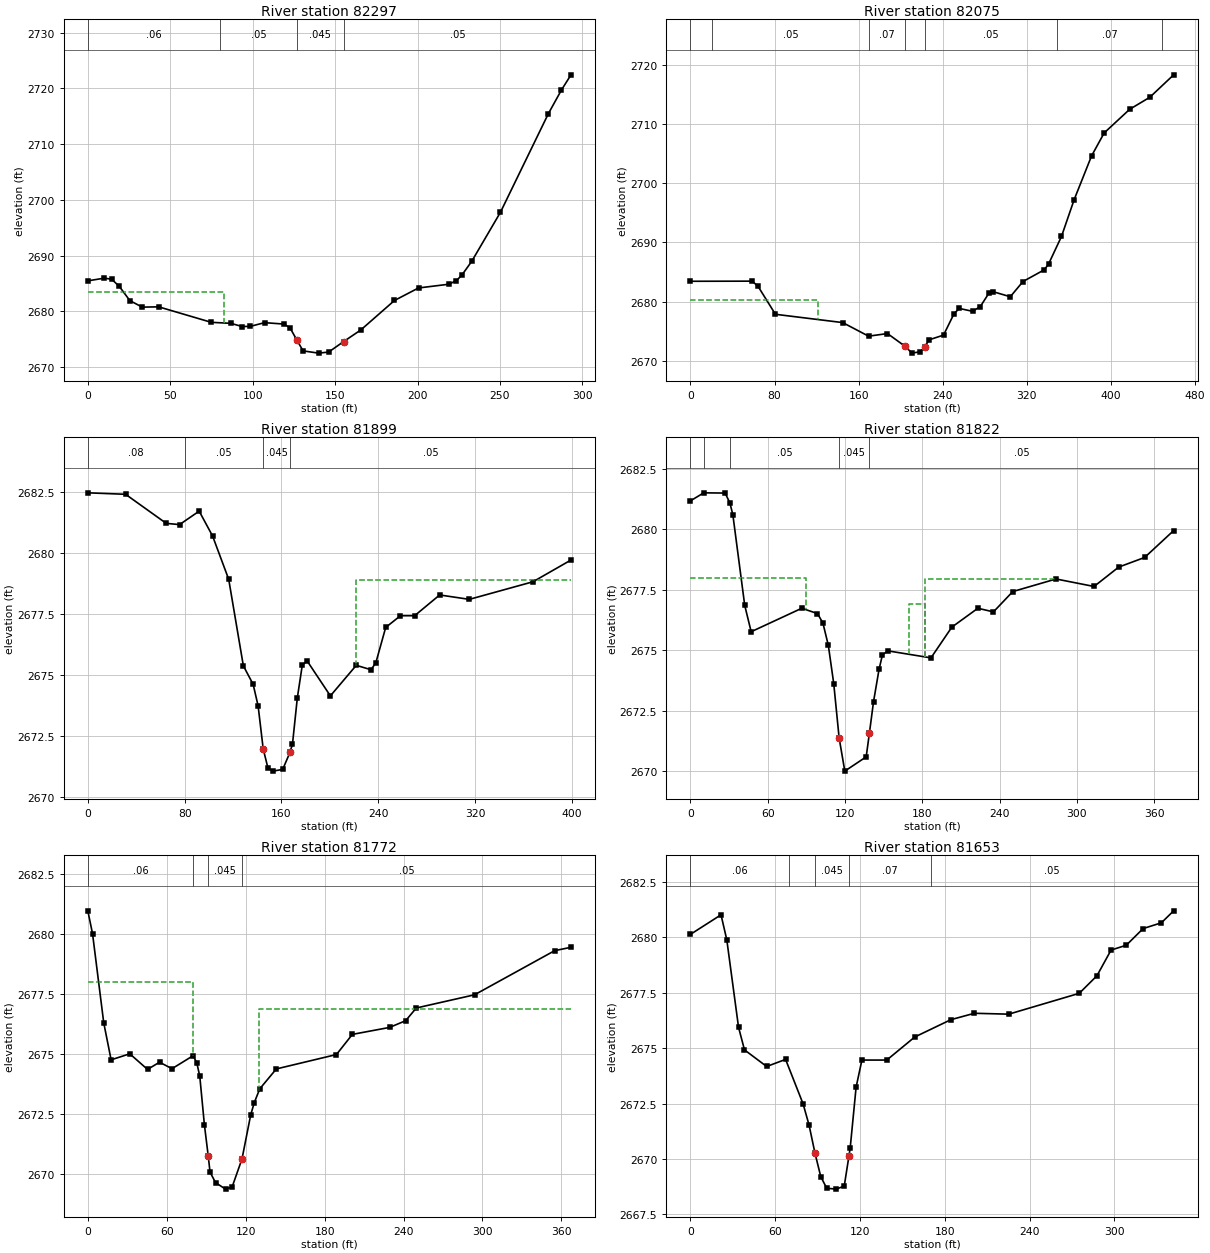
Type RM Length L Ch R = 1 ,82297   ,214.8,221.8,231.2
XS GIS Cut Line= 2
2311924.57644677544710.6944541052311672.44033266544860.108447653
#Sta/Elev= 30
       0 2685.46     9.8 2685.93    14.4 2685.77    19.1 2684.46    25.5 2681.91
      33 2680.74      43 2680.79    74.9 2678.01    86.8 2677.83    93.5 2677.26
    98.5 2677.28   107.2 2677.95   118.9  2677.7   122.6 2677.05  126.88 2674.78
   130.6 2672.88     140 2672.48   146.1 2672.67   155.2 2674.56   165.6 2676.64
     186 2681.93   200.6 2684.18     219 2684.85   223.6  2685.5   226.9 2686.49
   232.9 2688.97   250.3 2697.77   279.4 2715.49   287.3 2719.72   293.1 2722.45
#Mann= 4 ,-1,0
       0     .06       0      80     .05       0  126.88    .045       0
   155.2     .05       0
#XS Ineff= 2 , 0
           82.74  2683.4
Permanent Ineff=
       F       F
Bank Sta=126.88,155.2
XS Rating Curve= 0 ,0
Exp/Cntr(USF)=0,0
Exp/Cntr=0.3,0.1

Type RM Length L Ch R = 1 ,82075   ,175.1,176,177.5
XS GIS Cut Line= 3
2311873.21538649544561.2804605572311611.74089778544621.979895436
2311579.05658669544810.303783137
#Sta/Elev= 30
       0 2683.45    58.6 2683.47    64.1 2682.64    80.8 2677.88   144.8 2676.48
   169.4 2674.19   187.4 2674.63   204.1 2672.48   210.7 2671.33   218.7 2671.57
   222.8 2672.36   226.9 2673.57   240.7 2674.37   250.7 2677.98   255.7 2678.87
   268.4 2678.38   275.7 2679.19   283.9 2681.45   287.9 2681.69   304.2 2680.84
   316.3 2683.41   336.6 2685.39   340.7 2686.39   352.9 2691.01     365 2697.24
   381.5 2704.59   393.5 2708.47   417.8 2712.46   436.9 2714.48   459.6 2718.27
#Mann= 7 ,-1,0
       0     .07       0      20     .05       0     170     .07       0
   204.1    .045       0   222.8     .05       0  348.43     .07       0
  448.43     .05       0
#XS Ineff= 2 , 0
          121.31 2680.21
Permanent Ineff=
       F       F
Bank Sta=204.1,222.8
XS Rating Curve= 0 ,0
Exp/Cntr(USF)=0,0
Exp/Cntr=0.3,0.1

Type RM Length L Ch R = 1 ,81899   ,82.6,77.2,72.6
XS GIS Cut Line= 2
2311838.97467963544413.422862775 2311445.2065508544478.791484952
#Sta/Elev= 30
       0 2682.46    31.2  2682.4    64.8 2681.21    75.8 2681.16      92 2681.71
   103.1 2680.69   116.4 2678.92   128.5 2675.38   136.6 2674.62   140.7 2673.74
   144.92671.979   148.8  2671.2   152.9 2671.07     161 2671.14     1672671.834
   169.1 2672.18   173.1 2674.07   177.2 2675.41   181.2 2675.58   200.4 2674.15
   221.8  2675.4     234 2675.22     238 2675.51   246.1 2676.95   258.3 2677.43
     270 2677.43   290.7 2678.28   315.2  2678.1   367.8 2678.82   399.2 2679.71
#Mann= 4 ,-1,0
       0     .08       0      80     .05       0   144.9    .045       0
     167     .05       0
#XS Ineff= 2 , 0
                          221.47         2678.91
Permanent Ineff=
       F       F
Bank Sta=144.9,167
XS Rating Curve= 0 ,0
Exp/Cntr(USF)=0,0
Exp/Cntr=0.5,0.3

Type RM Length L Ch R = 1 ,81822   ,56.1,49.5,49.5
XS GIS Cut Line= 4
2311779.91568589544302.7288830962311701.62742246 544352.65183369
2311617.66609646544379.8825340142311425.91658168544409.382459365
#Sta/Elev= 30
       0 2681.17    10.3  2681.5    26.9 2681.49    30.6 2681.08    32.9 2680.59
    42.1 2676.85    47.1 2675.76    86.4 2676.73    98.6 2676.51   102.8 2676.12
     107  2675.2   111.2 2673.62   115.4 2671.37   119.8    2670   136.4 2670.59
   138.9 2671.57   142.1 2672.87   146.4 2674.21     149  2674.8   153.2 2674.97
   186.7 2674.68   202.9 2675.95   223.1 2676.73   235.2 2676.58   250.2 2677.42
   283.8 2677.94   313.3 2677.63   332.4 2678.43   352.6 2678.83   375.1 2679.94
#Mann= 5 ,-1,0
       0     .05       0    10.3      .1       0    30.6     .05       0
   115.4    .045       0   138.9     .05       0
#XS Ineff= 3 ,-1
       0      90    2678     170  181.89  2676.9  181.89  284.63 2677.94
Permanent Ineff=
       F       F       F
Bank Sta=115.4,138.9
XS Rating Curve= 0 ,0
Exp/Cntr(USF)=0,0
Exp/Cntr=0.5,0.3

Type RM Length L Ch R = 1 ,81772   ,111.7,119.7,120.7
XS GIS Cut Line= 4
2311728.85812278544252.8059325012311667.58904705544311.805783204
2311583.62772105544339.0364835282311391.87820627544368.536408879
#Sta/Elev= 30
       0 2680.98     3.6 2680.02    12.1 2676.31    17.7 2674.77    31.9 2675.02
    45.4 2674.37    54.5 2674.67      64  2674.4      80 2674.94    82.8 2674.65
    85.1 2674.09    88.6 2672.07   91.56 2670.75    92.9 2670.09    97.1 2669.65
   104.7 2669.38   109.7 2669.47   117.22670.639   123.8 2672.47   126.5 2672.98
   130.7 2673.56   143.3 2674.39     189 2674.99   201.1 2675.83   229.4 2676.12
   241.6  2676.4   249.7 2676.93     294 2677.48   354.9 2679.32   367.3 2679.46
#Mann= 4 ,-1,0
       0     .06       0      80     .05       0   91.56    .045       0
   117.2     .05       0
#XS Ineff= 2 , 0
              80    2678     130          2676.9
Permanent Ineff=
       F       F
Bank Sta=91.56,117.2
XS Rating Curve= 0 ,0
Exp/Cntr(USF)=0,0
Exp/Cntr=0.5,0.3

Type RM Length L Ch R = 1 ,81653   ,146.1,142.2,138.8
XS GIS Cut Line= 2
2311720.91583519544174.5176690692311391.87820627544267.555895177
#Sta/Elev= 30
       0 2680.13    21.6 2681.01    25.7 2679.88      34 2675.94    38.2 2674.92
    53.9 2674.17    67.3 2674.49    79.7 2672.48    83.9 2671.53    88.1 2670.26
    92.2  2669.2    96.4 2668.68   103.2 2668.64   108.8 2668.78   112.12670.119
     113 2670.49   117.2 2673.24   121.3 2674.46   138.9 2674.46   158.7  2675.5
   184.2 2676.28   200.9 2676.57   225.2 2676.53   275.1 2677.47   287.6 2678.26
   297.6 2679.42   308.4 2679.64   320.3 2680.39   333.2 2680.65   341.9 2681.19
#Mann= 5 ,-1,0
       0     .06       0      70     .07       0    88.1    .045       0
   112.1     .07       0     170     .05       0
Bank Sta=88.1,112.1
XS Rating Curve= 0 ,0
Exp/Cntr(USF)=0,0
Exp/Cntr=0.3,0.1

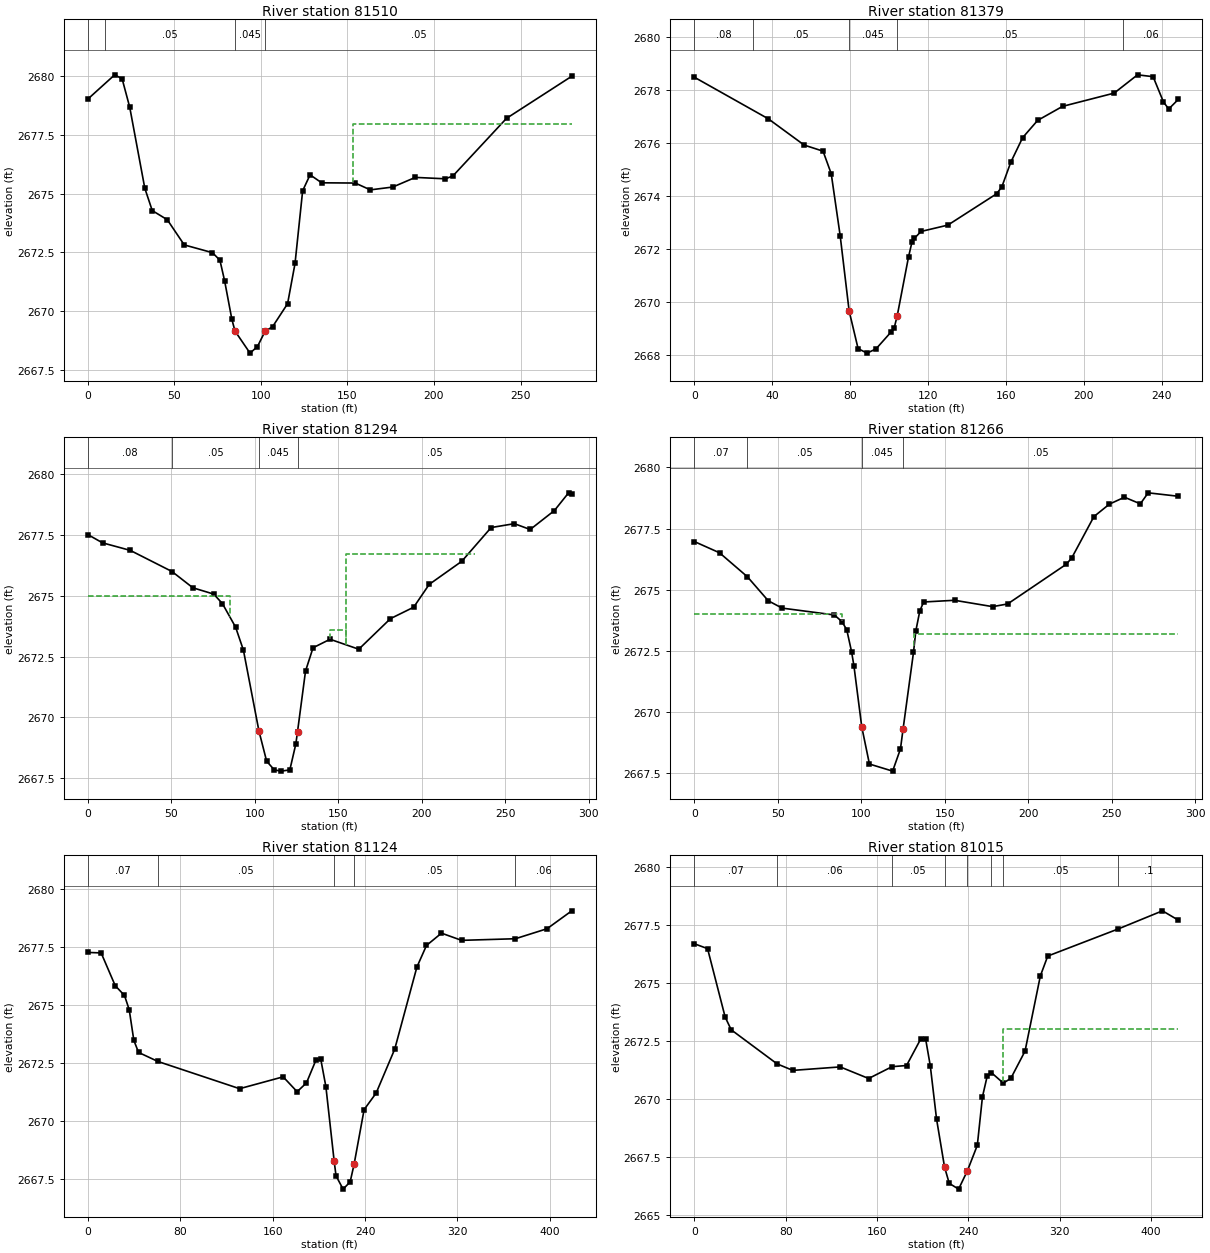
Type RM Length L Ch R = 1 ,81510   ,136.1,131.1,127
XS GIS Cut Line= 2
2311666.45443454544030.4218798542311408.89739397544139.344681151
#Sta/Elev= 30
       0 2679.02    15.5 2680.05    19.8 2679.88    24.2 2678.67    32.9 2675.23
    37.2 2674.28    45.9 2673.89    55.7 2672.82      72 2672.49    76.3 2672.17
      79  2671.3    83.2 2669.66      85 2669.16    93.7 2668.22      98  2668.5
   102.4 2669.15   106.7 2669.34   115.4 2670.32   119.7 2672.03   124.1 2675.12
   128.4  2675.8   135.1 2675.46   154.5 2675.45   163.2 2675.16   176.2 2675.28
   189.2 2675.69   206.6 2675.63   210.9 2675.75   241.9  2678.2   279.6 2679.99
#Mann= 4 ,-1,0
       0     .06       0      10     .05       0      85    .045       0
   102.4     .05       0
#XS Ineff= 2 , 0
                          153.21         2677.94
Permanent Ineff=
       F       F
Bank Sta=85,102.4
XS Rating Curve= 0 ,0
Exp/Cntr(USF)=0,0
Exp/Cntr=0.3,0.1

Type RM Length L Ch R = 1 ,81379   ,84.4,85,84.9
XS GIS Cut Line= 2
 2311613.1276464543899.9414408012311397.55126884544023.614204773
#Sta/Elev= 30
       0 2678.49      38 2676.92    56.4 2675.93    66.1  2675.7    70.3 2674.85
    74.9 2672.51    79.5 2669.67    84.1 2668.25    88.7 2668.08    93.3 2668.24
   101.2 2668.89   102.6 2669.02   104.2 2669.49     110 2671.71   111.8 2672.28
     113 2672.41   116.4 2672.67   130.2 2672.91   155.2 2674.09   157.9 2674.35
   162.5 2675.28   168.6 2676.21   176.3 2676.86   189.1 2677.39   215.6 2677.89
   227.6 2678.58   235.6 2678.51   240.9 2677.56   243.6 2677.29   248.5 2677.65
#Mann= 5 ,-1,0
       0     .08       0      30     .05       0    79.5    .045       0
   104.2     .05       0     220     .06       0
Bank Sta=79.5,104.2
XS Rating Curve= 0 ,0
Exp/Cntr(USF)=0,0
Exp/Cntr=0.5,0.3

Type RM Length L Ch R = 1 ,81294   ,27.5,28,28
XS GIS Cut Line= 3
2311604.58582077543829.688186326 2311525.3643919543852.777571663
2311346.49370573 543957.80667901
#Sta/Elev= 30
       0 2677.52     8.8 2677.18    25.4 2676.87    50.4    2676    62.9 2675.33
    75.4 2675.07    80.6 2674.68    88.5 2673.71    93.2 2672.76   102.5 2669.43
   107.1 2668.19   111.7 2667.83   115.8 2667.78     121 2667.83   124.6  2668.9
   125.6  2669.4   130.4  2671.9   134.9 2672.86   145.1 2673.21   162.3  2672.8
   181.3 2674.06   195.2 2674.53   204.5 2675.47     224 2676.42   241.6 2677.81
   255.5 2677.97     265 2677.73   279.5 2678.51     288 2679.24   289.9 2679.21
#Mann= 4 ,-1,0
       0     .08       0    50.4     .05       0   102.5    .045       0
   125.6     .05       0
#XS Ineff= 3 ,-1
       0      85    2675     145  154.74  2673.6  154.74  231.79 2676.71
Permanent Ineff=
       F       F       F
Bank Sta=102.5,125.6
XS Rating Curve= 0 ,0
Exp/Cntr(USF)=0,0
Minor Loss Coefficient=0
Exp/Cntr=0.5,0.3

Type RM Length L Ch R = 1 ,81266   ,138.5,142.4,146.3
XS GIS Cut Line= 3
2311590.69693189 543805.382630772311511.47550301543828.472016107
2311332.60481685543933.501123455
#Sta/Elev= 30
       0 2676.97    15.1 2676.51    31.8 2675.53    44.3 2674.55    52.6 2674.25
    83.9 2673.97    88.4  2673.7    91.3 2673.37    94.2 2672.47    95.6  2671.9
   100.3  2669.4   104.9 2667.88   118.8 2667.59   123.5  2668.5  125.08 2669.32
   131.3 2672.44   132.7 2673.32   135.1 2674.14   137.4  2674.5   155.9 2674.57
   178.7 2674.31   187.7 2674.42   222.8 2676.04   226.1  2676.3   239.4 2677.99
   248.7  2678.5   257.7 2678.78   267.2 2678.51   271.9 2678.96   289.9 2678.82
#Mann= 4 ,-1,0
       0     .07       0    31.8     .05       0   100.3    .045       0
  125.08     .05       0
#XS Ineff= 2 , 0
            88.3    2674   131.7          2673.2
Permanent Ineff=
       F       F
Bank Sta=100.3,125.08
XS Rating Curve= 0 ,0
Exp/Cntr(USF)=0,0
Minor Loss Coefficient=0
Exp/Cntr=0.5,0.3

Type RM Length L Ch R = 1 ,81124   ,93.1,108.4,129.2
XS GIS Cut Line= 3
2311619.58948312543746.4856455942311423.64735665543718.403438639
2311220.55171673 543805.76860218
#Sta/Elev= 30
       0 2677.26    11.5 2677.24    23.7 2675.83    31.7 2675.41    35.8  2674.8
    39.8 2673.48    43.9 2672.96    60.7 2672.57   131.4  2671.4   169.1 2671.91
   181.2 2671.27   189.3 2671.65   197.4 2672.62   201.7 2672.66   206.1 2671.49
   213.3 2668.27   214.9 2667.65     221 2667.08   227.1 2667.39   230.52668.141
   239.2  2670.5   249.6 2671.21   265.7  2673.1   284.9 2676.63   293.2 2677.56
   306.2 2678.09   323.6 2677.78   370.2 2677.85   397.6 2678.28     419 2679.05
#Mann= 5 ,-1,0
       0     .07       0    60.7     .05       0   213.3    .045       0
   230.5     .05       0   370.2     .06       0
Bank Sta=213.3,230.5
XS Rating Curve= 0 ,0
Exp/Cntr(USF)=0,0
Exp/Cntr=0.3,0.1

Type RM Length L Ch R = 1 ,81015   ,54.2,54.8,56
XS GIS Cut Line= 2
2311623.33915903543683.2304507212311214.87865416 543569.76919937
#Sta/Elev= 30
       0 2676.68    11.6 2676.47      27 2673.52    32.3 2672.97    72.5  2671.5
    86.3 2671.22   127.8 2671.37   152.7 2670.87   173.2 2671.38   185.9 2671.43
   198.4 2672.58   202.6 2672.58   206.7 2671.42   212.2 2669.12   219.2 2667.05
   223.3 2666.35   231.5  2666.1   239.32666.901   247.9 2667.99   252.4 2670.08
   256.5 2670.96   260.3 2671.12   270.7 2670.67   277.3 2670.88   289.7 2672.05
   303.1 2675.29   309.6 2676.15   371.4 2677.32   410.1  2678.1   423.9  2677.7
#Mann= 8 ,-1,0
       0     .07       0    72.5     .06       0   173.2     .05       0
   219.2    .045       0   239.3     .05       0   260.3     .07       0
   270.7     .05       0   371.4      .1       0
#XS Ineff= 2 , 0
             190  2671.6     270            2673
Permanent Ineff=
       F       F
Bank Sta=219.2,239.3
XS Rating Curve= 0 ,0
Exp/Cntr(USF)=0,0
Exp/Cntr=0.5,0.3

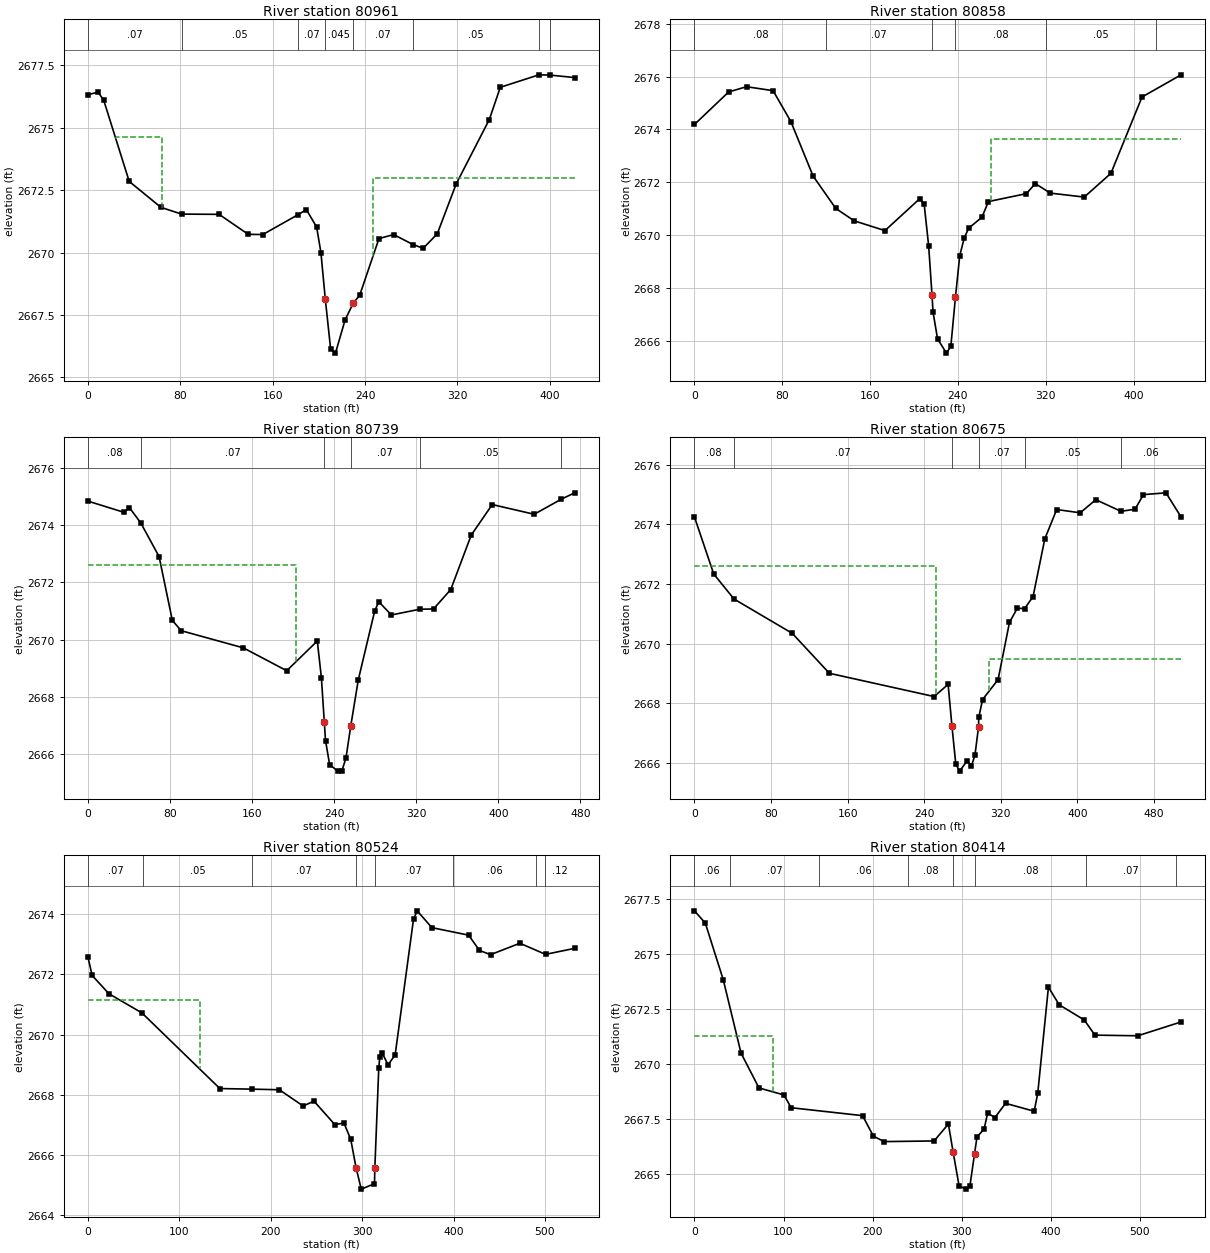
Type RM Length L Ch R = 1 ,80961   ,107.6,103,98.1
XS GIS Cut Line= 2
2311632.41605913 543637.845950182311230.76322935543509.634736154
#Sta/Elev= 30
       0 2676.33     8.7 2676.42    13.5 2676.12    35.7 2672.85    63.2 2671.81
    81.1 2671.54   113.6 2671.53   138.8 2670.73   151.4 2670.72   182.1 2671.52
   189.2 2671.72   198.1 2671.02   201.8    2670  205.63 2668.12   210.2 2666.14
   214.4 2665.97   222.8 2667.31   229.82667.972   235.4 2668.29   252.1 2670.56
   264.8 2670.72   281.6 2670.32   290.4 2670.17   302.6 2670.75     319 2672.75
   347.7 2675.33   357.2 2676.62   390.7 2677.12   400.2 2677.11   421.6 2677.01
#Mann= 8 ,-1,0
       0     .07       0    81.1     .05       0   182.1     .07       0
  205.63    .045       0   229.8     .07       0   281.6     .05       0
   390.7      .1       0   400.2     .06       0
#XS Ineff= 2 ,-1
   24.21   64.21 2674.62   246.7   421.6    2673
Permanent Ineff=
       F       F
Bank Sta=205.63,229.8
XS Rating Curve= 0 ,0
Exp/Cntr(USF)=0,0
Exp/Cntr=0.5,0.3

Type RM Length L Ch R = 1 ,80858   ,119.7,119,115.3
XS GIS Cut Line= 2
2311678.93517219543508.5001236412311240.97474197 543440.42337283
#Sta/Elev= 30
       0 2674.19    31.1 2675.42    47.4 2675.62    71.6 2675.47    87.8  2674.3
     108 2672.24   128.7 2671.01   145.5 2670.54   173.5 2670.17   205.2 2671.38
   209.2 2671.17   213.3 2669.59  216.35 2667.73   217.3 2667.08   221.4 2666.07
   229.5 2665.53   233.5 2665.79   237.72667.649   241.6 2669.22   245.7 2669.89
   249.7 2670.26   261.9 2670.68   267.7 2671.27   302.3 2671.57   310.4 2671.95
   324.1 2671.59     355 2671.44   379.3 2672.34   407.6 2675.23   443.2 2676.07
#Mann= 6 ,-1,0
       0     .08       0     120     .07       0  216.35    .045       0
   237.7     .08       0     320     .05       0     420     .06       0
#XS Ineff= 2 , 0
                           270.3         2673.63
Permanent Ineff=
       F       F
Bank Sta=216.35,237.7
XS Rating Curve= 0 ,0
Exp/Cntr(USF)=0,0
Exp/Cntr=0.5,0.3

Type RM Length L Ch R = 1 ,80739   ,64.4,63.6,65.1
XS GIS Cut Line= 4
2311668.72365957543435.8849227762311465.62801965543356.462046831
2311393.01281878543355.3274343172311213.74404165543315.615996344
#Sta/Elev= 30
       0 2674.84    34.9 2674.45    40.4 2674.61    51.4 2674.08    69.3  2672.9
    82.2 2670.67    90.8 2670.31   151.4 2669.71   193.7 2668.91   223.5 2669.95
   227.5 2668.66   230.32667.132   231.5 2666.47   235.5 2665.63   243.5  2665.4
   247.5 2665.41   251.5 2665.87   256.1 2666.98   263.5  2668.6   279.5 2671.01
   283.5 2671.32   295.7 2670.86   323.4 2671.06   336.8 2671.07   353.6 2671.75
   373.5 2673.65     394 2674.72   434.9 2674.38   460.9  2674.9   474.3 2675.13
#Mann= 6 ,-1,0
       0     .08       0    51.4     .07       0   230.3    .045       0
   256.1     .07       0   323.4     .05       0   460.9     .06       0
#XS Ineff= 2 , 0
           202.5  2672.6   277.5          2669.5
Permanent Ineff=
       F       F
Bank Sta=230.3,256.1
XS Rating Curve= 0 ,0
Exp/Cntr(USF)=0,0
Exp/Cntr=0.5,0.3

Type RM Length L Ch R = 1 ,80675   ,137.4,150.7,168
XS GIS Cut Line= 4
2311690.84860358543388.231197209 2311457.1184258543294.058358588
2311384.50322493543292.923746074 2311205.2344478543253.212308101
#Sta/Elev= 30
       0 2674.25    20.1 2672.34    41.3  2671.5   102.1 2670.35   140.9 2669.01
   250.3 2668.23   264.9 2668.64   268.9 2667.24   272.9 2665.97   276.9 2665.73
   284.9 2666.08   289.2  2665.9   292.9 2666.26  296.66 2667.21   296.9 2667.53
   300.9 2668.13   317.1  2668.8     329 2670.72   337.2 2671.19   344.8 2671.18
   353.6 2671.58   365.9 2673.52   378.3  2674.5   402.8 2674.39   419.2 2674.83
   445.4 2674.44   460.1 2674.51   468.9    2675   492.4 2675.06   508.2 2674.25
#Mann= 6 ,-1,0
       0     .08       0    41.3     .07       0   268.9    .045       0
  296.66     .07       0   344.8     .05       0   445.4     .06       0
#XS Ineff= 2 , 0
           252.5  2672.6   307.5          2669.5
Permanent Ineff=
       F       F
Bank Sta=268.9,296.66
XS Rating Curve= 0 ,0
Exp/Cntr(USF)=0,0
Exp/Cntr=0.5,0.3

Type RM Length L Ch R = 1 ,80524   ,126.3,110.7,96.9
XS GIS Cut Line= 3
2311707.30048502543315.6159963442311430.45503173 543136.34721921
2311228.49400432543119.328031508
#Sta/Elev= 30
       0 2672.57     4.5 2671.97    22.8 2671.36      59 2670.72   144.3  2668.2
     180 2668.18   209.4 2668.16   235.4 2667.62   247.3 2667.78   270.1    2667
   280.1 2667.05   287.5 2666.51   293.3 2665.57     299 2664.85   313.5 2665.03
   313.9 2665.56   318.2  2668.9   319.3 2669.24   322.2 2669.37   328.3 2668.99
   336.1 2669.32   356.2 2673.84   360.2 2674.12   376.3 2673.56   416.5 2673.31
   428.4  2672.8   440.5 2672.66   472.6 2673.04   500.7 2672.67   532.5 2672.87
#Mann= 8 ,-1,0
       0     .07       0      60     .05       0     180     .07       0
   293.3    .045       0   313.9     .07       0  399.82     .06       0
  489.82     .07       0  499.82     .12       0
#XS Ineff= 2 , 0
          122.53 2671.16
Permanent Ineff=
       F       F
Bank Sta=293.3,313.9
XS Rating Curve= 0 ,0
Exp/Cntr(USF)=0,0
Exp/Cntr=0.3,0.1

Type RM Length L Ch R = 1 ,80414   ,220.2,217.7,216.4
XS GIS Cut Line= 2
2311800.33871113543076.2127559942311255.72470465543034.232092995
#Sta/Elev= 30
       0 2676.97    12.2 2676.41    32.3 2673.84    52.3  2670.5    72.4 2668.92
   100.5  2668.6   108.5 2668.02   188.7 2667.66   200.8 2666.73   212.8 2666.48
     269 2666.51     285 2667.28  290.23 2666.03     297 2664.47   304.7 2664.32
   309.1 2664.44   314.42665.936   317.1 2666.69   325.1 2667.05   329.1 2667.78
   337.2 2667.57   349.2 2668.22   381.3 2667.86   385.3 2668.67   397.3  2673.5
   409.4  2672.7   437.5 2672.01   449.5 2671.32   497.6 2671.29   546.2 2671.92
#Mann= 8 ,-1,0
       0     .06       0      40     .07       0     140     .06       0
     240     .08       0  290.23    .045       0   314.4     .08       0
     440     .07       0     540     .12       0
#XS Ineff= 2 , 0
           88.42 2671.28
Permanent Ineff=
       F       F
Bank Sta=290.23,314.4
XS Rating Curve= 0 ,0
Exp/Cntr(USF)=0,0
Exp/Cntr=0.3,0.1

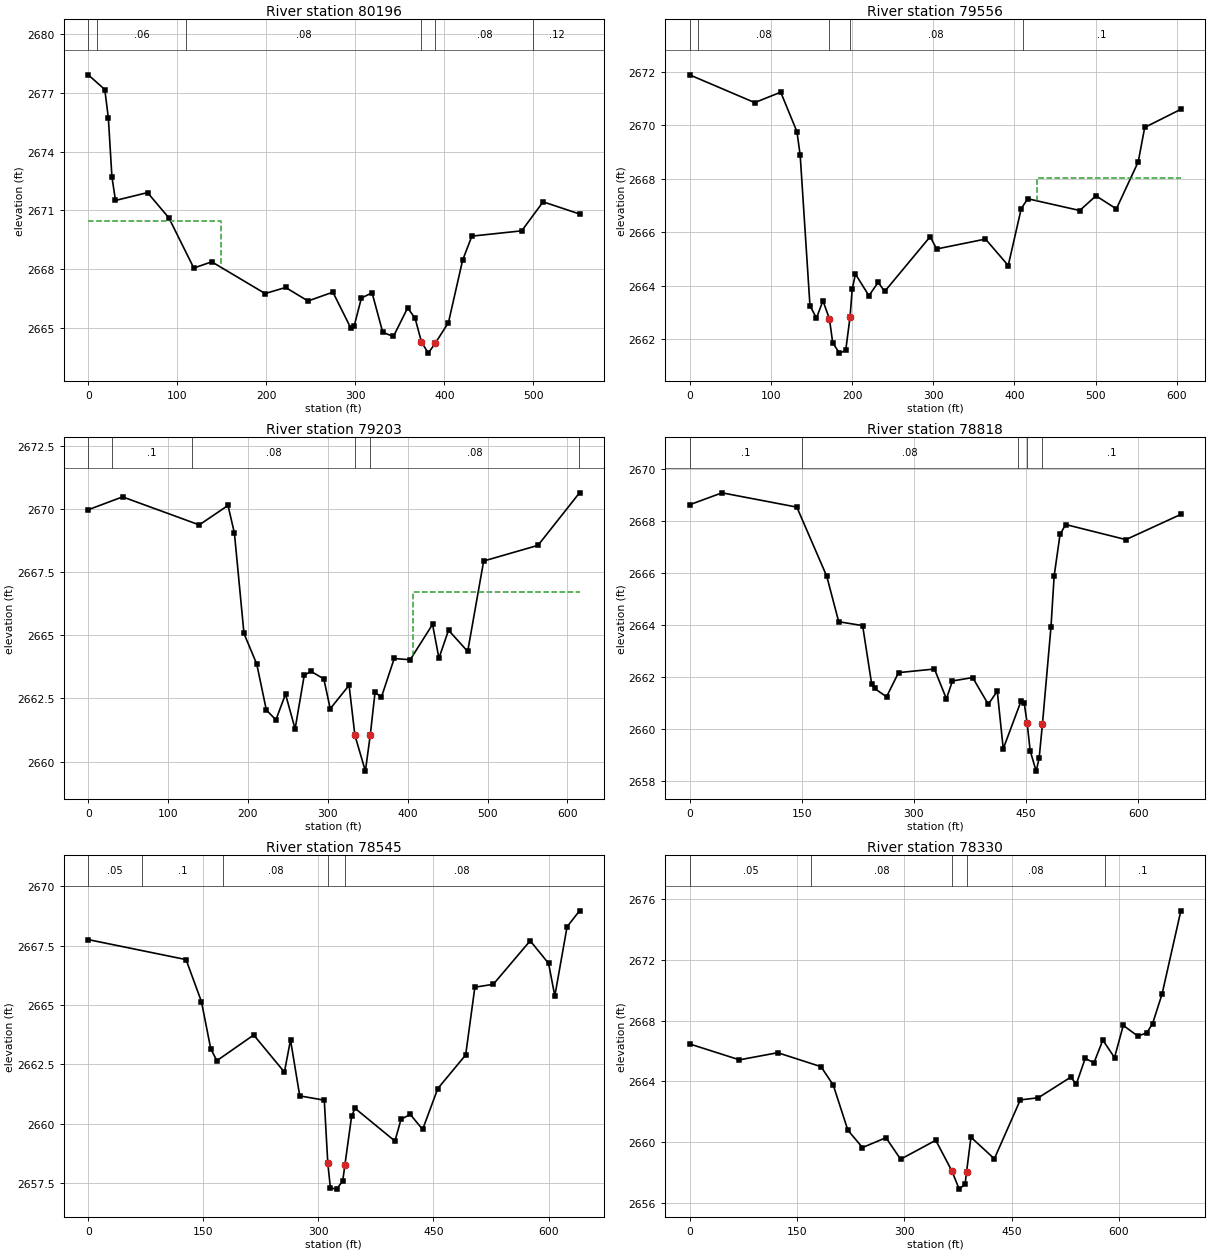
Type RM Length L Ch R = 1 ,80196   ,650.1,639.8,629.9
XS GIS Cut Line= 2
2311862.74239938542850.4248658062311311.32071781542830.001840563
#Sta/Elev= 30
       0 2677.92    18.6 2677.17    22.6 2675.72    26.6 2672.72    30.6 2671.51
    66.6 2671.91    90.6 2670.62   118.6 2668.06   138.7 2668.38   198.7 2666.76
   221.7 2667.07   246.8 2666.38   274.8 2666.83   294.8 2665.01   298.8 2665.12
   306.8 2666.53   318.8  2666.8   330.8 2664.78   342.8 2664.57   358.8 2666.03
   367.2 2665.49   374.2  2664.3   381.9 2663.72   389.82664.225   404.6 2665.28
   420.5 2668.46   430.9 2669.69   486.9 2669.96   510.9 2671.44   551.8 2670.82
#Mann= 6 ,-1,0
       0      .1       0      10     .06       0     110     .08       0
   374.2    .045       0   389.8     .08       0     500     .12       0
#XS Ineff= 2 , 0
          149.05 2670.44
Permanent Ineff=
       F       F
Bank Sta=374.2,389.8
XS Rating Curve= 0 ,0
Exp/Cntr(USF)=0,0
Exp/Cntr=0.3,0.1

Type RM Length L Ch R = 1 ,79556   ,247.5,353.2,347.8
XS GIS Cut Line= 2
2311868.41546194542554.2909997812311263.66699224542549.752549727
#Sta/Elev= 30
       0 2671.89    80.2 2670.85   112.2 2671.24   132.2 2669.76   136.2 2668.87
   148.2 2663.25   156.2 2662.78   164.2 2663.43   172.2 2662.75   176.2 2661.86
   184.5 2661.47   192.2 2661.57   197.52662.806   200.2 2663.86   204.2 2664.43
   220.8 2663.62   232.2 2664.12   240.2 2663.78   296.2 2665.83   304.2 2665.37
   364.3 2665.74   392.3 2664.75   408.3 2666.88   416.3 2667.25   480.3 2666.81
   500.3 2667.36   525.4 2666.87   552.3 2668.63   560.3 2669.92   604.8  2670.6
#Mann= 5 ,-1,0
       0     .06       0      10     .08       0   172.2    .045       0
   197.5     .08       0     410      .1       0
#XS Ineff= 2 , 0
                          427.37         2668.02
Permanent Ineff=
       F       F
Bank Sta=172.2,197.5
XS Rating Curve= 0 ,0
Exp/Cntr(USF)=0,0
Exp/Cntr=0.3,0.1

Type RM Length L Ch R = 1 ,79203   ,465.5,384.9,387.7
XS GIS Cut Line= 2
2311883.16542462542371.618385106 2311268.2054423542382.964510241
#Sta/Elev= 30
       0 2669.97      43 2670.48     139 2669.37     175 2670.14     183 2669.05
     195 2665.07     211 2663.86     223 2662.04     235 2661.65     247 2662.67
     259 2661.29   270.5 2663.42     279 2663.57     295 2663.27     303 2662.09
   326.6 2663.02  333.87 2661.04     347 2659.62   353.2 2661.07   359.1 2662.74
   367.1 2662.55   383.1 2664.08   403.1 2664.03   431.1 2665.43   439.1 2664.09
   451.1  2665.2   475.1 2664.36   495.1 2667.94   563.1 2668.56   615.1 2670.64
#Mann= 6 ,-1,0
       0     .06       0      30      .1       0     130     .08       0
  333.87    .045       0   353.2     .08       0  615.06      .1       0
#XS Ineff= 2 , 0
                          406.09          2666.7
Permanent Ineff=
       F       F
Bank Sta=333.87,353.2
XS Rating Curve= 0 ,0
Exp/Cntr(USF)=0,0
Exp/Cntr=0.3,0.1

Type RM Length L Ch R = 1 ,78818   ,275,272.7,274.4
XS GIS Cut Line= 2
2311903.58844986 542091.369094272311246.64780454 542072.08068154
#Sta/Elev= 30
       0 2668.62    43.4 2669.08   143.5 2668.53   183.5 2665.87   199.5 2664.12
   231.5 2663.97   243.5 2661.74   247.5 2661.55   263.5 2661.23   279.5 2662.16
   327.6  2662.3   343.6 2661.15   351.6 2661.84   378.7 2661.97   399.6 2660.94
   411.6 2661.45   419.6 2659.23   443.6 2661.08   447.6    2661   451.6 2660.21
   455.6 2659.16   463.6 2658.37   467.6 2658.86     472 2660.17   483.5 2663.93
   487.7 2665.88   495.6 2667.48   503.1 2667.86   583.7 2667.28   657.2 2668.25
#Mann= 5 ,-1,0
       0      .1       0     150     .08       0     440      .1       0
   451.6    .045       0     472      .1       0
Bank Sta=451.6,472
XS Rating Curve= 0 ,0
Exp/Cntr(USF)=0,0
Exp/Cntr=0.3,0.1

Type RM Length L Ch R = 1 ,78545   ,208.4,214.9,219.3
XS GIS Cut Line= 5
2311926.98960118541898.9608666042311762.18679297541881.948963821
2311666.49483982541881.9489638212311584.62505768541879.822475973
2311287.98000291541862.810573191
#Sta/Elev= 30
       0 2667.75   127.5 2666.91   147.6 2665.14   159.7 2663.16   167.7 2662.66
   215.7 2663.74   255.7 2662.18   263.7 2663.53   275.7 2661.18   307.7    2661
   312.3 2658.34   315.7 2657.31   323.7 2657.26   331.7  2657.6   334.6 2658.28
   343.3 2660.32   347.7 2660.66   399.8 2659.28   407.8  2660.2   419.8  2660.4
   435.9 2659.77   455.7 2661.49     492  2662.9     504 2665.75     528 2665.87
   576.1  2667.7   600.1 2666.75   608.2 2665.38   624.2 2668.29   640.4 2668.96
#Mann= 5 ,-1,0
       0     .05       0      70      .1       0  175.68     .08       0
   312.3    .045       0   334.6     .08       0
Bank Sta=312.3,334.6
XS Rating Curve= 0 ,0
Exp/Cntr(USF)=0,0
Exp/Cntr=0.3,0.1

Type RM Length L Ch R = 1 ,78330   ,178.9,177.5,175.1
XS GIS Cut Line= 2
2311924.26361122541755.9019944432311253.58154768541608.402367687
#Sta/Elev= 30
       0 2666.46    69.7 2665.41   123.2 2665.88   183.7 2664.96   200.8 2663.75
   221.3 2660.77   241.7 2659.63   274.5 2660.28     295 2658.86   344.1 2660.11
   366.5  2658.1   376.9 2656.89   385.1 2657.22   387.22658.035   393.3 2660.31
     426 2658.89   462.3 2662.77   487.5 2662.91   532.5 2664.26   540.7 2663.83
     553  2665.5   565.3 2665.22   577.6 2666.71     594 2665.56   606.2 2667.68
   626.7 2666.97     639 2667.19   647.2  2667.8   660.4 2669.74   686.7 2675.23
#Mann= 5 ,-1,0
       0     .05       0     170     .08       0   366.5    .045       0
   387.2     .08       0     580      .1       0
Bank Sta=366.5,387.2
XS Rating Curve= 0 ,0
Exp/Cntr(USF)=0,0
Exp/Cntr=0.3,0.1