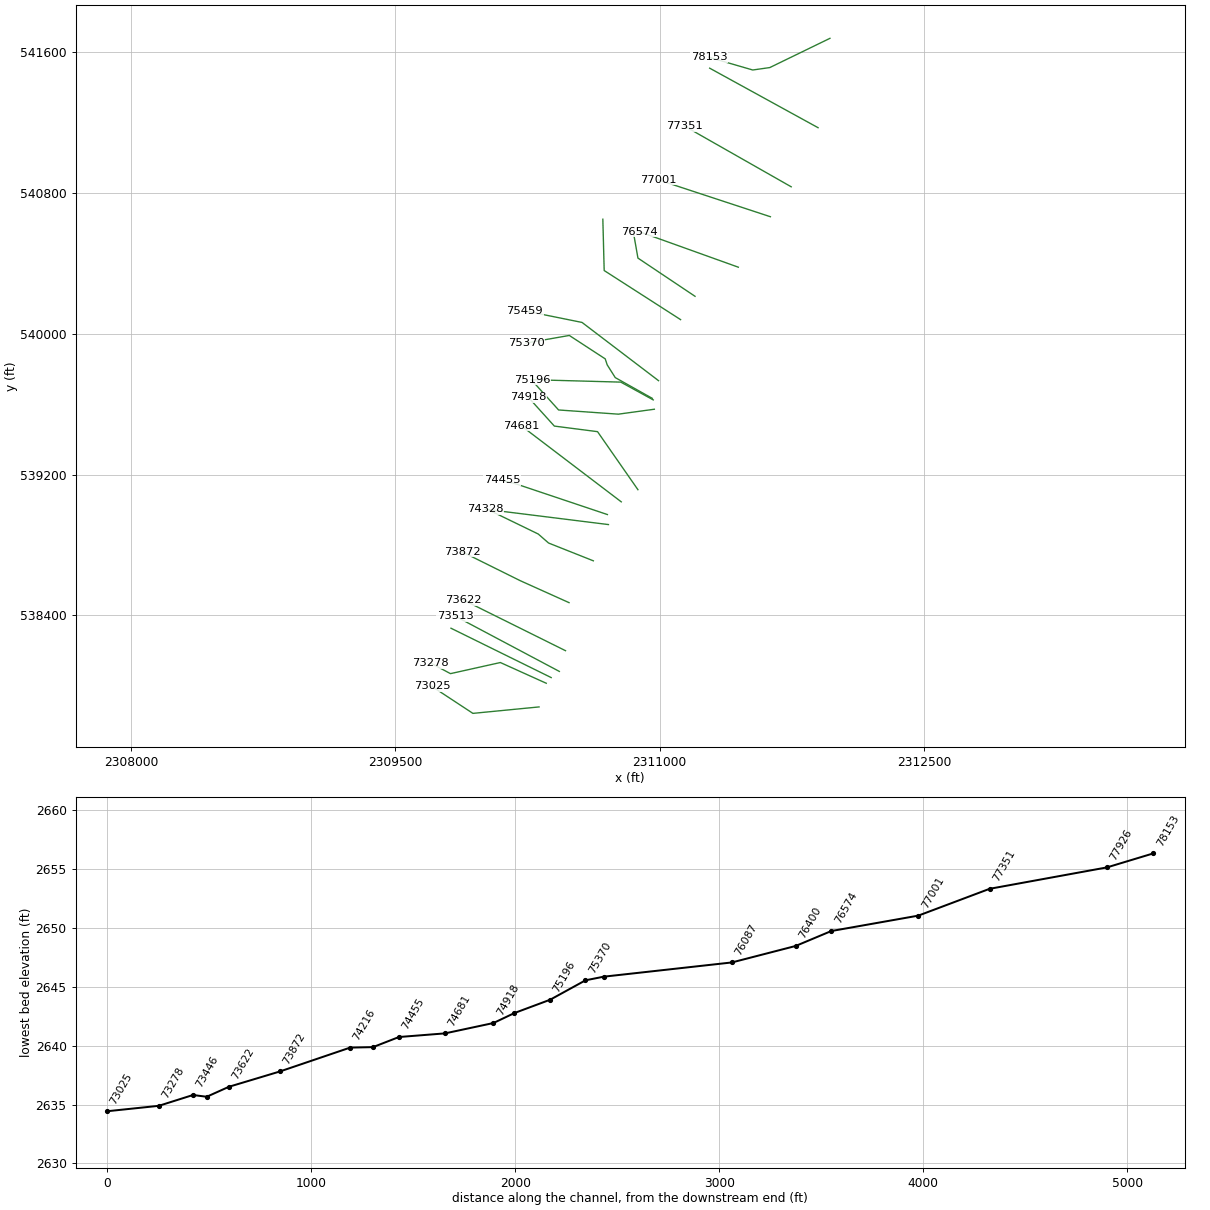
HEC-RAS study DEERCK.prj: DEERCK

--- DEERCK.g01 (geometry) --- (continued)

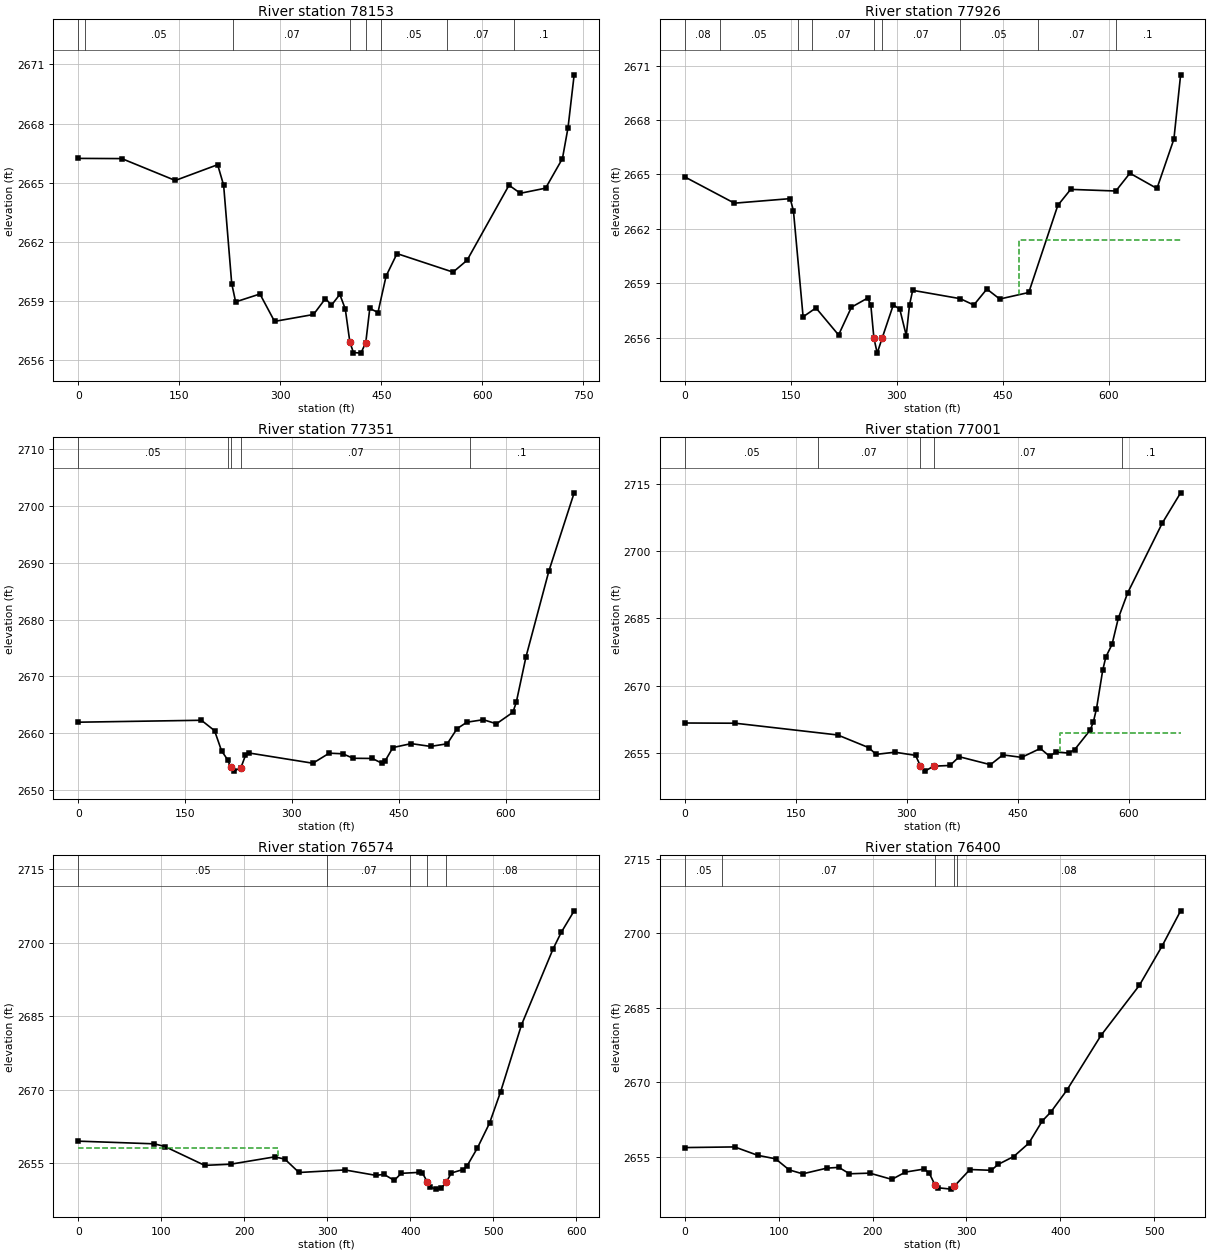
Type RM Length L Ch R = 1 ,78153   ,244.1,227.1,211.9
XS GIS Cut Line= 4
2311966.32962636541675.6796425822311625.02832679541509.813590451
2311528.27312971 541495.991419442311279.47405151541568.292006266
#Sta/Elev= 30
       0 2666.23    64.7 2666.22   144.1 2665.11     207 2665.91   215.9 2664.87
   227.9 2659.88   233.7 2658.95   269.8 2659.35   291.5 2657.96   349.3 2658.31
   367.1 2659.12     376 2658.78   388.4 2659.33   396.5 2658.59   403.3 2656.91
   408.6 2656.38   419.7 2656.35   426.9 2656.88   432.9 2658.62     445 2658.41
   457.1 2660.26   473.3  2661.4   556.5 2660.46   577.3 2661.06   639.6 2664.87
   656.4 2664.46   693.9 2664.72   718.9 2666.22   727.2 2667.79   736.3 2670.47
#Mann= 8 ,-1,0
       0     .06       0      10     .05       0     230     .07       0
   403.3    .045       0   426.9     .07       0  449.47     .05       0
  547.21     .07       0  647.21      .1       0
Bank Sta=403.3,426.9
XS Rating Curve= 0 ,0
Exp/Cntr(USF)=0,0
Exp/Cntr=0.3,0.1

Type RM Length L Ch R = 1 ,77926   ,571.1,575.2,568.4
XS GIS Cut Line= 2
2311899.04999981 541168.424848562311283.83788137541506.287241471
#Sta/Elev= 30
       0 2664.87    70.4 2663.42   149.3 2663.67   153.9 2663.01   167.6 2657.16
   185.8 2657.65   217.8 2656.16     236 2657.69   258.8 2658.19   263.4 2657.83
   267.8 2655.99   272.5 2655.16   279.52655.991   295.3 2657.82   304.5 2657.57
   313.6 2656.13   318.2 2657.82   322.7 2658.62     390 2658.16   409.2 2657.81
   427.7 2658.69   445.9 2658.14     487  2658.5   528.1  2663.3   546.3 2664.18
   610.2 2664.09   630.1 2665.07   668.4 2664.23   692.4 2666.95   701.9 2670.49
#Mann= 9 ,-1,0
       0     .08       0      50     .05       0     160     .08       0
     180     .07       0   267.8    .045       0   279.5     .07       0
     390     .05       0     500     .07       0     610      .1       0
#XS Ineff= 2 , 0
                          472.65         2661.41
Permanent Ineff=
       F       F
Bank Sta=267.8,279.5
XS Rating Curve= 0 ,0
Exp/Cntr(USF)=0,0
Exp/Cntr=0.3,0.1

Type RM Length L Ch R = 1 ,77351   ,322.2,349.4,344.9
XS GIS Cut Line= 2
2311746.50765077 540833.08381679 2311141.3809769541177.249612554
#Sta/Elev= 30
       0 2661.95   172.9 2662.29   191.4 2660.46   201.2 2656.92     210 2655.29
  213.99 2653.99   218.6 2653.34   228.52653.978   234.8 2656.11   239.4 2656.54
   329.4 2654.73   352.4  2656.5   371.4 2656.39     386  2655.6   412.8 2655.57
     426 2654.75   430.6 2655.09   441.8 2657.49   467.5 2658.18   494.6 2657.69
     518 2658.15   531.9 2660.82   545.7 2661.95   568.7 2662.39   587.1 2661.67
   610.1 2663.68   614.9 2665.42   628.5 2673.41   660.7 2688.54   696.2 2702.31
#Mann= 5 ,-1,0
       0     .05       0     210     .07       0  213.99    .045       0
   228.5     .07       0     550      .1       0
Bank Sta=213.99,228.5
XS Rating Curve= 0 ,0
Exp/Cntr(USF)=0,0
Exp/Cntr=0.3,0.1

Type RM Length L Ch R = 1 ,77001   ,418.2,426.7,412
XS GIS Cut Line= 2
2311628.40041554540663.2107885952310992.17827794540872.438202974
#Sta/Elev= 30
       0 2661.76    68.3 2661.71   206.6  2659.1   248.7 2656.27   258.4 2654.78
   283.8 2655.27   311.8 2654.56  318.05 2652.31   324.5 2651.06   336.1 2652.16
   358.2 2652.32   370.8 2654.26   412.9 2652.49   429.7 2654.67     455 2654.12
   480.3  2656.1   492.9 2654.34   501.3 2655.34   518.5 2655.07   526.6 2655.84
   547.6 2660.19   551.8 2661.95   556.1 2664.93   564.5 2673.49   568.7 2676.43
   577.1 2679.24   585.5 2685.02   598.2 2690.69     645 2706.22   669.7 2712.93
#Mann= 5 ,-1,0
       0     .05       0     180     .07       0  318.05    .045       0
   336.1     .07       0     590      .1       0
#XS Ineff= 2 , 0
                           506.3          2659.6
Permanent Ineff=
       F       F
Bank Sta=318.05,336.1
XS Rating Curve= 0 ,0
Exp/Cntr(USF)=0,0
Exp/Cntr=0.3,0.1

Type RM Length L Ch R = 1 ,76574   ,181.6,174.6,167
XS GIS Cut Line= 2
2311446.46567497540376.717450246 2310884.2021405540578.426341536
#Sta/Elev= 30
       0 2659.53    91.7 2658.98   104.4 2658.43   152.3 2654.59   183.6 2654.83
   236.7 2656.33   248.9 2655.86   265.9 2653.14   321.2 2653.66   358.7 2652.55
   368.1 2652.77   380.6 2651.53   389.1 2652.97   410.4 2653.16   414.6 2653.02
   420.5 2651.21   423.1 2650.24   430.6 2649.75   436.9 2649.88   443.1 2651.11
   449.4 2653.04   463.4 2653.74   468.2 2654.45   480.7 2658.11   495.4  2663.2
   508.8 2669.63   533.8 2683.19   571.9  2698.7   581.8  2702.1   597.3 2706.47
#Mann= 5 ,-1,0
       0     .05       0     300     .07       0     400     .08       0
   420.5    .045       0   443.1     .08       0
#XS Ineff= 2 , 0
          240.38 2658.12
Permanent Ineff=
       F       F
Bank Sta=420.5,443.1
XS Rating Curve= 0 ,0
Exp/Cntr(USF)=0,0
Exp/Cntr=0.3,0.1

Type RM Length L Ch R = 1 ,76400   ,285.9,312.5,280.7
XS GIS Cut Line= 3
2311200.63296371540211.5682955022310876.63805708540428.405353639
2310852.68512624 540564.55885526
#Sta/Elev= 30
       0 2656.85    53.2 2656.98    77.6  2655.3    96.8 2654.58   111.3 2652.35
   125.7 2651.56   151.4 2652.71   164.2 2652.86   175.5 2651.57   197.1  2651.7
   220.6 2650.44     235 2651.91   255.2 2652.53   260.5 2651.66   266.8 2649.22
   270.1 2648.75   283.4 2648.48   287.22649.086   303.8 2652.43   326.5 2652.27
   333.7 2653.45   350.4 2655.05   366.4 2657.72   380.8 2662.21   389.9    2664
   406.9 2668.39   443.4 2679.46   484.1  2689.5   508.4 2697.45   528.1 2704.53
#Mann= 5 ,-1,0
       0     .05       0      40     .07       0   266.8    .045       0
   287.2     .07       0     290     .08       0
Bank Sta=266.8,287.2
XS Rating Curve= 0 ,0
Exp/Cntr(USF)=0,0
Exp/Cntr=0.3,0.1

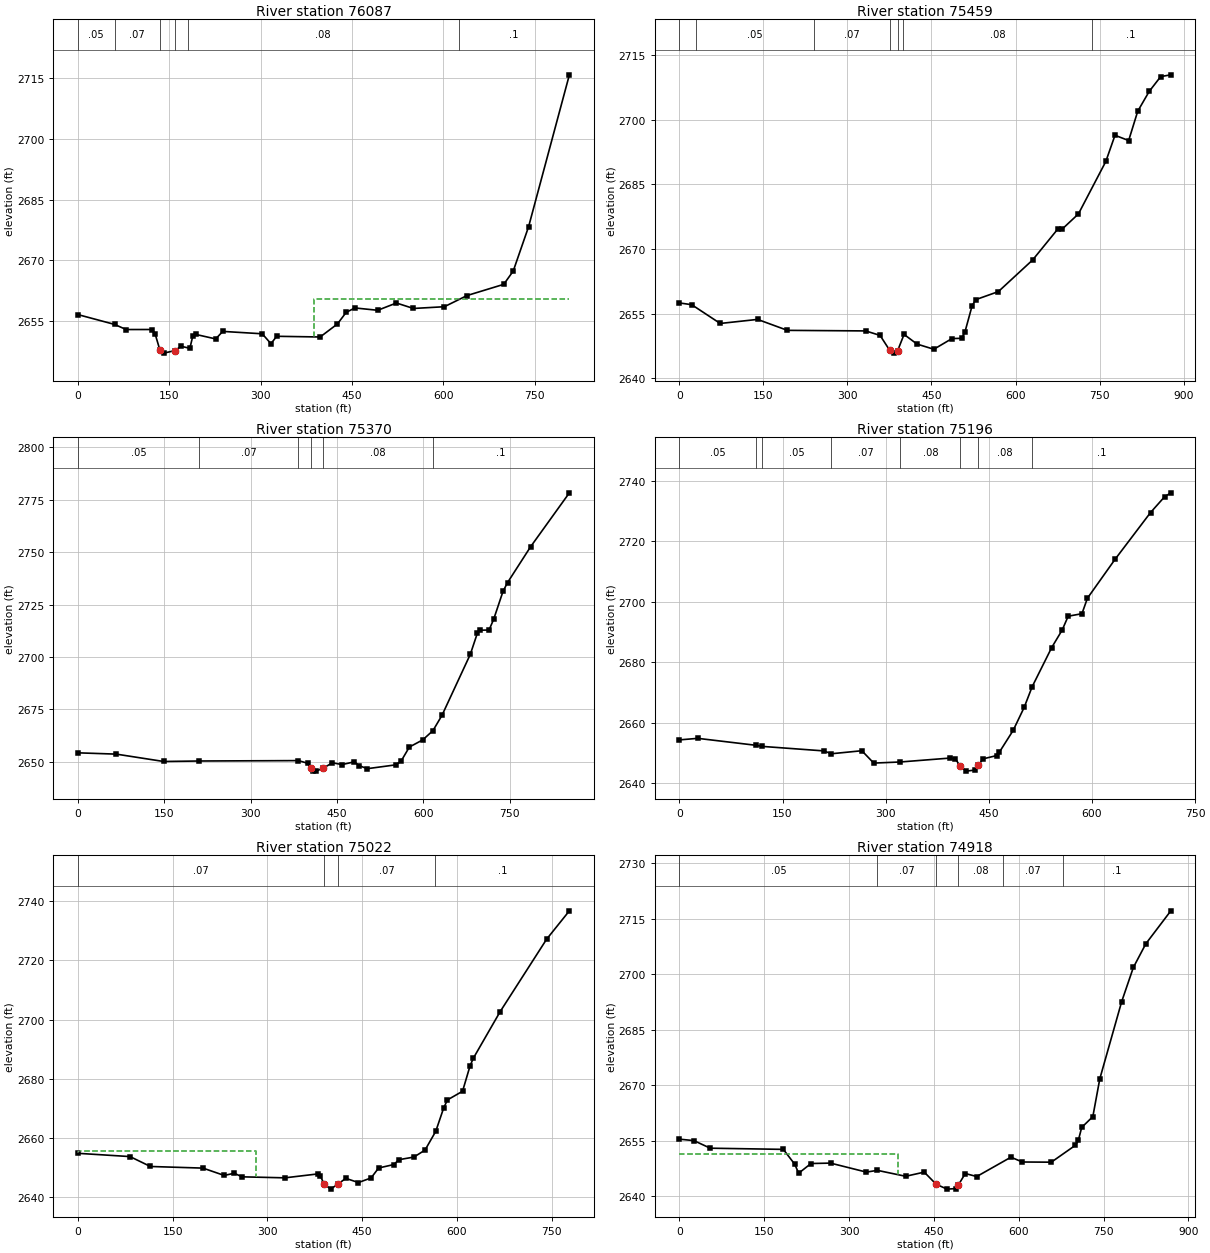
Type RM Length L Ch R = 1 ,76087   ,618,628.2,627.3
XS GIS Cut Line= 3
2311118.68872663540079.1968355932310685.01461035540357.807241687
2310677.45052693540649.024453488
#Sta/Elev= 30
       0  2656.6      60 2654.18    79.1 2652.91   122.1 2652.92   126.6 2651.85
   134.7 2647.74   140.9 2647.08   158.72647.688   169.4 2648.77   183.7 2648.27
   188.4 2651.25   193.2 2651.71   226.1 2650.59   237.7 2652.45   302.5 2651.86
   316.8 2649.42   326.3 2651.24   397.6 2651.07   425.9 2654.28   440.3 2657.15
   454.6 2658.25   492.1 2657.67   522.8 2659.47   550.8 2658.12   601.5 2658.55
   638.9 2661.32     699 2664.08   714.6 2667.36   739.9 2678.36   806.8 2715.87
#Mann= 6 ,-1,0
       0     .05       0      60     .07       0   134.7    .045       0
   158.7     .07       0     180     .08       0  625.46      .1       0
#XS Ineff= 2 , 0
                          387.37         2660.55
Permanent Ineff=
       F       F
Bank Sta=134.7,158.7
XS Rating Curve= 0 ,0
Exp/Cntr(USF)=0,0
Exp/Cntr=0.3,0.1

Type RM Length L Ch R = 1 ,75459   ,88.4,89.6,91.7
XS GIS Cut Line= 3
 2310993.6011989539732.6497543062310559.36678015540063.228215032
2310234.39134419540129.063755939
#Sta/Elev= 30
       0 2657.51    21.9  2657.1    72.8 2652.75   139.5 2653.69   192.8 2651.15
   332.5 2651.02   358.2 2649.98   375.3 2646.54   383.9 2645.87   389.6 2646.45
     401 2650.21   424.1 2647.97   454.2 2646.77   486.6 2649.25   503.7  2649.3
   509.5 2650.68   522.6  2656.9   529.2 2658.28   569.4 2660.14   630.6 2667.48
   675.5 2674.65   683.7 2674.68   712.3 2678.15   761.2 2690.31   777.6 2696.39
     802 2695.17   818.2 2701.97   838.6 2706.55   859.2    2710   877.3 2710.41
#Mann= 7 ,-1,0
       0     .03       0      30     .05       0     240     .07       0
   375.3    .045       0   389.6     .07       0     400     .08       0
  735.75      .1       0
Bank Sta=375.3,389.6
XS Rating Curve= 0 ,0
Exp/Cntr(USF)=0,0
Exp/Cntr=0.3,0.1

Type RM Length L Ch R = 1 ,75370   ,156.3,173.2,195
XS GIS Cut Line= 6
2310958.02945377 539632.361608522310747.86102508539750.106571584
 2310702.2823297539822.2728392682310690.88765585539856.456860803
2310487.04960151539989.3947223272310242.69715129 539946.34817669
#Sta/Elev= 30
       0 2654.29    66.6 2653.67   148.8 2650.16   210.6 2650.39   382.9 2650.58
     399 2649.33   405.2 2647.01   408.5 2645.73   413.3 2645.56   425.5 2646.85
   441.9 2649.54   458.8 2648.69   480.4    2650   488.1 2648.22   502.7 2646.73
   551.8 2648.54   561.3 2650.28   575.8 2657.06   598.9 2660.44   616.7 2664.86
   632.5 2672.19   681.7  2701.3   693.9 2711.35   697.9 2712.77   714.2 2712.88
   722.2 2717.94   738.5 2731.33   746.4 2735.52   786.4 2752.59   853.8 2778.32
#Mann= 6 ,-1,0
       0     .05       0   210.6     .07       0   382.9     .08       0
   405.2    .045       0   425.5     .08       0   616.7      .1       0
Bank Sta=405.2,425.5
XS Rating Curve= 0 ,0
Exp/Cntr(USF)=0,0
Exp/Cntr=0.3,0.1

Type RM Length L Ch R = 1 ,75196   ,176.3,174.8,173.5
XS GIS Cut Line= 3
2310963.59605878539623.458112396  2310779.262808539724.519354734
2310275.01327368539738.252779064
#Sta/Elev= 30
       0 2654.25    26.7 2654.76   111.7 2652.45   120.1  2652.1   210.2  2650.6
   220.9 2649.66   265.3 2650.66   282.6 2646.57   321.3 2646.94   393.4 2648.23
   401.4 2647.97   408.6 2645.45   417.4 2643.91   429.4 2644.25   434.8 2645.79
   441.4 2647.96   461.4 2649.06   465.4 2650.22   485.4  2657.4   501.4 2665.02
     513 2671.85   541.4 2684.81   556.7 2690.63   565.4 2695.19   585.4 2696.02
   593.4 2701.15   633.5    2714   685.2 2729.51   705.5  2734.7   714.7 2736.03
#Mann= 8 ,-1,0
       0     .05       0   111.7     .07       0   120.1     .05       0
   220.9     .07       0   321.3     .08       0   408.6    .045       0
   434.8     .08       0     513      .1       0
Bank Sta=408.6,434.8
XS Rating Curve= 0 ,0
Exp/Cntr(USF)=0,0
Exp/Cntr=0.3,0.1

Type RM Length L Ch R = 1 ,75022   ,107.6,103.1,101.2
XS GIS Cut Line= 4
2310969.78834368539570.6431539452310765.27794001539542.628030155
2310426.29494215539566.4408853762310270.81100511539738.733896687
#Sta/Elev= 30
       0 2654.86    82.4 2653.76   114.7 2650.42     198 2649.87   231.6  2647.4
   247.6 2648.14   259.7 2646.93   327.8 2646.59   379.9 2647.91     384 2647.13
   389.7 2644.59     400 2642.78   412.2 2644.53   424.1 2646.42   444.1    2645
   464.2 2646.55   476.2 2649.91   500.2 2651.07   508.3 2652.71   532.1  2653.6
   549.7 2655.96   566.7  2662.3   579.3 2670.22   585.2 2672.88   609.1  2675.8
     621 2684.37   626.1 2686.91   668.6 2702.64   742.3 2727.11   778.3 2736.67
#Mann= 4 ,-1,0
       0     .07       0   389.7    .045       0   412.2     .07       0
  566.24      .1       0
#XS Ineff= 2 , 0
          281.26 2655.61
Permanent Ineff=
       F       F
Bank Sta=389.7,412.2
XS Rating Curve= 0 ,0
Exp/Cntr(USF)=0,0
Exp/Cntr=0.3,0.1

Type RM Length L Ch R = 1 ,74918   ,255.9,237,219.5
XS GIS Cut Line= 4
 2310876.6161386539113.8765155462310647.30415761539443.347752601
2310402.17755724539474.9769913582310254.57444304539638.394724937
#Sta/Elev= 30
       0 2655.43    25.7 2655.03    54.4 2652.99   183.7 2652.67   203.8 2648.66
   210.8 2646.23   232.6 2648.85   267.1 2648.96   330.5 2646.53     350    2647
   399.9  2645.4   432.8 2646.52   453.9 2643.25   473.1 2641.93   489.3 2642.08
   493.3 2643.09   505.4 2646.15   525.6 2645.33   586.1 2650.56   606.2 2649.26
   657.5 2649.21   700.1 2653.78   705.3 2655.13   711.2  2658.6   730.9 2661.52
   743.2 2671.73   781.8 2692.55   802.5 2701.81   824.6 2708.22   868.8 2717.12
#Mann= 6 ,-1,0
       0     .05       0     350     .07       0   453.9    .045       0
   493.3     .08       0  571.42     .07       0  678.58      .1       0
#XS Ineff= 2 , 0
          385.68  2651.5
Permanent Ineff=
       F       F
Bank Sta=453.9,493.3
XS Rating Curve= 0 ,0
Exp/Cntr(USF)=0,0
Exp/Cntr=0.3,0.1

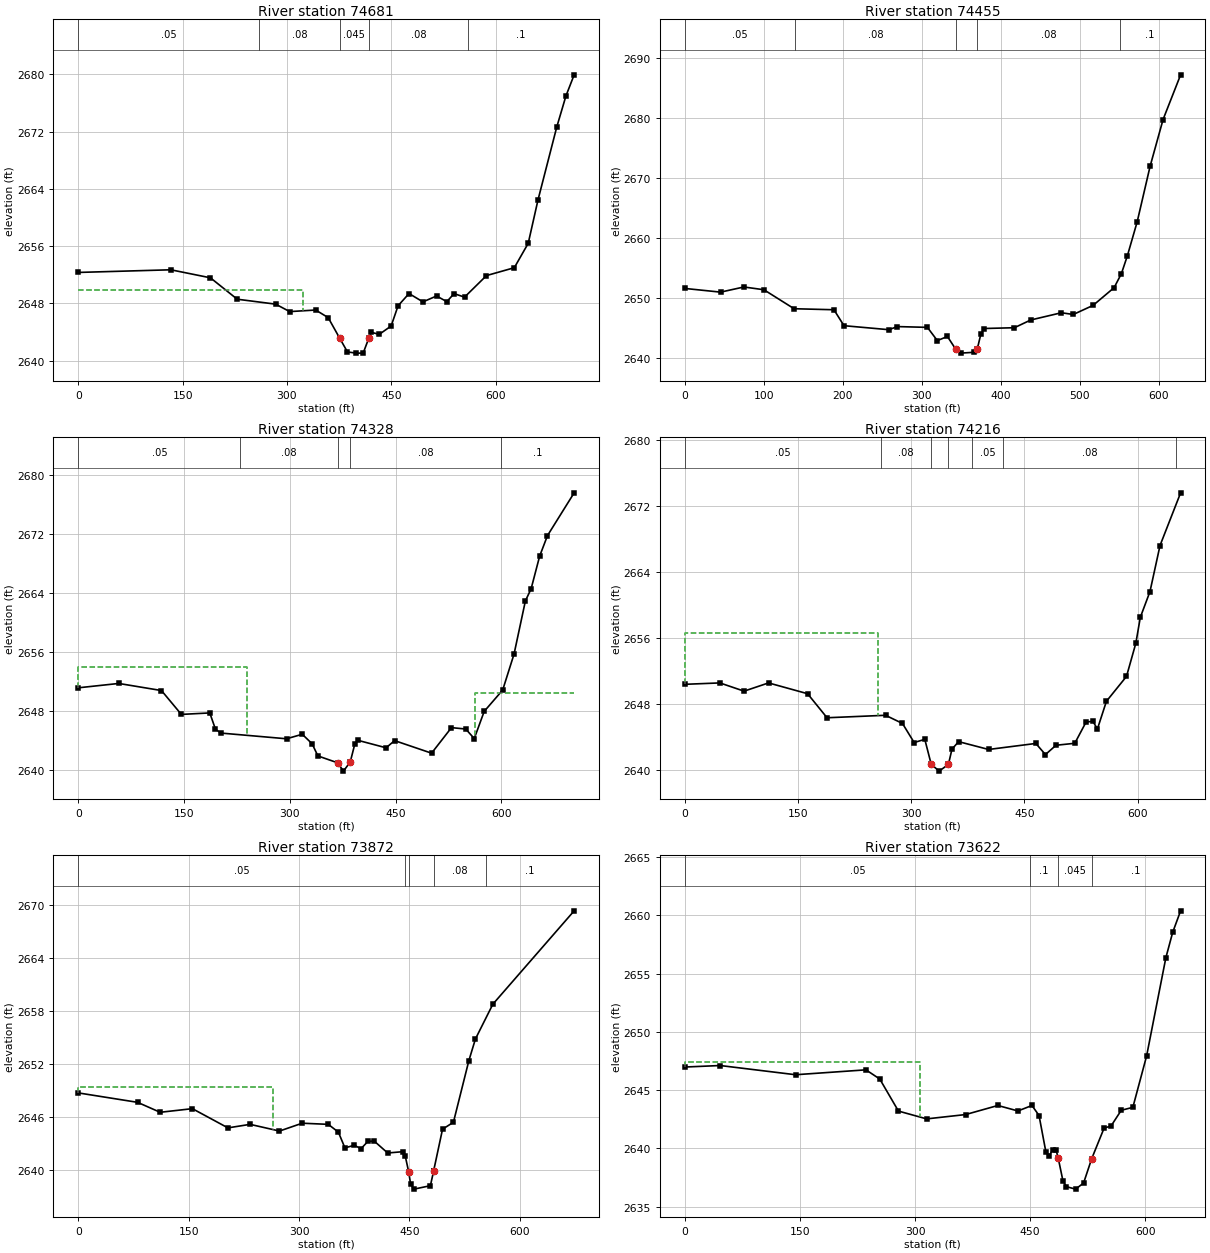
Type RM Length L Ch R = 1 ,74681   ,215.7,226.1,238.3
XS GIS Cut Line= 2
2310782.08701429539044.8784652542310214.78075753539476.311371625
#Sta/Elev= 30
       0 2652.32   133.1 2652.69     190 2651.57   228.5 2648.58   283.8 2647.89
   303.9 2646.85   341.3 2647.07   359.2 2646.01   375.5 2643.18   386.9 2641.22
   399.4 2641.05   409.5 2641.05   417.72643.164   421.2 2643.96   432.6 2643.67
   449.7 2644.84   459.7 2647.67   475.4 2649.37   495.4 2648.21     515 2649.03
   529.7 2648.24   540.1 2649.36   555.2 2648.87   586.7 2651.88   626.7 2652.98
   646.7 2656.39   660.7 2662.43   687.7 2672.63   700.9 2676.97   712.7 2679.92
#Mann= 5 ,-1,0
       0     .05       0     260     .08       0   375.5    .045       0
   417.7     .08       0     560      .1       0
#XS Ineff= 2 , 0
          323.08 2649.82
Permanent Ineff=
       F       F
Bank Sta=375.5,417.7
XS Rating Curve= 0 ,0
Exp/Cntr(USF)=0,0
Exp/Cntr=0.3,0.1

Type RM Length L Ch R = 1 ,74455   ,122.5,127.4,134.4
XS GIS Cut Line= 3
2310703.19584475538972.9135879892310180.07983419539148.348835435
2310106.71600344539166.423982142
#Sta/Elev= 30
       0 2651.54    45.4 2650.92    74.9 2651.78   100.2 2651.32   138.4 2648.15
   188.8 2647.98   201.5 2645.32   258.3 2644.65     269 2645.17     307 2645.04
   319.6 2642.83   332.3 2643.52  342.56 2641.45   349.1 2640.74     366 2640.88
   370.2 2641.48   374.5 2643.86   378.7 2644.85     417 2644.98   437.7 2646.27
   476.5 2647.48   491.5 2647.19   516.6 2648.71   543.2 2651.67   552.4 2654.01
   559.9 2656.96   572.4 2662.68   588.7 2671.93   605.1 2679.73   627.3 2687.19
#Mann= 5 ,-1,0
       0     .05       0     140     .08       0  342.56    .045       0
   370.2     .08       0     550      .1       0
Bank Sta=342.56,370.2
XS Rating Curve= 0 ,0
Exp/Cntr(USF)=0,0
Exp/Cntr=0.3,0.1

Type RM Length L Ch R = 1 ,74328   ,125.9,111.9,96
XS GIS Cut Line= 2
2310709.24769243538916.0088958182310011.67111005539002.855779568
#Sta/Elev= 30
       0 2651.16    57.5 2651.75     118 2650.79   146.2 2647.56   186.5 2647.76
   194.6 2645.54   202.6 2645.03   295.3 2644.26   317.6 2644.87   331.6 2643.58
   339.7 2641.94   367.9    2641     376 2639.88   385.6 2641.12   392.1 2643.55
   396.1 2644.06   436.4 2643.04   448.5 2644.01   500.9 2642.31   529.1 2645.77
   549.3 2645.58   561.4 2644.29   575.5 2647.97   601.7 2650.86   617.8 2655.73
   633.9 2662.93     642 2664.57   654.1 2668.99   665.2 2671.77     703 2677.56
#Mann= 5 ,-1,0
       0     .05       0     230     .08       0   367.9    .045       0
   385.6     .08       0     600      .1       0
#XS Ineff= 2 , 0
          239.16 2654.01  562.53         2650.45
Permanent Ineff=
       F       F
Bank Sta=367.9,385.6
XS Rating Curve= 0 ,0
Exp/Cntr(USF)=0,0
Exp/Cntr=0.3,0.1

Type RM Length L Ch R = 1 ,74216   ,327.7,344.5,347.9
XS GIS Cut Line= 4
2310623.45255046538710.2923387822310369.33725264538811.300511554
2310310.85883683538862.3362199022310035.66861704538995.942474289
#Sta/Elev= 30
       0 2650.38    46.6 2650.55    78.7 2649.55   111.1 2650.55   162.8 2649.24
   188.6 2646.32   266.1 2646.62   288.5 2645.63     304 2643.31   318.1  2643.7
   326.6 2640.67   337.1 2639.84   349.4 2640.66   354.1 2642.51   362.9 2643.42
   402.6 2642.47   465.2  2643.2   477.9 2641.85   491.9 2642.98   516.8 2643.22
   531.8 2645.81   540.8 2645.88   546.8 2644.96   558.7 2648.32   585.3 2651.34
   597.7 2655.38   603.6 2658.51   616.4 2661.64   629.7 2667.23     657 2673.63
#Mann= 7 ,-1,0
       0     .05       0     260     .08       0   326.6    .045       0
   349.4     .08       0  381.07     .05       0  421.07     .08       0
  651.07      .1       0
#XS Ineff= 2 , 0
          255.81 2656.61
Permanent Ineff=
       F       F
Bank Sta=326.6,349.4
XS Rating Curve= 0 ,0
Exp/Cntr(USF)=0,0
Exp/Cntr=0.3,0.1

Type RM Length L Ch R = 1 ,73872   ,249.3,249.6,248.6
XS GIS Cut Line= 3
2310485.63216763538472.8279934122310208.52083993538597.549313715
2309877.19851586538761.925714972
#Sta/Elev= 30
       0 2648.73    80.6 2647.66   111.3 2646.53   155.1 2646.94   203.4 2644.76
   233.5 2645.16   273.4  2644.4   304.3 2645.29   339.7 2645.16   353.4 2644.28
   362.3 2642.49   375.1 2642.79   384.1 2642.39   393.4 2643.22   402.1 2643.26
   420.4 2641.91   441.2 2642.06   444.1 2641.62  448.85  2639.8   451.6 2638.36
   456.1 2637.81   478.4  2638.2   482.9 2639.89   482.9 2639.92   494.9 2644.61
   509.7  2645.4   530.7  2652.4   539.6 2654.85   563.3  2658.8   673.7 2669.39
#Mann= 5 ,-1,0
       0     .05       0  443.89     .08       0  448.85    .045       0
   482.9     .08       0  553.89      .1       0
#XS Ineff= 2 , 0
          265.12 2649.43
Permanent Ineff=
       F       F
Bank Sta=448.85,482.9
XS Rating Curve= 0 ,0
Exp/Cntr(USF)=0,0
Exp/Cntr=0.3,0.1

Type RM Length L Ch R = 1 ,73622   ,110.2,109,108.3
XS GIS Cut Line= 2
2310465.51611546538200.2224829762309887.00380919538487.377501827
#Sta/Elev= 30
       0 2646.99    46.2 2647.12   144.4 2646.33   236.1 2646.75   254.1 2645.96
   278.4 2643.21   315.1 2642.54   365.8 2642.91   407.9 2643.69     434 2643.22
   452.3 2643.69   461.5 2642.83   470.4 2639.71   474.9 2639.39   479.3 2639.89
   483.8 2639.84  486.51 2639.17   492.7  2637.2   497.2 2636.72   509.1 2636.51
   519.5 2637.03     5302639.107   546.3 2641.76   555.2 2641.92   568.6 2643.28
   583.7 2643.53   601.6 2647.94   626.7 2656.38   635.6 2658.56   645.9  2660.4
#Mann= 4 ,-1,0
       0     .05       0     450      .1       0  486.51    .045       0
     530      .1       0
#XS Ineff= 2 , 0
          306.53 2647.45
Permanent Ineff=
       F       F
Bank Sta=486.51,530
XS Rating Curve= 0 ,0
Exp/Cntr(USF)=0,0
Exp/Cntr=0.5,0.3

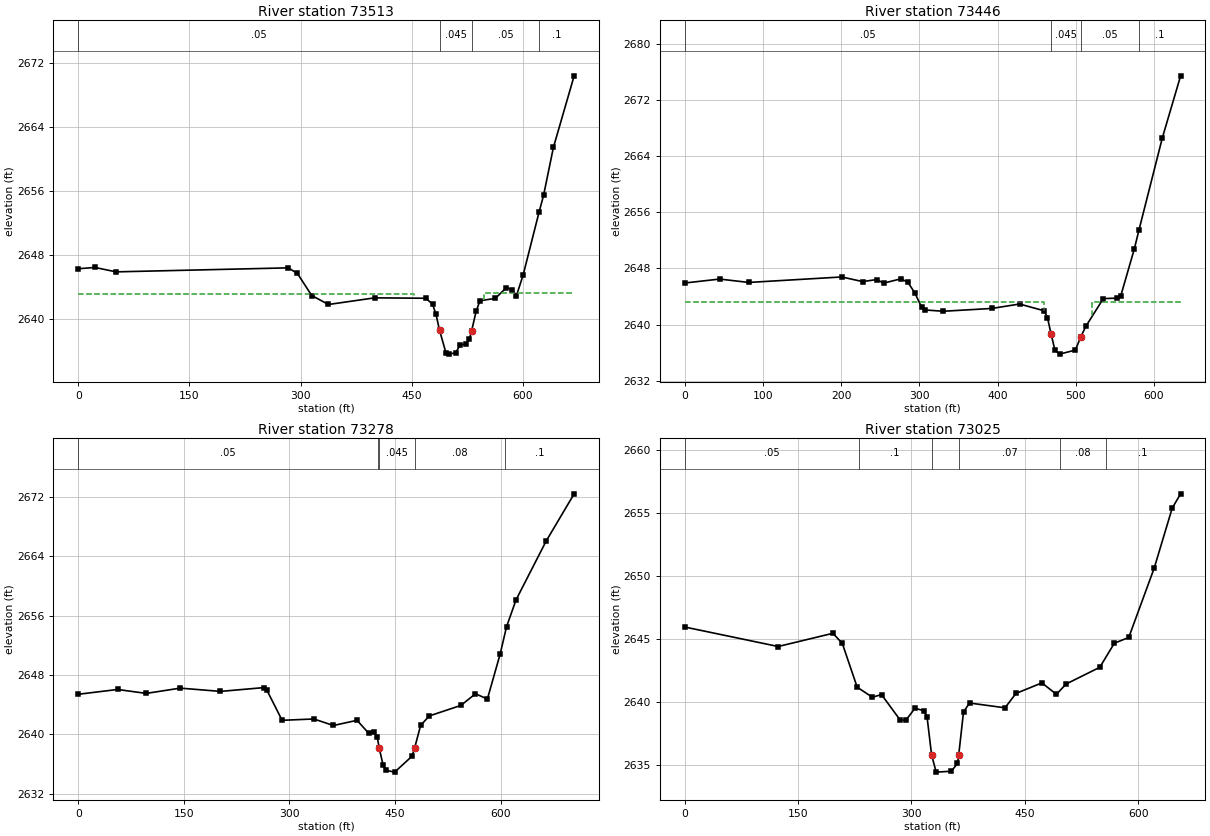
Type RM Length L Ch R = 1 ,73513   ,66.3,67.2,68.7
XS GIS Cut Line= 2
2310430.49721072538082.5589630562309839.37809874538396.328349508
#Sta/Elev= 30
       0 2646.31    22.7 2646.47      51 2645.92   283.4 2646.42   295.7 2645.73
   315.1 2642.97   337.7 2641.85   400.1 2642.68   469.1 2642.63   478.1 2641.89
   482.7 2640.66  487.52 2638.65   496.2 2635.82   500.4 2635.66   509.5 2635.84
   515.4 2636.83   523.4  2636.9   527.9 2637.57   530.82638.541     537 2641.03
   542.1 2642.32   562.8 2642.61   577.6 2643.94   585.7  2643.7   591.3 2642.94
   600.4 2645.54   621.9 2653.39   627.9 2655.45   641.2 2661.44   669.2 2670.37
#Mann= 4 ,-1,0
       0     .05       0  487.52    .045       0   530.8     .05       0
   621.9      .1       0
#XS Ineff= 2 , 0
           452.5  2643.2   547.5          2643.3
Permanent Ineff=
       F       F
Bank Sta=487.52,530.8
XS Rating Curve= 0 ,0
Exp/Cntr(USF)=0,0
Exp/Cntr=0.5,0.3

Type RM Length L Ch R = 1 ,73446   ,141.7,167.7,199.4
XS GIS Cut Line= 2
2310384.27225646538047.5400583182309815.56524352538327.691296222
#Sta/Elev= 30
       0 2645.93    44.7 2646.49      82 2646.01   200.8 2646.79   227.5 2646.13
   245.4 2646.42   254.3 2645.91   276.6 2646.53   285.5 2646.01   294.1 2644.54
     303 2642.46   307.8 2642.09   330.6 2641.91   392.6 2642.31   428.2 2642.94
   459.4 2641.98   463.8    2641   468.3 2638.72   473.3 2636.38   479.3 2635.81
   499.5 2636.39   506.3 2638.25   512.9 2639.78   535.2 2643.71     553 2643.78
   557.5  2644.1   574.9 2650.82   580.8 2653.49   610.7 2666.61     634 2675.41
#Mann= 4 ,-1,0
       0     .05       0   468.3    .045       0   506.3     .05       0
   580.8      .1       0
#XS Ineff= 2 , 0
           459.2 2643.16   520.8         2643.16
Permanent Ineff=
       F       F
Bank Sta=468.3,506.3
XS Rating Curve= 0 ,0
Exp/Cntr(USF)=0,0
Exp/Cntr=0.5,0.3

Type RM Length L Ch R = 1 ,73278   ,257.7,253,239.5
XS GIS Cut Line= 4
2310356.25713267 538015.322665962310095.71648142538132.986185879
2309812.76373114538069.9521573512309699.30247979  538130.1846735
#Sta/Elev= 30
       0 2645.39    55.9 2646.04    96.6 2645.51   144.9 2646.22     202 2645.78
   263.4 2646.29   267.8 2645.96   289.5 2641.88   334.6 2642.06   362.4 2641.18
   395.9 2641.88   412.4 2640.14   420.6 2640.32   424.7 2639.58  427.39 2638.12
   432.9 2635.85     437 2635.14   449.3 2634.89   473.9 2637.03   477.72638.153
   486.2 2641.19   498.5 2642.47   543.4 2643.89   564.1 2645.46     581 2644.75
   599.1 2650.81   608.2  2654.5   621.7 2658.13   664.4 2666.05   704.2 2672.43
#Mann= 5 ,-1,0
       0     .05       0  425.88     .08       0  427.39    .045       0
   477.7     .08       0  605.77      .1       0
Bank Sta=427.39,477.7
XS Rating Curve= 0 ,0
Exp/Cntr(USF)=0,0
Exp/Cntr=0.3,0.1

Type RM Length L Ch R = 1 ,73025   ,253.4,225.4,202.2
XS GIS Cut Line= 3
2310315.33008309537881.0304237712309939.93320884537844.418009848
2309706.91607229537997.680037359
#Sta/Elev= 30
       0 2645.96   123.7 2644.41   196.1 2645.46   208.5 2644.66   228.2 2641.18
   248.3 2640.38   260.4 2640.59   284.7  2638.6   292.5 2638.54   304.6  2639.5
   316.7 2639.31   320.7 2638.79  326.65  2635.8   332.7 2634.43   352.8  2634.5
   360.9 2635.12  362.54  2635.8   368.9 2639.22   376.9 2639.92   423.8 2639.54
   438.2 2640.68   472.6 2641.52   491.8 2640.61   504.6 2641.43   549.2 2642.76
   568.4 2644.67   587.5 2645.13   621.1 2650.63     645 2655.41   656.1 2656.54
#Mann= 6 ,-1,0
       0     .05       0     230      .1       0  326.65    .045       0
  362.54     .07       0  497.18     .08       0  557.18      .1       0
Bank Sta=326.65,362.54
XS Rating Curve= 0 ,0
Exp/Cntr(USF)=0,0
Exp/Cntr=0.3,0.1