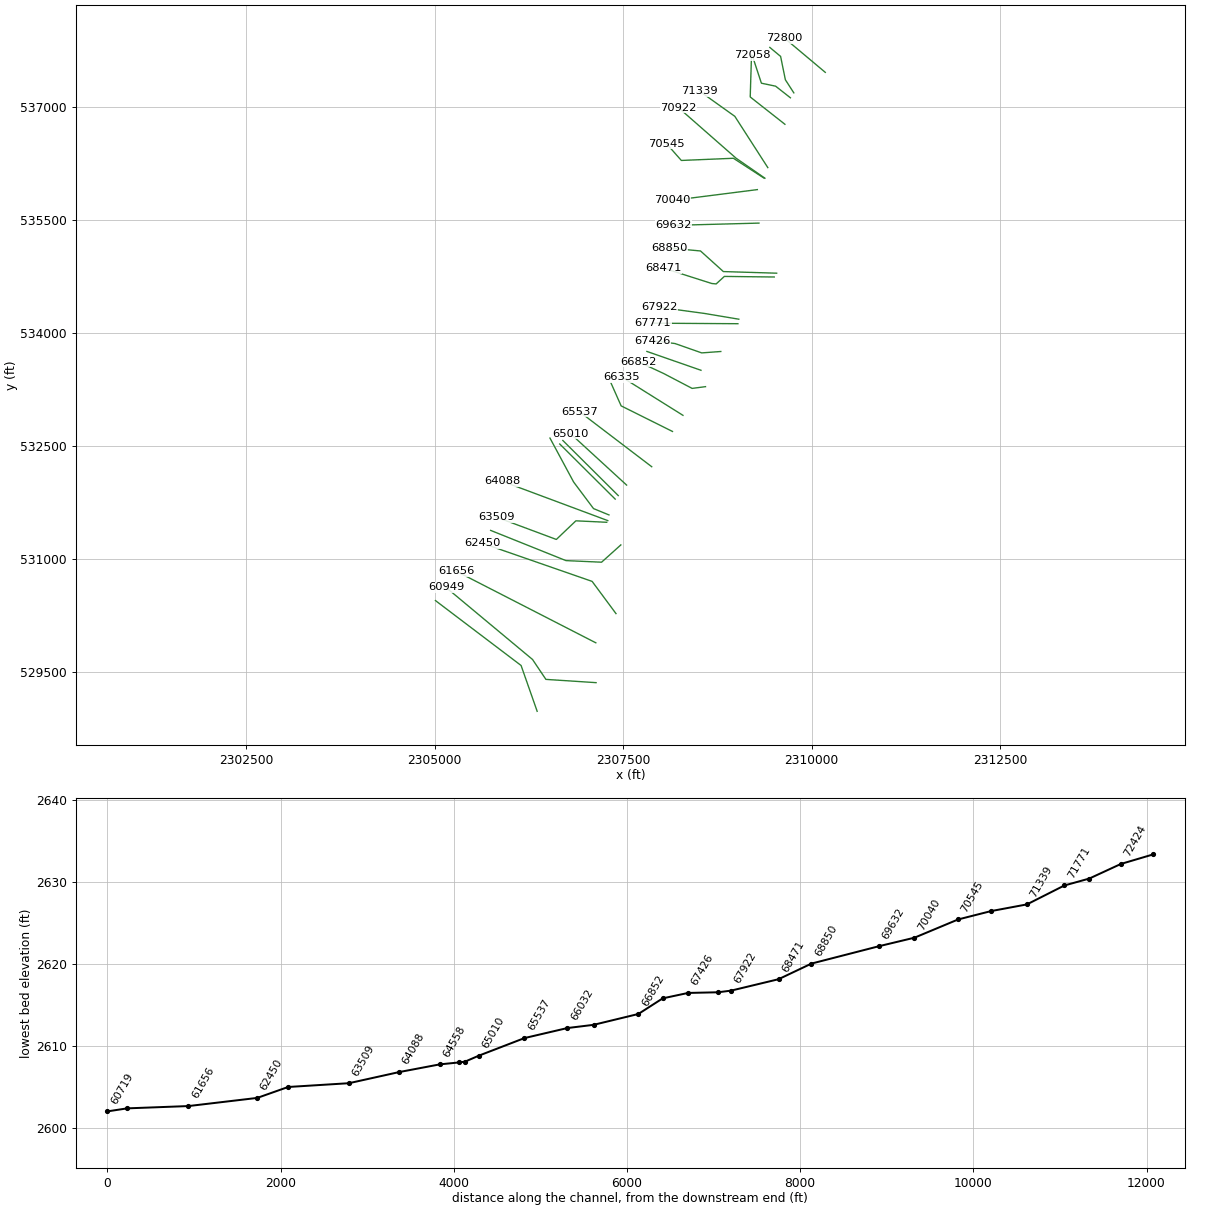
HEC-RAS study DEERCK.prj: DEERCK

--- DEERCK.g01 (geometry) --- (continued)

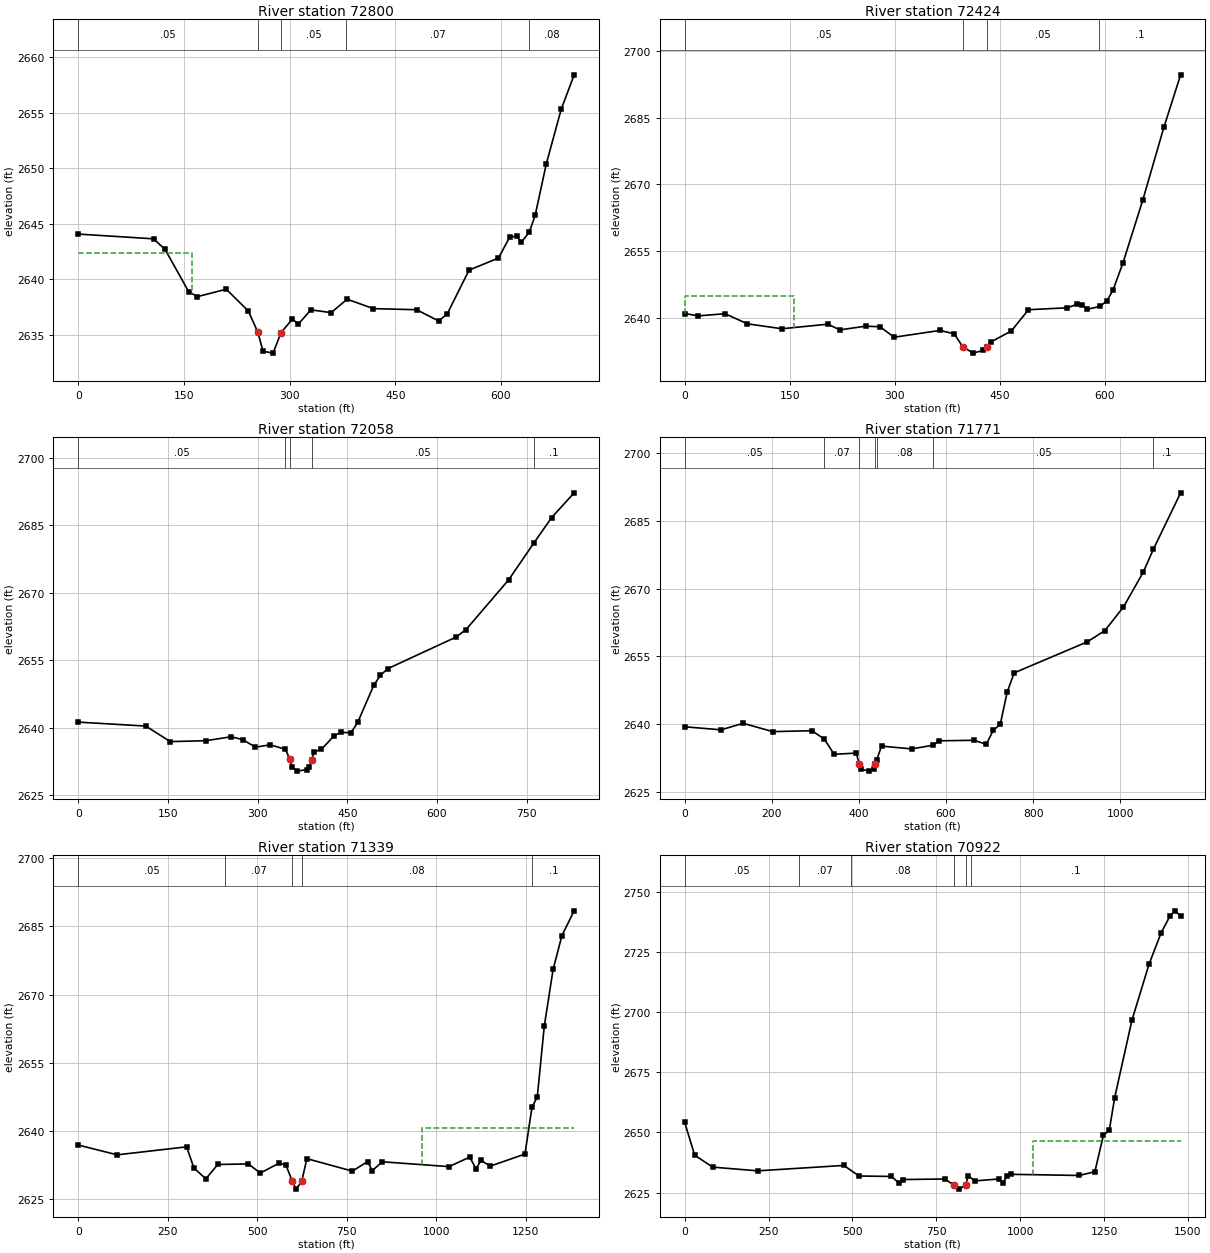
Type RM Length L Ch R = 1 ,72800   ,399.8,375.9,351
XS GIS Cut Line= 2
2310181.16260899537456.4209463432309641.87147602537908.865195556
#Sta/Elev= 30
       0 2644.06     107 2643.63   123.3 2642.67   156.8 2638.87   169.2 2638.42
   210.1 2639.09   241.5 2637.12  254.67 2635.25   262.4  2633.5   276.6 2633.33
   287.72635.158   304.1 2636.41   312.4 2635.94   330.2 2637.23     359 2636.98
   381.7 2638.19     419 2637.34   480.4 2637.24   511.5 2636.23   523.7 2636.86
   554.7 2640.81   596.5  2641.9   612.2 2643.76   622.6 2643.89   628.7 2643.31
   640.1 2644.22   648.6 2645.75   664.4  2650.4   685.5  2655.3   703.9 2658.41
#Mann= 5 ,-1,0
       0     .05       0  254.67    .045       0   287.7     .05       0
     380     .07       0     640     .08       0
#XS Ineff= 2 , 0
          162.13 2642.37
Permanent Ineff=
       F       F
Bank Sta=254.67,287.7
XS Rating Curve= 0 ,0
Exp/Cntr(USF)=0,0
Exp/Cntr=0.3,0.1

Type RM Length L Ch R = 1 ,72424   ,322.9,365.8,413.5
XS GIS Cut Line= 4
2309763.73726451537184.6742455772309651.67676935537358.368013077
2309588.64274082 537667.935130962309445.76560949537786.999407069
#Sta/Elev= 30
       0 2641.04    19.6 2640.52    57.7    2641    89.7 2638.73   138.9 2637.63
   204.4 2638.65   221.8 2637.38   258.6 2638.21     279 2638.07   299.4 2635.73
   364.7 2637.25   385.1  2636.5   397.3 2633.59   412.2 2632.16   425.9 2632.76
   431.72633.541   438.2 2634.71   466.7 2637.13   491.2  2641.9   546.6 2642.33
   560.8 2643.11   568.3 2643.01   575.3 2642.01   593.3 2642.63   603.4  2643.9
   611.9 2646.27   626.1 2652.34   654.5 2666.47   684.6 2682.78   708.6 2694.59
#Mann= 4 ,-1,0
       0     .05       0   397.3    .045       0   431.7     .05       0
  592.62      .1       0
#XS Ineff= 2 , 0
          156.81 2645.02
Permanent Ineff=
       F       F
Bank Sta=397.3,431.7
XS Rating Curve= 0 ,0
Exp/Cntr(USF)=0,0
Exp/Cntr=0.3,0.1

Type RM Length L Ch R = 1 ,72058   ,305.5,287.3,268.3
XS GIS Cut Line= 4
2309718.53595947537119.3708857052309522.30054931537273.242097672
2309334.06595645537312.708824076 2309212.5468073 537680.98436774
#Sta/Elev= 30
       0 2641.27   113.1 2640.39     154 2636.94   213.8 2637.14   255.6 2638.01
   274.8  2637.4   296.5  2635.7     321 2636.22   346.52635.248   353.7 2633.11
   357.8  2631.3     366 2630.38   382.3 2630.72   386.4 2631.28   390.5 2632.95
   394.6 2634.65   406.8 2635.23     428 2638.24   439.5    2639   456.2  2638.9
   467.5 2641.23   494.2 2649.41   505.4 2651.68     518 2653.16   631.7 2660.14
   648.6 2661.82   720.2 2672.92   762.3  2681.1   791.9 2686.72   829.5 2692.21
#Mann= 5 ,-1,0
       0     .05       0   346.5     .05       0   353.7    .045       0
   390.5     .05       0   762.3      .1       0
Bank Sta=353.7,390.5
XS Rating Curve= 0 ,0
Exp/Cntr(USF)=0,0
Exp/Cntr=0.3,0.1

Type RM Length L Ch R = 1 ,71771   ,444.9,432,418.4
XS GIS Cut Line= 3
2309645.71159696536768.0413077162309185.73882994537130.173514508
2309202.87541143537683.114542243
#Sta/Elev= 30
       0 2639.37    83.4  2638.7   134.3 2640.14   202.3  2638.3   292.1  2638.5
   320.9 2636.63     343 2633.27     394 2633.54     4012631.041   404.1 2630.03
   422.2 2629.54   434.7 2629.95   437.82631.023   440.6 2631.95   451.9 2635.09
   521.2 2634.47   570.9 2635.29     583 2636.26   664.5 2636.38   692.5 2635.48
   708.5 2638.62   724.5  2639.9   740.5 2647.12   756.5 2651.33   924.7 2658.22
   964.6  2660.7  1007.3 2665.92  1052.6 2673.62  1075.9  2678.7  1138.6 2691.25
#Mann= 7 ,-1,0
       0     .05       0   320.9     .07       0     401    .045       0
   437.8     .07       0   440.6     .08       0   570.9     .05       0
  1075.9      .1       0
Bank Sta=401,437.8
XS Rating Curve= 0 ,0
Exp/Cntr(USF)=0,0
Exp/Cntr=0.3,0.1

Type RM Length L Ch R = 1 ,71339   ,399.7,416.7,423
XS GIS Cut Line= 3
2309419.03538587536193.4434702932308981.49758306536873.472103574
2308512.33054149537208.214880421
#Sta/Elev= 30
       0 2636.94   108.8 2634.78   302.9 2636.54   323.1 2631.88   356.4  2629.5
   389.7 2632.66   475.3 2632.78   508.4 2630.76   560.9 2632.95     580 2632.56
   598.1 2628.92   608.5 2627.24   624.1 2628.93   638.6 2633.94   765.5  2631.2
   808.6 2633.31   820.8 2631.29   849.4 2633.25  1035.4 2632.19  1093.3 2634.28
  1111.2 2631.69  1124.7 2633.56  1150.6  2632.3  1247.6 2634.95  1267.2 2645.25
    1282  2647.5  1301.6 2663.09  1326.2 2675.55  1350.8    2683    1385 2688.44
#Mann= 5 ,-1,0
       0     .05       0     410     .07       0   598.1    .045       0
   624.1     .08       0 1268.63      .1       0
#XS Ineff= 2 , 0
                          960.84         2640.75
Permanent Ineff=
       F       F
Bank Sta=598.1,624.1
XS Rating Curve= 0 ,0
Exp/Cntr(USF)=0,0
Exp/Cntr=0.3,0.1

Type RM Length L Ch R = 1 ,70922   ,347.8,377.4,403.1
XS GIS Cut Line= 3
2309380.66385901536053.2735863772308998.50358173536318.010314772
2308236.31800079536986.257056608
#Sta/Elev= 30
       0 2654.16    29.8 2640.51    83.6 2635.56   217.6 2634.02   474.5 2636.26
   519.8 2631.87   615.3 2631.69   638.9 2629.04   651.7 2630.41   774.9 2630.62
   803.4 2628.08   819.1 2626.42   837.3 2628.13   845.8 2632.03   864.1 2629.83
   936.1 2630.63     949 2628.97   961.2 2631.99   973.8 2632.57  1175.5 2632.09
  1222.8 2633.63  1248.3 2648.79  1265.9  2650.9  1281.9 2664.44  1333.3 2696.57
  1384.3 2719.83  1420.2 2732.85  1446.8 2739.86  1460.9 2742.03  1478.5    2740
#Mann= 6 ,-1,0
       0     .05       0     340     .07       0   494.9     .08       0
   803.4    .045       0   837.3     .08       0   854.9      .1       0
#XS Ineff= 2 , 0
                         1037.47         2646.28
Permanent Ineff=
       F       F
Bank Sta=803.4,837.3
XS Rating Curve= 0 ,0
Exp/Cntr(USF)=0,0
Exp/Cntr=0.3,0.1

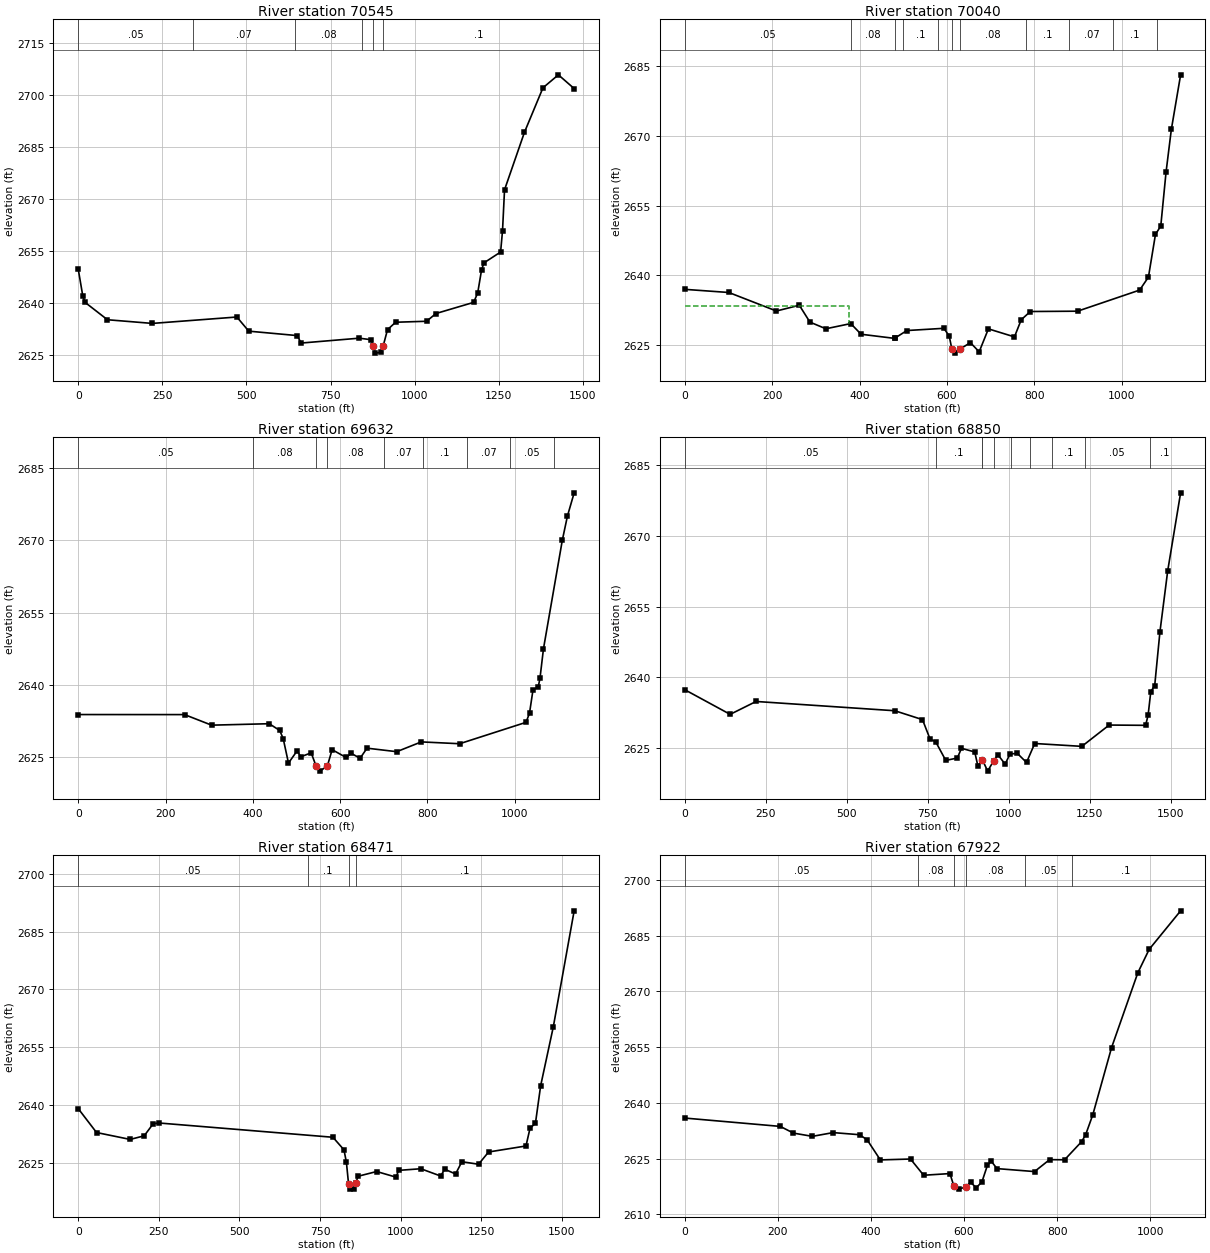
Type RM Length L Ch R = 1 ,70545   ,500.4,504.5,507.3
XS GIS Cut Line= 4
2309368.95575783536053.7476657822308963.04719378536317.324655425
2308272.47548091536288.3311865652308074.79273868536512.371627762
#Sta/Elev= 30
       0 2649.73    13.6 2641.94    20.4 2640.08    86.9 2635.06   220.3    2634
   471.5 2635.85   506.9 2631.76     651 2630.48   662.3 2628.32   835.2 2629.73
   871.2 2629.28  876.43 2627.51   883.2 2625.41   899.2 2625.65  906.34 2627.49
   919.2 2632.19   943.3 2634.34  1035.3 2634.62  1063.2 2636.86  1175.2 2640.08
  1187.3 2642.83  1198.6 2649.41  1205.8  2651.5  1255.3 2654.64    1261 2660.76
    1267 2672.62  1326.2 2689.25  1381.2 2702.11    1427 2705.86  1473.9 2701.89
#Mann= 6 ,-1,0
       0     .05       0     340     .07       0  643.98     .08       0
  843.98      .1       0  876.43    .045       0  906.34      .1       0
Bank Sta=876.43,906.34
XS Rating Curve= 0 ,0
Exp/Cntr(USF)=0,0
Exp/Cntr=0.3,0.1

Type RM Length L Ch R = 1 ,70040   ,410.3,407.6,403.8
XS GIS Cut Line= 2
2309280.32009906535901.6904596352308155.18900338535758.647227357
#Sta/Elev= 30
       0 2636.94     101 2636.26   209.8 2632.27   262.2 2633.51   286.4 2629.88
   322.9 2628.44   379.8 2629.56   403.4 2627.26     480 2626.37     480 2626.38
   508.2 2628.06   592.9 2628.54     605 2626.85  611.09 2624.06   617.1 2623.19
   629.2 2624.04   653.4 2625.45   673.5 2623.47   694.6 2628.42   754.2 2626.69
   769.7 2630.39   790.5 2632.16   898.5 2632.23  1040.5 2636.78  1060.6 2639.58
  1076.7  2648.8  1088.8 2650.58  1100.9 2662.23    1113 2671.42  1134.2 2683.18
#Mann= 11 ,-1,0
       0     .05       0     380     .08       0     480     .07       0
     500      .1       0     580     .08       0  611.09    .045       0
   629.2     .08       0     780      .1       0     880     .07       0
     980      .1       0    1080     .08       0
#XS Ineff= 2 , 0
          376.92 2633.32
Permanent Ineff=
       F       F
Bank Sta=611.09,629.2
XS Rating Curve= 0 ,0
Exp/Cntr(USF)=0,0
Exp/Cntr=0.3,0.1

Type RM Length L Ch R = 1 ,69632   ,804.7,782,751
XS GIS Cut Line= 2
2309301.66983522535457.6159474882308165.86387146535427.726316863
#Sta/Elev= 30
       0 2633.89   243.6 2633.88   305.6 2631.69   437.6 2631.99   461.7 2630.59
   469.7 2628.88   481.7 2623.83   501.7 2626.39   509.7 2625.12   533.7 2625.96
  545.06 2623.19   553.7 2622.16   570.82623.221   581.7 2626.61   613.7 2624.99
   625.7 2625.84   645.7 2624.82   661.7 2626.92   729.7 2626.19     786 2628.22
   873.8 2627.84  1025.8 2632.27  1033.9 2634.16  1041.9    2639  1053.9 2639.62
  1057.9  2641.4  1065.9 2647.53  1109.1 2670.04  1120.8 2675.04  1136.2 2679.86
#Mann= 9 ,-1,0
       0     .05       0     400     .08       0  545.06    .045       0
   570.8     .08       0     700     .07       0     790      .1       0
     890     .07       0     990     .05       0    1090     .08       0
Bank Sta=545.06,570.8
XS Rating Curve= 0 ,0
Exp/Cntr(USF)=0,0
Exp/Cntr=0.3,0.1

Type RM Length L Ch R = 1 ,68850   ,345,379.9,390.1
XS GIS Cut Line= 4
2309536.51693299534793.6391528842308829.84066606534814.988889045
2308526.67441258535088.2655119052308112.48953106535126.695036994
#Sta/Elev= 30
       0 2637.35   140.4  2632.1   220.4 2634.84   648.7 2632.87   734.2 2630.98
   757.7 2626.83   774.9 2626.28     806 2622.32   841.7 2622.82   854.6 2624.89
   895.5 2624.11   905.2 2621.13   919.3 2622.43   935.4 2620.04     9542622.255
   967.2 2623.51   989.3 2621.52  1004.3 2623.68    1027 2623.81  1055.3 2621.88
  1080.7 2625.91  1226.1  2625.3  1310.5 2629.83    1423 2629.77  1430.8 2631.96
    1439 2636.92  1451.1 2638.23  1467.2 2649.61  1491.3 2662.63  1531.1 2679.17
#Mann= 10 ,-1,0
       0     .05       0     777      .1       0     917     .05       0
   919.3    .045       0     954     .05       0    1007      .1       0
    1067     .05       0 1135.15      .1       0 1235.15     .05       0
 1435.15      .1       0
Bank Sta=919.3,954
XS Rating Curve= 0 ,0
Exp/Cntr(USF)=0,0
Exp/Cntr=0.3,0.1

Type RM Length L Ch R = 1 ,68471   ,539.3,548.5,542.1
XS GIS Cut Line= 5
2309504.98264877534743.0330390982308842.83958156534750.765987039
2308734.29217171534651.4032107142308676.53571165534656.653797993
2308037.78083476534860.113711454
#Sta/Elev= 30
       0 2639.04    56.8 2632.83   161.1 2631.04   204.6 2631.98   232.3 2635.09
   249.6 2635.31   789.8  2631.6     824 2628.34   831.6 2625.06   838.12619.599
   843.6 2618.14   855.7 2618.24   860.8 2619.67   867.7 2621.48   925.4 2622.71
   985.3 2621.25   993.7 2623.01  1062.3 2623.43  1123.8 2621.54  1136.4  2623.3
    1170 2622.07  1189.6 2625.25  1241.3  2624.6  1272.4 2627.78  1388.3 2629.34
  1400.9 2633.94  1417.7 2635.24  1433.8 2644.97    1473 2660.23  1537.7 2690.37
#Mann= 4 ,-1,0
       0     .05       0  712.19      .1       0   838.1    .045       0
   860.8      .1       0
Bank Sta=838.1,860.8
XS Rating Curve= 0 ,0
Exp/Cntr(USF)=0,0
Exp/Cntr=0.3,0.1

Type RM Length L Ch R = 1 ,67922   ,146.7,151.3,155.9
XS GIS Cut Line= 4
 2309034.6705805534183.5577792522308579.65679172534259.820414091
2308142.28845605534319.3035653432307981.41795086534342.345864809
#Sta/Elev= 30
       0  2635.9   205.3 2633.65   233.7 2631.84   274.3 2630.97   318.9 2631.98
   375.7 2631.41   391.9 2630.04   420.3 2624.62   485.1 2624.86   513.3 2620.49
   569.8 2620.94   577.9 2617.71     590 2616.75   604.2 2617.42   614.2 2618.59
   626.3 2617.13   638.5  2618.7   650.4  2623.2   658.6 2624.27   670.8 2622.28
   751.5 2621.48   783.8 2624.69   816.1 2624.66   852.4 2629.51     861 2631.31
   876.6 2636.76     917 2654.89   973.4 2675.04   997.8 2681.36  1065.3 2691.73
#Mann= 6 ,-1,0
       0     .05       0  501.36     .08       0   577.9     .04       0
   604.2     .08       0  731.36     .05       0  831.36      .1       0
Bank Sta=577.9,604.2
XS Rating Curve= 0 ,0
Exp/Cntr(USF)=0,0
Exp/Cntr=0.3,0.1

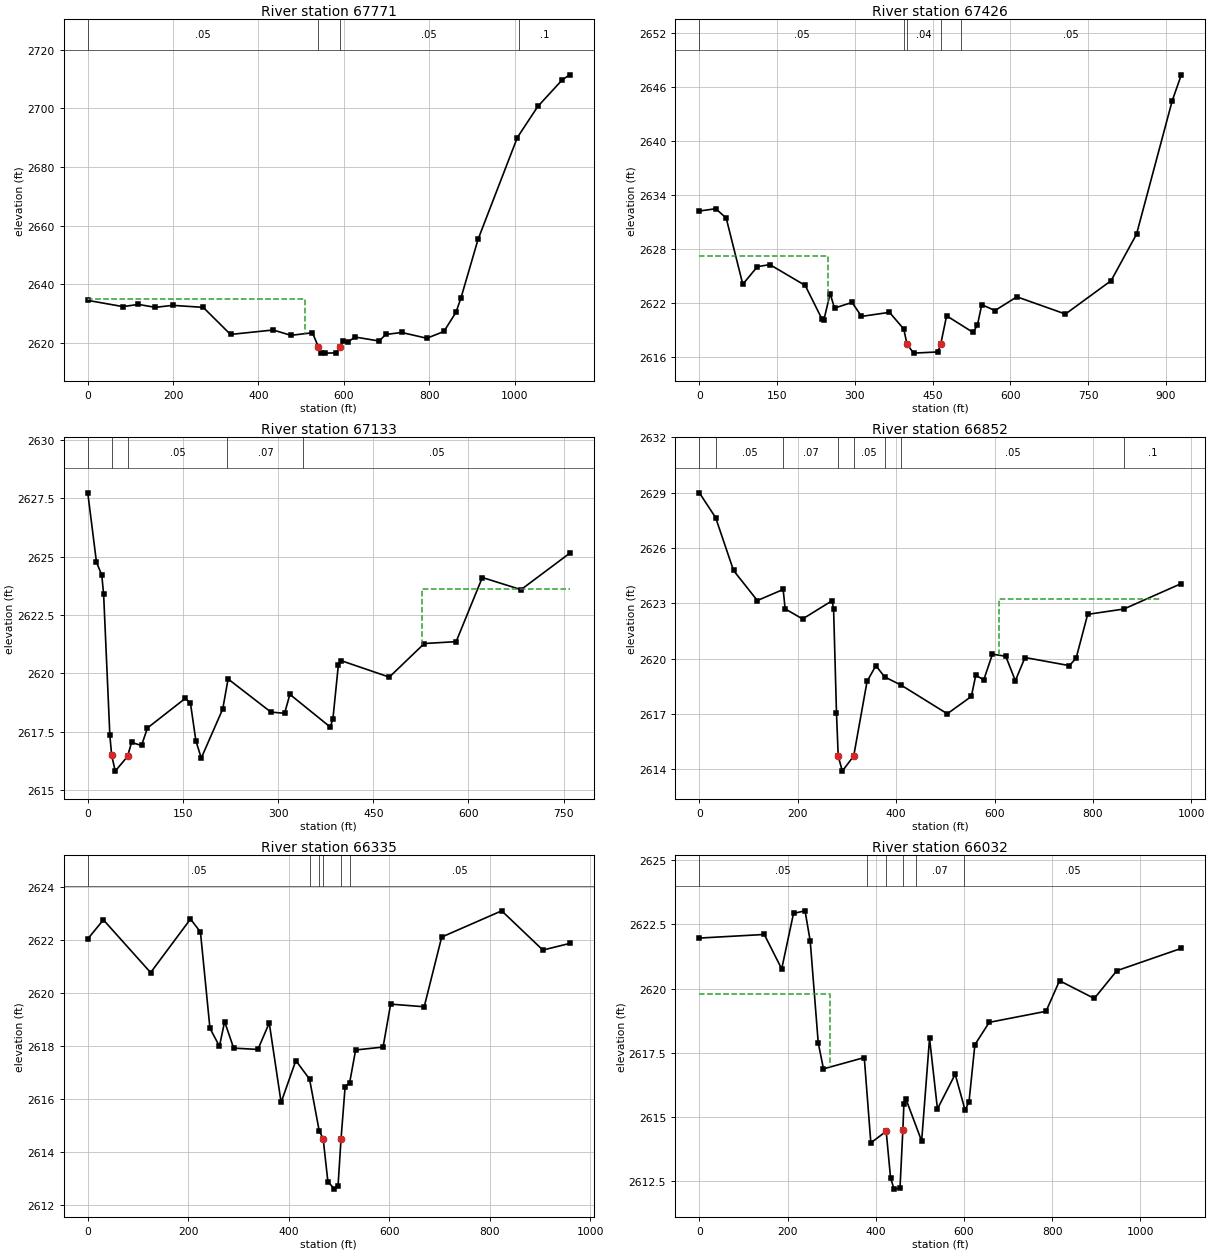
Type RM Length L Ch R = 1 ,67771   ,361.7,344.9,327.3
XS GIS Cut Line= 2
2309022.69151477534123.7386067742307893.54112414534130.520290801
#Sta/Elev= 30
       0 2634.54    82.5 2632.41   118.5 2633.16   158.5 2632.16   198.8 2632.84
   270.5 2632.16   334.5 2622.92   434.5 2624.44   475.9 2622.62   526.5 2623.49
   540.3  2618.7   546.5 2616.56   556.4 2616.55   582.5 2616.64   590.5 2618.53
   598.5 2620.67   610.5 2620.47   626.5 2622.03   682.5 2620.69   698.5 2622.92
   735.6 2623.59   794.5 2621.62   834.5 2623.94   862.8 2630.49   874.5 2635.39
   914.5 2655.35  1006.5 2690.06  1054.5 2700.67  1111.8 2709.74  1129.2 2711.45
#Mann= 4 ,-1,0
       0     .05       0   540.3     .04       0   590.5     .05       0
    1010      .1       0
#XS Ineff= 2 , 0
          508.31 2635.13
Permanent Ineff=
       F       F
Bank Sta=540.3,590.5
XS Rating Curve= 0 ,0
Exp/Cntr(USF)=0,0
Minor Loss Coefficient=0
Exp/Cntr=0.3,0.1

Type RM Length L Ch R = 1 ,67426   ,289.6,293.1,319
XS GIS Cut Line= 4
2308795.69432056533755.2915357812308542.45926713533736.674478512
2308189.34858123533860.6556826532307890.45227498533899.085207743
#Sta/Elev= 30
       0 2632.22    31.6 2632.47    51.7 2631.44    83.7  2624.1   111.8 2626.05
   135.9 2626.28   204.1 2623.97   236.2 2620.27   240.2 2620.16   252.2 2623.07
   260.6 2621.46   294.5 2622.09   312.6 2620.54   366.6 2620.99   394.2 2619.14
   400.3 2617.49     413 2616.47   459.8  2616.6   465.5 2617.47   476.8 2620.61
   527.7 2618.77   536.1 2619.55   544.6 2621.84   570.1 2621.19   612.4 2622.71
     706  2620.8   794.1  2624.5   843.1 2629.65     912 2644.45   929.5 2647.31
#Mann= 5 ,-1,0
       0     .05       0  393.92     .07       0   400.3     .04       0
   465.5     .07       0  503.92     .05       0
#XS Ineff= 2 , 0
          247.51 2627.27
Permanent Ineff=
       F       F
Bank Sta=400.3,465.5
XS Rating Curve= 0 ,0
Exp/Cntr(USF)=0,0
Exp/Cntr=0.3,0.1

Type RM Length L Ch R = 1 ,67133   ,283,281.1,274.9
XS GIS Cut Line= 2
2308533.07933343533506.2500623832307815.72819842533756.041975465
#Sta/Elev= 30
       0 2627.74    13.7 2624.77    22.1 2624.21      25 2623.39    34.8 2617.36
    37.6  2616.5    43.3 2615.81    62.7 2616.44      69 2617.04    84.7 2616.91
    94.1 2617.66   153.8 2618.93   161.9 2618.72   170.4 2617.11   178.9 2616.37
   212.7 2618.47   221.2 2619.76   288.7 2618.34   310.2 2618.29   318.6  2619.1
   382.2  2617.7   386.4 2618.05   394.9 2620.34   398.9 2620.55   475.3 2619.84
   530.4 2621.28   580.6 2621.36   621.9 2624.11   682.9 2623.59   759.6 2625.15
#Mann= 5 ,-1,0
       0     .05       0    37.6     .04       0    62.7     .05       0
     220     .07       0     340     .05       0
#XS Ineff= 2 , 0
                          527.57         2623.63
Permanent Ineff=
       F       F
Bank Sta=37.6,62.7
XS Rating Curve= 0 ,0
Exp/Cntr(USF)=0,0
Exp/Cntr=0.3,0.1

Type RM Length L Ch R = 1 ,66852   ,509.5,516.8,512.8
XS GIS Cut Line= 4
2308593.01550751533289.0186559432308415.52202631533265.962300875
2308037.76545449533463.5505900612307698.30464953533621.538637651
#Sta/Elev= 30
       0    2629    33.1 2627.65    69.4 2624.79   117.8 2623.16   170.3 2623.76
   174.3 2622.71   209.8 2622.16   269.8 2623.15   272.8  2622.7   278.7 2617.06
   282.22614.734   290.5 2613.91   313.7 2614.73   340.9 2618.78   358.8 2619.63
   376.5 2619.02   410.3 2618.57   503.9 2617.02   552.9 2617.96   561.9 2619.12
     578 2618.85   595.7 2620.25   622.8 2620.14   642.3 2618.81   661.9 2620.07
   752.2 2619.63   765.9 2620.04   789.3 2622.41   862.9  2622.7   979.7 2624.08
#Mann= 8 ,-1,0
       0     .07       0    33.1     .05       0   170.3     .07       0
   282.2     .04       0   313.7     .05       0   376.5     .07       0
   410.3     .05       0   862.9      .1       0
#XS Ineff= 1 ,-1
  609.78  938.35 2623.24
Permanent Ineff=
       F
Bank Sta=282.2,313.7
XS Rating Curve= 0 ,0
Exp/Cntr(USF)=0,0
Exp/Cntr=0.3,0.1

Type RM Length L Ch R = 1 ,66335   ,298.1,302.7,305.5
XS GIS Cut Line= 2
2308294.23801303532908.6884113422307481.48934677533417.533176583
#Sta/Elev= 30
       0 2622.03    31.1 2622.75   125.1 2620.76   204.4 2622.78   224.2 2622.29
   243.1 2618.66     262 2617.98   272.3 2618.91   290.3 2617.91   338.5 2617.86
   361.1 2618.86   384.7 2615.86     414 2617.44   441.3 2616.74   460.52614.787
   468.3  2614.5   477.8 2612.87   490.9 2612.59     498 2612.71   503.9 2614.48
   512.1 2616.46     521  2616.6     533 2617.84   587.6 2617.95   602.6 2619.57
   669.4 2619.47   704.2  2622.1   823.6 2623.09   905.5 2621.61   958.9 2621.86
#Mann= 6 ,-1,0
       0     .05       0   441.3     .07       0   460.5     .04       0
   468.3     .04       0   503.9     .07       0     521     .05       0
Bank Sta=468.3,503.9
XS Rating Curve= 0 ,0
Exp/Cntr(USF)=0,0
Exp/Cntr=0.3,0.1

Type RM Length L Ch R = 1 ,66032   ,501.5,495.4,487.3
XS GIS Cut Line= 3
2308155.18900338532694.9600882692307474.13241985533034.420893227
2307339.62908203533337.587146712
#Sta/Elev= 30
       0 2621.97   147.1 2622.11   186.6 2620.77   213.4 2622.93   239.5 2623.03
   251.3 2621.85   269.4  2617.9   281.3 2616.88   373.8 2617.32   388.7    2614
   423.5 2614.45   433.4 2612.64   441.4  2612.2   454.8 2612.24  461.33 2614.52
   463.7 2615.53   468.2 2615.71   503.9 2614.07   521.8 2618.07   539.7 2615.32
   579.9 2616.67   602.3 2615.28   611.2 2615.59   624.6 2617.82   657.1 2618.69
   785.9 2619.12   816.5 2620.31   895.3 2619.62   946.4  2620.7  1092.6 2621.57
#Mann= 6 ,-1,0
       0     .05       0     380     .07       0   423.5     .04       0
  461.33     .05       0     490     .07       0     600     .05       0
#XS Ineff= 2 , 0
          295.02 2619.79
Permanent Ineff=
       F       F
Bank Sta=423.5,461.33
XS Rating Curve= 0 ,0
Exp/Cntr(USF)=0,0
Exp/Cntr=0.3,0.1

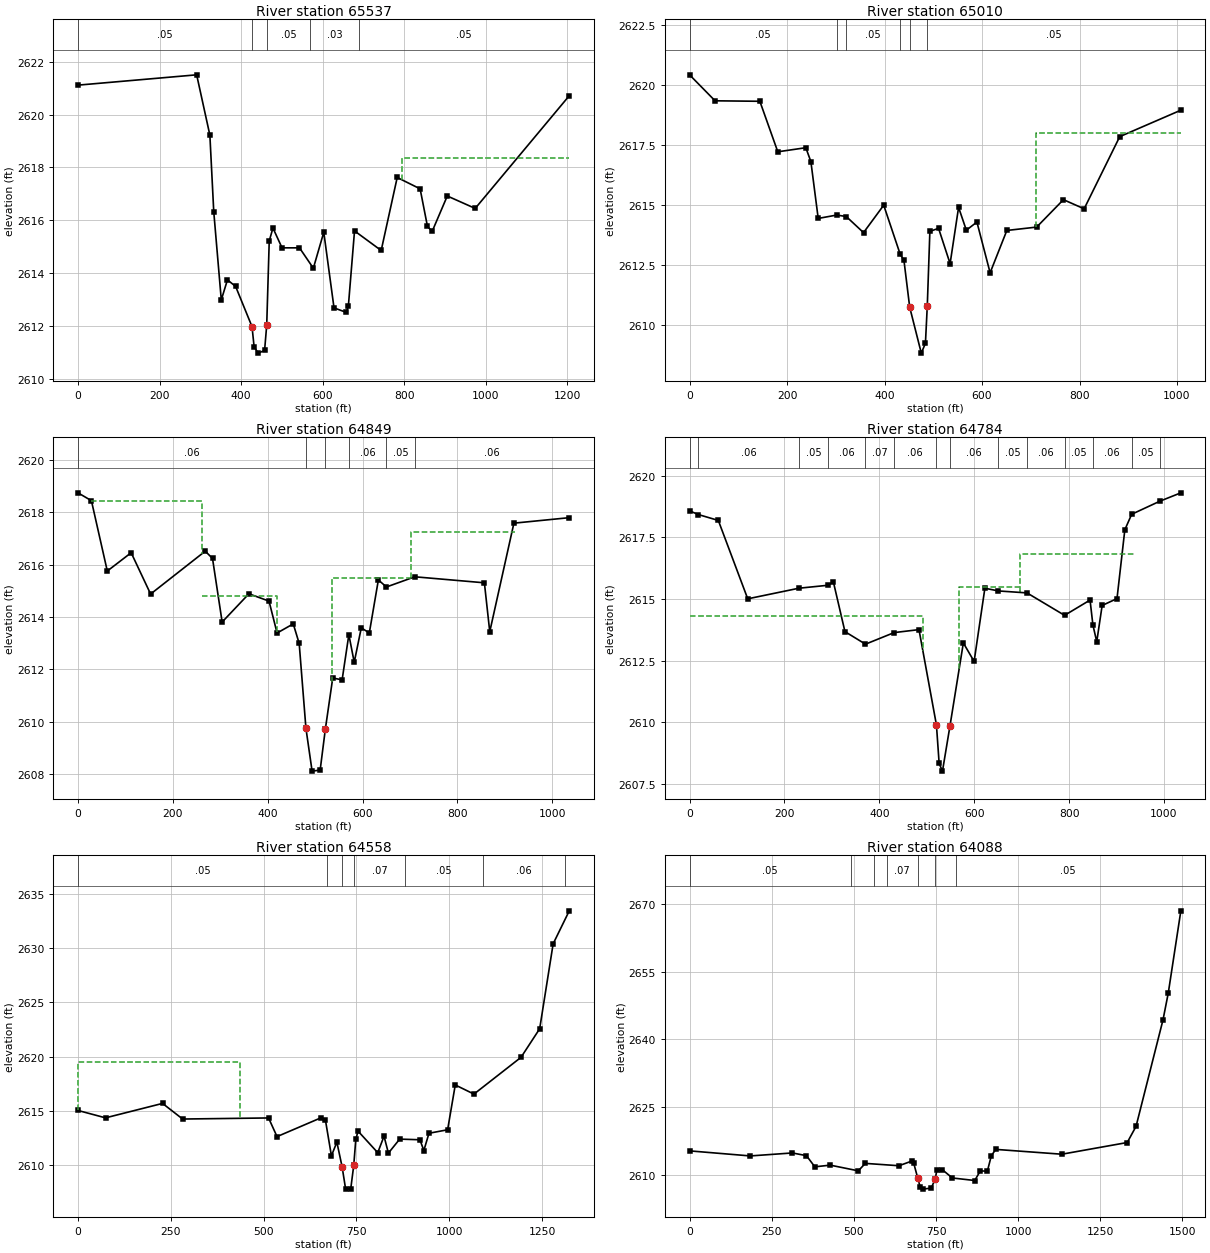
Type RM Length L Ch R = 1 ,65537   ,519.8,527.1,518.5
XS GIS Cut Line= 2
 2307879.7774069532227.4008663452306921.17425328532957.561843048
#Sta/Elev= 30
       0 2621.11   291.1  2621.5   323.5 2619.22     333 2616.33   351.5 2612.99
   366.6 2613.75   386.7  2613.5   426.9 2611.98     432 2611.22     442 2610.98
   457.7 2611.08  462.94 2612.04   469.1 2615.22   478.2 2615.71   500.5 2614.96
   543.3 2614.96   577.3 2614.19   602.9 2615.55     628 2612.69   658.2 2612.52
   663.2 2612.76   678.3  2615.6   743.7 2614.86     783 2617.62   839.2 2617.19
   857.2 2615.77   868.7 2615.58   905.8 2616.92   974.3 2616.45    1205 2620.71
#Mann= 5 ,-1,0
       0     .05       0   426.9     .04       0  462.94     .05       0
     570     .03       0     690     .05       0
#XS Ineff= 2 , 0
                          795.35         2618.37
Permanent Ineff=
       F       F
Bank Sta=426.9,462.94
XS Rating Curve= 0 ,0
Exp/Cntr(USF)=0,0
Exp/Cntr=0.3,0.1

Type RM Length L Ch R = 1 ,65010   ,164.2,160.1,159.3
XS GIS Cut Line= 2
2307546.72152279531984.0138741112306803.75070439532665.070457643
#Sta/Elev= 30
       0 2620.41    52.3 2619.33   144.2 2619.31     181 2617.21   238.5 2617.38
   248.9  2616.8   263.9 2614.44   301.9 2614.58   321.4 2614.52   356.9 2613.85
   398.3 2614.99   432.1 2612.95   439.8  2612.7   451.6 2610.75   475.4 2608.84
   483.9 2609.25  487.73 2610.82     493  2613.9   510.8 2614.03   534.5 2612.56
   551.9  2614.9   567.8 2613.95   589.5 2614.29   616.6 2612.18   650.9 2613.94
   712.1 2614.08     767 2615.22   809.5 2614.84   882.5 2617.84  1007.9 2618.94
#Mann= 6 ,-1,0
       0     .05       0   301.9     .03       0   321.4     .05       0
   432.1     .03       0   451.6     .04       0  487.73     .05       0
#XS Ineff= 2 , 0
                          710.65            2618
Permanent Ineff=
       F       F
Bank Sta=451.6,487.73
XS Rating Curve= 0 ,0
Exp/Cntr(USF)=0,0
Exp/Cntr=0.5,0.3

Type RM Length L Ch R = 1 ,64849   ,70.9,65.7,66
XS GIS Cut Line= 2
2307435.70289475531845.2405890652306701.27197082532575.401565768
#Sta/Elev= 30
       0 2618.75    28.3 2618.45    61.8 2615.76   112.1 2616.46   153.1 2614.88
   268.3 2616.52   283.6 2616.24   303.9 2613.81   360.3 2614.89   402.7 2614.61
   419.7 2613.39   453.8 2613.74   466.3 2612.99   480.5 2609.75   493.5 2608.11
   510.5 2608.15  521.47 2609.72     537 2611.67   556.8  2611.6     571 2613.33
   582.3 2612.27   597.2 2613.59   614.1 2613.39   633.2 2615.42   650.2 2615.15
     710 2615.54   856.7 2615.31     868 2613.44   918.9 2617.59  1035.6  2617.8
#Mann= 6 ,-1,0
       0     .06       0   480.5     .04       0  521.47     .05       0
     571     .06       0   650.2     .05       0     710     .06       0
#XS Ineff= 5 ,-1
   27.91  261.13 2618.42  261.13     420  2614.8   535.9  701.42  2615.5
  701.42  920.28 2617.26  920.28  1035.6  2615.5
Permanent Ineff=
       F       F       F       F       F
Bank Sta=480.5,521.47
XS Rating Curve= 0 ,0
Exp/Cntr(USF)=0,0
Exp/Cntr=0.5,0.3

Type RM Length L Ch R = 1 ,64784   ,234.1,225.5,213.1
XS GIS Cut Line= 2
2307395.13839605531798.2711695112306660.70747211532528.432146214
#Sta/Elev= 30
       0 2618.58    18.3 2618.43    60.6 2618.19   122.6 2615.01   230.4 2615.44
   291.8 2615.56   303.1  2615.7   327.5 2613.68   370.8 2613.17   431.2 2613.64
   483.6 2613.76   520.4 2609.89   526.1 2608.33   533.1 2608.02   548.8 2609.84
   577.1 2613.22   599.8 2612.47   622.5 2615.44   650.9 2615.33   711.3 2615.25
   790.5 2614.34   844.2 2614.96   850.2 2613.95   858.3 2613.27   869.7 2614.74
     901 2615.02   917.5 2617.81   931.9 2618.44   991.3 2618.97  1035.6 2619.31
#Mann= 14 ,-1,0
       0     .05       0    18.3     .06       0   230.4     .05       0
   291.8     .06       0   370.8     .07       0   431.2     .06       0
   520.4     .04       0   548.8     .06       0   650.9     .05       0
   711.3     .06       0   790.5     .05       0   850.2     .06       0
   931.9     .05       0   991.3     .06       0
#XS Ineff= 4 ,-1
       0   491.7  2614.3   568.3  697.15  2615.5  697.15  937.37 2616.83
  937.37  1035.6  2615.5
Permanent Ineff=
       F       F       F       F
Bank Sta=520.4,548.8
XS Rating Curve= 0 ,0
Exp/Cntr(USF)=0,0
Exp/Cntr=0.5,0.3

Type RM Length L Ch R = 1 ,64558   ,444.9,470.6,492.9
XS GIS Cut Line= 4
2307312.85571693531588.2386147632307108.02312322 531672.33781792
2306844.27100541532024.6963209362306530.47408153532607.426170009
#Sta/Elev= 30
       0 2615.03    74.2 2614.35   227.8 2615.68   281.9 2614.24   513.4 2614.34
   536.2 2612.62     655 2614.36   666.7 2614.12   682.7 2610.85   697.4 2612.11
   711.62609.817     721 2607.78   734.8 2607.82   742.92609.987   748.4 2612.38
   754.6 2613.12   807.5 2611.14   824.4 2612.66   836.2  2611.1   866.6 2612.39
   921.1 2612.33   931.7 2611.34   945.5 2612.93   995.7 2613.25  1016.3 2617.38
  1066.7 2616.54  1193.5 2619.93  1243.7 2622.56    1280 2630.39  1323.4 2633.43
#Mann= 7 ,-1,0
       0     .05       0  671.56     .07       0   711.6     .04       0
   742.9     .07       0  881.56     .05       0 1091.56     .06       0
 1311.56     .05       0
#XS Ineff= 2 , 0
          437.21 2619.49
Permanent Ineff=
       F       F
Bank Sta=711.6,742.9
XS Rating Curve= 0 ,0
Exp/Cntr(USF)=0,0
Exp/Cntr=0.3,0.1

Type RM Length L Ch R = 1 ,64088   ,527.6,578.3,627.6
XS GIS Cut Line= 2
 2307297.3776906531513.0017936222305896.38691755532035.253240897
#Sta/Elev= 30
       0 2615.31   184.8 2614.19   312.9 2614.85   355.7 2614.25   381.2 2611.78
   428.2 2612.15   513.5 2610.89   534.9 2612.54   637.3 2612.02   675.9 2613.04
   682.1 2612.61   694.5 2609.26   701.4 2607.42   709.9 2606.84   735.5 2607.07
   747.4 2609.06   752.6    2611   769.7 2611.12   799.6 2609.31   867.9 2608.75
   884.9 2610.88   906.3 2610.81   918.4 2614.24   931.9 2615.64    1133 2614.57
    1332 2617.16  1358.8 2620.73  1440.9 2644.33    1457 2650.29  1495.2 2668.46
#Mann= 7 ,-1,0
       0     .05       0     490     .07       0     560     .05       0
     600     .07       0   694.5     .04       0   747.4     .07       0
     810     .05       0
Bank Sta=694.5,747.4
XS Rating Curve= 0 ,0
Exp/Cntr(USF)=0,0
Exp/Cntr=0.3,0.1

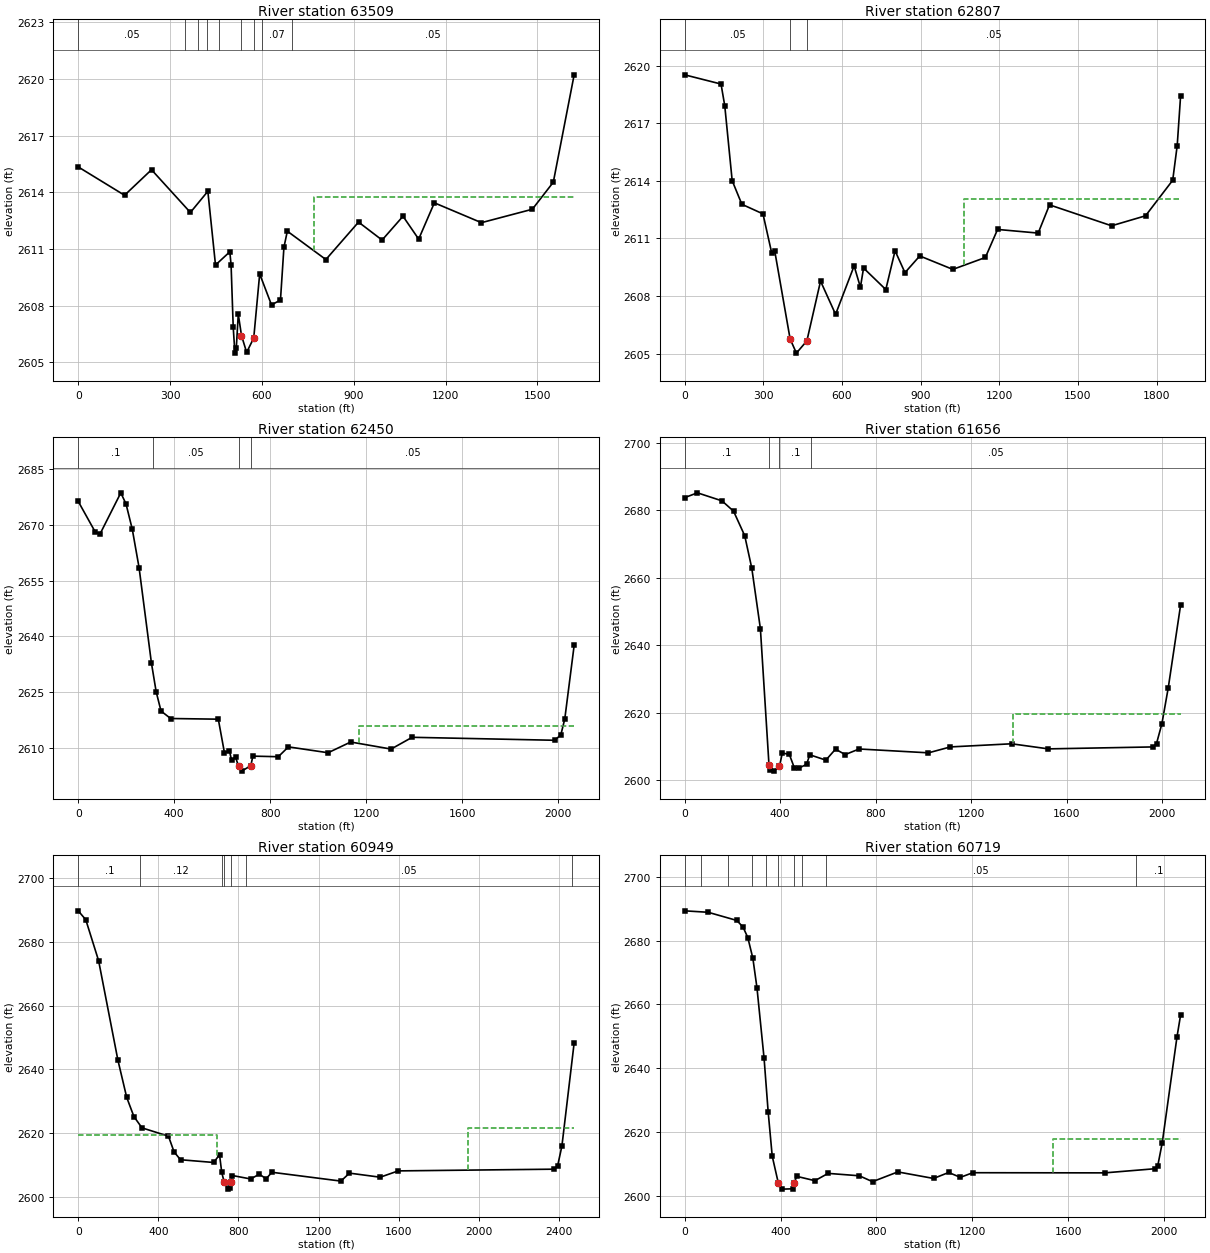
Type RM Length L Ch R = 1 ,63509   ,740.8,701.9,656.9
XS GIS Cut Line= 4
2307283.32903705531490.8876841912306874.20483372531510.049731339
2306615.02957981531263.288953638 2305816.3913012531561.130951931
#Sta/Elev= 30
       0 2615.34   151.3 2613.84   239.4 2615.19   366.4 2612.93   423.4 2614.05
   448.4 2610.15   495.2 2610.85   499.3 2610.15   506.3 2606.85   511.8 2605.49
   516.3 2605.75   522.8 2607.55   533.3 2606.42   550.1 2605.53   573.3 2606.29
   592.7 2609.68   631.3 2608.04   660.6  2608.3   671.9 2611.09     683 2611.94
   808.9 2610.44   915.6 2612.42   992.5 2611.47  1060.8 2612.73    1112 2611.52
  1163.2 2613.44  1316.9 2612.39  1483.2  2613.1  1551.7 2614.53  1619.8 2620.21
#Mann= 9 ,-1,0
       0     .05       0     350     .07       0     390     .05       0
  419.57     .07       0  459.57     .05       0   533.3     .04       0
   573.3     .08       0  599.57     .07       0  699.57     .05       0
#XS Ineff= 2 , 0
                          771.15         2613.76
Permanent Ineff=
       F       F
Bank Sta=533.3,573.3
XS Rating Curve= 0 ,0
Exp/Cntr(USF)=0,0
Exp/Cntr=0.3,0.1

Type RM Length L Ch R = 1 ,62807   ,369.1,357.1,330.1
XS GIS Cut Line= 4
2307470.51520545531190.770368913 2307214.8455255530961.458387925
2306743.04271404530982.544547095 2305744.0859233 531383.18157135
#Sta/Elev= 30
       0 2619.52   138.7 2619.04   152.9 2617.91   181.2 2614.01   218.1 2612.78
   298.7 2612.28   331.9 2610.25   343.4 2610.36   402.2 2605.77   426.2 2605.03
   466.2 2605.67   518.3 2608.78   575.7 2607.05   646.4 2609.57   670.4 2608.46
   682.4 2609.46   767.3 2608.34   802.6 2610.36   840.4 2609.22   896.8 2610.09
    1023 2609.39  1147.1 2610.01  1193.7 2611.47  1348.6 2611.28  1391.8 2612.75
  1628.7 2611.66  1758.1 2612.18  1861.8 2614.03    1879 2615.84    1892 2618.44
#Mann= 3 ,-1,0
       0     .05       0   402.2     .04       0   466.2     .05       0
#XS Ineff= 2 , 0
                         1066.67         2613.06
Permanent Ineff=
       F       F
Bank Sta=402.2,466.2
XS Rating Curve= 0 ,0
Exp/Cntr(USF)=0,0
Minor Loss Coefficient=0
Exp/Cntr=0.3,0.1

Type RM Length L Ch R = 1 ,62450   ,796.8,793.9,782.3
XS GIS Cut Line= 3
2307405.76054873530280.1467822782307089.46816116530707.141505496
2305639.79471814531210.573555709
#Sta/Elev= 30
       0 2676.35      71  2668.1    90.9 2667.57   177.4 2678.65   199.2 2675.65
   225.3 2668.82   253.5 2658.52   304.9 2632.86   324.8 2625.05     345 2619.88
   385.1 2617.87   583.6 2617.69     609 2608.71   630.1 2609.12   638.6 2606.71
   655.5 2607.43   668.2 2604.99     681  2603.7   719.1 2605.17   727.5 2607.74
   833.4 2607.58   875.7 2610.23  1040.9 2608.65  1135.1 2611.54  1303.4 2609.64
  1391.1 2612.81  1985.1 2612.01  2010.5 2613.48  2026.9 2617.73    2066 2637.56
#Mann= 4 ,-1,0
       0      .1       0     310     .05       0   668.2     .04       0
   719.1     .05       0
#XS Ineff= 2 , 0
                         1169.87         2615.93
Permanent Ineff=
       F       F
Bank Sta=668.2,719.1
XS Rating Curve= 0 ,0
Exp/Cntr(USF)=0,0
Exp/Cntr=0.3,0.1

Type RM Length L Ch R = 1 ,61656   ,730.3,707.3,687.8
XS GIS Cut Line= 2
2307138.26639311529892.7990859332305290.29481507 530840.88885206
#Sta/Elev= 30
       0 2683.73    53.4 2685.15   156.3 2682.77   204.7 2679.71   251.4 2672.46
   281.1  2662.8   317.1  2644.9     353 2604.66   357.5 2603.08   373.2 2602.71
     397 2604.11   408.9 2608.08   438.4 2607.65   459.4 2603.66   478.9 2603.62
   510.4 2604.72   523.9 2607.55   591.3 2605.97   631.7 2609.22   672.2 2607.61
   730.7 2609.27    1021 2608.13  1112.8 2609.88    1369 2610.81  1523.1  2609.3
  1962.9 2609.88    1976 2610.87  1998.6 2616.76  2025.3 2627.43    2077 2651.94
#Mann= 4 ,-1,0
       0      .1       0     353     .04       0     397      .1       0
     530     .05       0
#XS Ineff= 2 , 0
                         1373.68         2619.57
Permanent Ineff=
       F       F
Bank Sta=353,397
XS Rating Curve= 0 ,0
Exp/Cntr(USF)=0,0
Exp/Cntr=0.3,0.1

Type RM Length L Ch R = 1 ,60949   ,242.6,229.8,220
XS GIS Cut Line= 4
2307141.79889168529364.3516796432306476.52912358529407.738838432
2306299.36489186529671.6773877332305153.22078051530626.194881093
#Sta/Elev= 30
       0 2689.74    37.7 2686.96   101.8  2674.1     198 2642.95   242.1 2631.21
   278.2 2625.18   318.4 2621.65   450.6 2619.04   478.6 2614.11   510.7 2611.65
   676.6 2610.79   705.5 2613.24   716.6 2607.69  728.22 2604.76   746.3 2602.43
   757.3 2602.67   763.1 2604.74   769.6  2606.7   861.1 2605.62   904.2 2607.12
   938.2 2605.68   967.1 2607.72  1311.7 2604.95  1354.3 2607.45  1507.7 2606.17
  1597.8 2608.15  2376.7 2608.69  2393.8 2609.81    2415 2615.97  2476.1 2648.31
#Mann= 7 ,-1,0
       0      .1       0     310     .12       0  716.68      .1       0
  728.22     .04       0   763.1      .1       0  836.68     .05       0
 2464.57      .1       0
#XS Ineff= 2 , 0
          693.52 2619.51 1947.37         2621.54
Permanent Ineff=
       F       F
Bank Sta=728.22,763.1
XS Rating Curve= 0 ,0
Exp/Cntr(USF)=0,0
Exp/Cntr=0.3,0.1

Type RM Length L Ch R = 1 ,60719   ,667.6,670,681
XS GIS Cut Line= 3
2306360.83003347528984.7140402392306147.50983609529592.134263286
2305012.21251445530452.646245937
#Sta/Elev= 30
       0 2689.38    98.1 2688.92   217.4 2686.36   243.4 2684.28   263.3 2680.99
   284.5 2674.44   301.5 2665.22   331.2 2643.07   348.1 2626.37   365.1 2612.41
   390.5 2603.98   407.5 2602.06   449.9 2602.16  457.44    2604   466.8 2606.08
   543.1 2604.71   598.3    2607   728.3 2606.25   783.5  2604.4   888.9 2607.46
  1038.1 2605.41  1100.9 2607.28  1149.9 2605.76  1201.8 2607.21  1751.8 2607.16
  1963.1 2608.47    1973 2609.36  1991.7 2616.58  2053.3 2649.84  2068.4 2656.74
#Mann= 10 ,-1,0
       0      .1       0      70     .12       0     180      .1       0
     280     .12       0     340      .1       0   390.5     .04       0
  457.44     .08       0     490     .07       0     590     .05       0
 1883.79      .1       0
#XS Ineff= 2 , 0
                         1536.84         2617.79
Permanent Ineff=
       F       F
Bank Sta=390.5,457.44
XS Rating Curve= 0 ,0
Exp/Cntr(USF)=0,0
Exp/Cntr=0.3,0.1