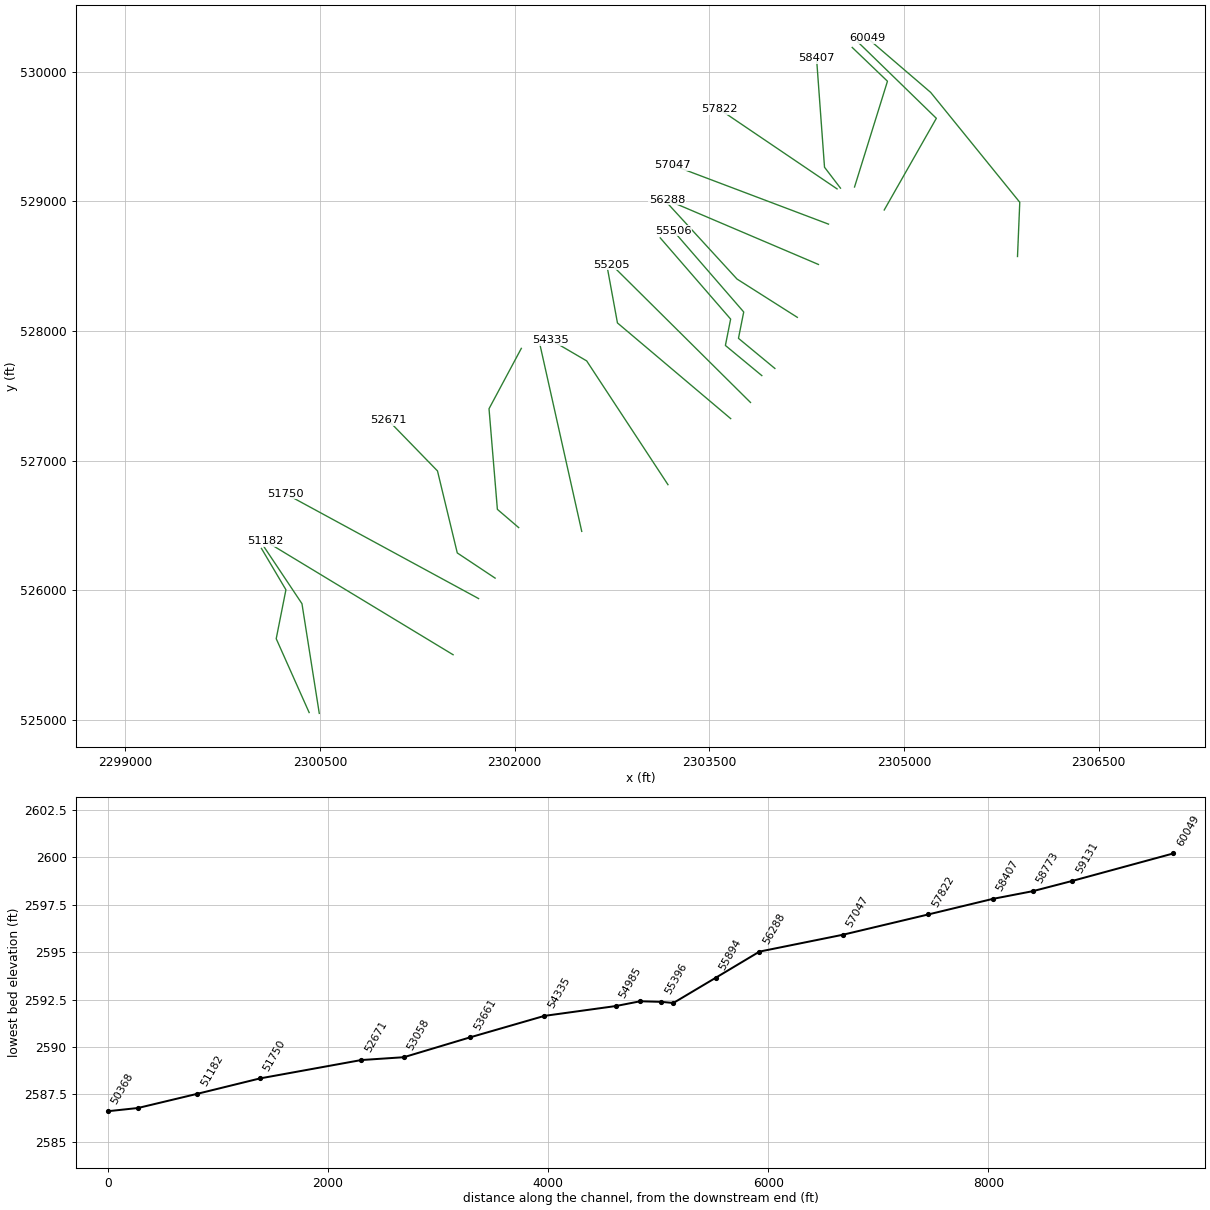
HEC-RAS study DEERCK.prj: DEERCK

--- DEERCK.g01 (geometry) --- (continued)

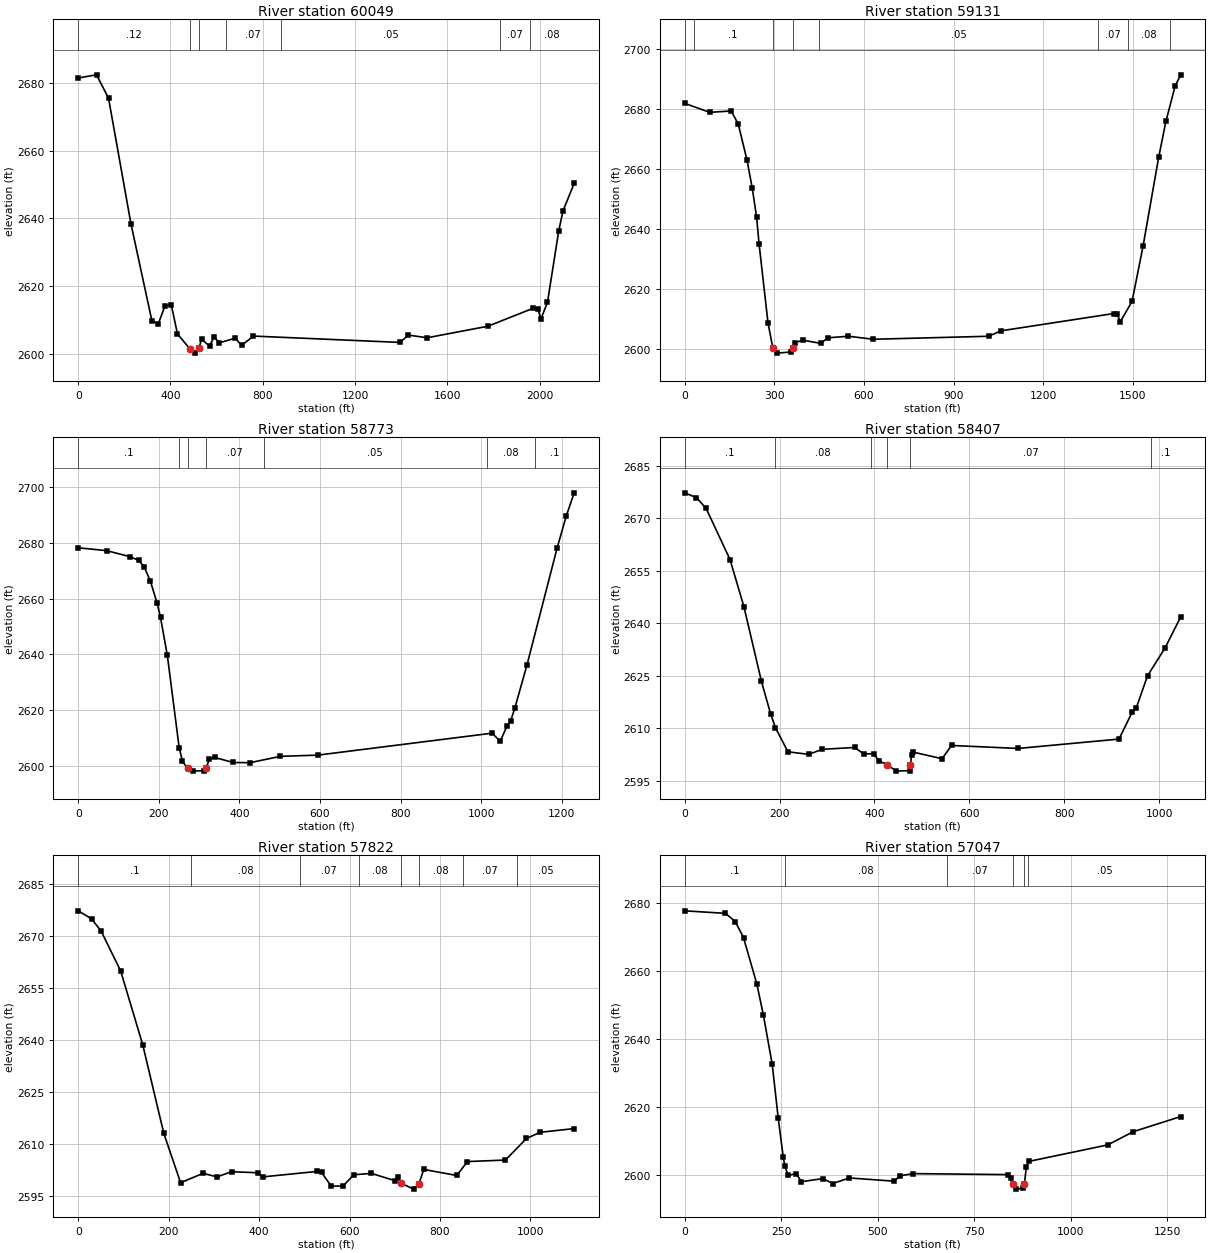
Type RM Length L Ch R = 1 ,60049   ,980.2,918.1,871.4
XS GIS Cut Line= 4
2305875.64889693528573.9166844222305893.16735685528992.176246792
2305206.43868248529839.6063662032304720.69038131530256.688290156
#Sta/Elev= 30
       0 2681.52    79.3 2682.45   131.4 2675.55   228.5 2638.45   319.5 2609.72
   347.6 2608.94   375.6  2614.1   403.3 2614.54   430.2 2605.88   483.1 2601.56
   507.4 2600.21  523.31 2601.61   534.6 2604.32   569.2 2602.29   589.8  2605.1
   610.4 2603.22   680.7 2604.64   708.2  2602.5   759.7 2605.25  1395.5 2603.37
  1430.4 2605.55  1512.4 2604.75    1776 2608.16  1971.6 2613.46  1992.1 2613.38
  2005.7  2610.3    2034 2615.24  2082.8 2636.36  2101.2 2642.23  2149.6 2650.37
#Mann= 7 ,-1,0
       0     .12       0   483.1     .04       0  523.31     .08       0
  638.63     .07       0  878.63     .05       0 1829.38     .07       0
 1959.38     .08       0
Bank Sta=483.1,523.31
XS Rating Curve= 0 ,0
Exp/Cntr(USF)=0,0
Exp/Cntr=0.3,0.1

Type RM Length L Ch R = 1 ,59131   ,345.6,357.9,363.5
XS GIS Cut Line= 3
2304848.38856814528932.6573312542305250.12151989529639.707326332
2304643.50476275530230.254765402
#Sta/Elev= 30
       0 2681.82    83.4 2678.83   155.7 2679.27   179.2 2674.96   208.5 2662.99
   226.3 2653.57   240.8 2643.87     249 2635.05   278.9  2608.8     295  2600.5
   308.8 2598.76   355.2 2599.14   361.52600.481   368.6 2602.26   396.2 2603.06
   454.9 2602.01   479.1 2603.85   548.1 2604.38     631 2603.37  1016.9 2604.37
  1058.9 2606.18  1435.6 2611.92  1446.7 2611.81  1457.9 2609.19  1497.3 2615.97
  1534.1 2634.33  1586.3 2663.86  1610.5  2675.8  1641.1 2687.46  1659.8  2691.3
#Mann= 8 ,-1,0
       0     .05       0      30      .1       0     295     .04       0
   361.5      .1       0     450     .05       0 1383.21     .07       0
 1483.21     .08       0 1623.21      .1       0
Bank Sta=295,361.5
XS Rating Curve= 0 ,0
Exp/Cntr(USF)=0,0
Exp/Cntr=0.3,0.1

Type RM Length L Ch R = 1 ,58773   ,345.3,366.2,382
XS GIS Cut Line= 3
2304619.52130553529110.0063601332304873.36393124529925.843287814
2304601.77705817530186.299877929
#Sta/Elev= 30
       0 2678.17    70.3 2677.16     129 2674.98     150 2673.68   163.8 2671.34
   179.3 2666.13     196 2658.25   204.2 2653.24   221.2 2639.63   250.5 2606.65
   258.7  2601.7   271.4 2599.22     284 2598.22   313.3 2598.39   317.5 2599.35
   325.3 2602.45   338.3 2603.12   384.5 2601.31   426.4 2601.24   501.8 2603.52
   594.1 2603.94  1027.4 2611.81  1047.2 2608.85  1064.1 2614.44  1073.1  2616.2
  1083.3  2620.7  1113.5 2636.16  1188.6  2678.2  1211.2 2689.58  1230.7 2697.85
#Mann= 7 ,-1,0
       0      .1       0     250     .07       0   271.4     .04       0
   317.5     .07       0     460     .05       0 1014.42     .08       0
 1134.42      .1       0
Bank Sta=271.4,317.5
XS Rating Curve= 0 ,0
Exp/Cntr(USF)=0,0
Exp/Cntr=0.3,0.1

Type RM Length L Ch R = 1 ,58407   ,538.4,585,609.3
XS GIS Cut Line= 3
2304511.16187646529101.2204604782304388.15928129529262.295287482
2304326.65798371530102.813021119
#Sta/Elev= 30
       0 2677.33    24.9 2675.95    45.2 2672.89    95.6 2658.25   124.8 2644.82
   161.9 2623.43   181.1 2614.18   191.2 2610.27   217.6 2603.34   261.4  2602.6
   289.8 2604.04     358 2604.57     378  2602.7   398.1 2602.81   410.1 2600.67
   426.5 2599.67   446.2 2597.81   474.3 2597.95  475.96 2599.56   478.3 2602.32
   482.3 2603.22   542.5 2601.35   562.5 2605.14   702.9 2604.29   915.5 2606.97
   943.5 2614.73   951.5 2615.73   975.6 2625.04  1012.6 2633.02  1045.4 2641.83
#Mann= 6 ,-1,0
       0      .1       0     190     .08       0  392.67     .07       0
   426.5     .04       0  475.96     .07       0  982.67      .1       0
Bank Sta=426.5,475.96
XS Rating Curve= 0 ,0
Exp/Cntr(USF)=0,0
Exp/Cntr=0.3,0.1

Type RM Length L Ch R = 1 ,57822   ,757.4,775.1,774.6
XS GIS Cut Line= 2
2304484.80417749529095.3631940422303576.92787984529710.376169874
#Sta/Elev= 30
       0 2677.15    29.7 2674.82    50.7  2671.3    93.9 2659.83   142.9 2638.46
   189.2 2613.07   226.4 2598.83   276.1 2601.54   307.1 2600.51     339 2602.01
   396.9 2601.71   407.9 2600.51   527.4 2602.08   538.1 2601.78   559.5 2597.86
   585.4 2597.88   609.5 2601.13   648.2 2601.52   701.3 2599.39   706.1 2600.57
   713.2 2598.71     742 2596.99   753.4 2598.52   764.1 2602.66     837 2600.92
   860.7 2604.93   944.7 2605.37   991.2 2611.58  1021.4 2613.36  1096.6 2614.43
#Mann= 8 ,-1,0
       0      .1       0     250     .08       0     490     .07       0
     620     .08       0   713.2     .04       0   753.4     .08       0
     850     .07       0     970     .05       0
Bank Sta=713.2,753.4
XS Rating Curve= 0 ,0
Exp/Cntr(USF)=0,0
Exp/Cntr=0.3,0.1

Type RM Length L Ch R = 1 ,57047   ,767.5,758.5,752.4
XS GIS Cut Line= 2
2304418.85335555528823.5733112672303217.81480347529277.889705212
#Sta/Elev= 30
       0  2677.8   105.5 2677.06   131.2 2674.64   152.3 2669.91   186.8  2656.3
   203.9 2647.06   226.7 2632.61   242.2 2616.81   255.2 2605.37   259.5 2602.63
     268 2599.94   288.8 2600.51   302.2  2598.1   357.8 2599.03   383.5 2597.57
   426.2 2599.21   541.7 2598.26   558.8 2599.87   592.4 2600.48   836.8 2600.19
   845.4  2599.3   850.4  2597.3   858.2 2595.92   875.1  2596.2   879.6 2597.35
   884.5 2602.39   892.4 2604.11  1095.5 2608.93  1161.8 2612.84  1284.1 2617.26
#Mann= 6 ,-1,0
       0      .1       0     260     .08       0     680     .07       0
   850.4     .04       0   879.6     .07       0     890     .05       0
Bank Sta=850.4,879.6
XS Rating Curve= 0 ,0
Exp/Cntr(USF)=0,0
Exp/Cntr=0.3,0.1

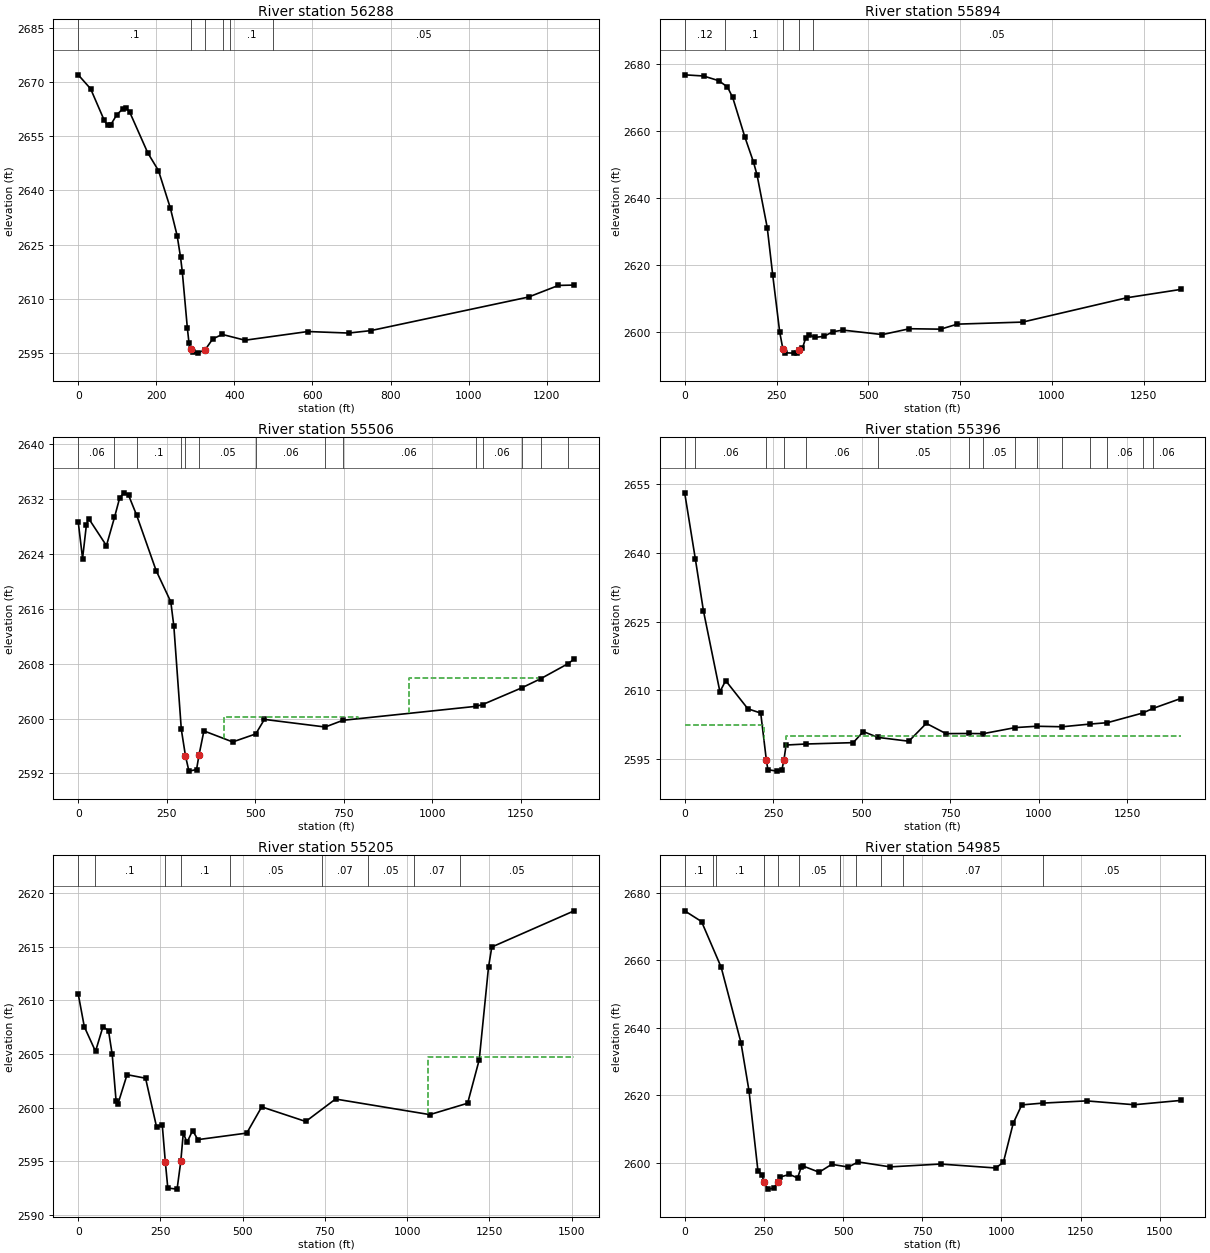
Type RM Length L Ch R = 1 ,56288   ,400.8,394.6,386.3
XS GIS Cut Line= 2
 2304341.3011498528512.5651836112303172.77649572529010.432830713
#Sta/Elev= 30
       0 2671.98    31.7 2668.13    66.4 2659.46    75.1 2657.97    83.2 2658.16
    98.9 2660.95   114.3 2662.59     123 2662.72   131.7 2661.71   178.2 2650.39
   205.6 2645.49     236 2635.12   253.4  2627.5   262.1 2621.54   266.6 2617.51
   279.5 2601.99   283.8 2597.76   287.9 2596.14     294 2595.23   306.2 2595.03
   325.42596.013   344.7 2598.97   368.9  2600.2   427.3  2598.6   588.2    2601
   692.5 2600.58   749.1 2601.25  1153.4 2610.54    1230 2613.75  1270.2 2613.85
#Mann= 6 ,-1,0
       0      .1       0   287.9     .04       0   325.4      .1       0
     370     .07       0     390      .1       0     500     .05       0
Bank Sta=287.9,325.4
XS Rating Curve= 0 ,0
Exp/Cntr(USF)=0,0
Exp/Cntr=0.3,0.1

Type RM Length L Ch R = 1 ,55894   ,392,387.7,382.8
XS GIS Cut Line= 3
2304178.51899647528104.6108980812303713.62951894528400.049225196
2303173.54098355528989.325899925
#Sta/Elev= 30
       0 2676.69    51.4 2676.34    92.8 2674.94   116.5 2673.05   130.7 2669.94
   163.9 2658.12   187.6 2650.57   197.1 2646.76   224.8 2631.09   239.7 2616.95
   258.7 2599.94   267.52594.812   272.9 2593.75   297.7 2593.66   306.4 2593.75
   312.2 2594.59   320.3 2595.06   329.8 2598.25   338.3 2599.21   353.5 2598.34
   378.8 2598.66   403.8 2600.05     431 2600.53   538.3 2599.19     612 2600.94
     697 2600.81   742.3 2602.31     920 2602.92  1203.8 2610.18  1350.2 2612.66
#Mann= 5 ,-1,0
       0     .12       0     110      .1       0   267.5     .04       0
   312.2      .1       0     350     .05       0
Bank Sta=267.5,312.2
XS Rating Curve= 0 ,0
Exp/Cntr(USF)=0,0
Exp/Cntr=0.5,0.3

Type RM Length L Ch R = 1 ,55506   ,110.8,109.9,108.2
XS GIS Cut Line= 4
2304005.62286378527710.3847927542303724.85358299527942.767543995
2303765.36371972528146.0951743582303222.58710184528772.526564157
#Sta/Elev= 30
       0 2628.72    12.3 2623.35    23.2  2628.3    29.5 2629.19    79.7 2625.23
   102.4 2629.35   117.3 2632.24   129.9 2632.94   142.1 2632.61   164.9 2629.69
     220  2621.6   261.5 2617.03   270.1 2613.48   291.2 2598.41     303 2594.52
   312.7 2592.32   334.2 2592.55   341.1 2594.65     355 2598.19   436.3 2596.58
   501.5 2597.75   525.8 2599.87   697.6 2598.76   747.8 2599.74  1122.1 2601.77
  1141.9 2602.03  1252.5 2604.47  1306.6 2605.82    1383 2607.99  1400.7 2608.67
#Mann= 14 ,-1,0
       0     .06       0   102.4     .12       0   164.9      .1       0
   291.2     .05       0     303     .04       0   341.1     .05       0
   501.5     .06       0   697.6     .05       0   747.8     .06       0
  1122.1     .05       0  1141.9     .06       0  1252.5     .05       0
  1306.6     .06       0    1383     .05       0
#XS Ineff= 3 ,-1
       0     235  2602.5   411.6  790.892600.162  934.55 1299.67 2605.85
Permanent Ineff=
       F       F       F
Bank Sta=303,341.1
XS Rating Curve= 0 ,0
Exp/Cntr(USF)=0,0
Minor Loss Coefficient=0
Exp/Cntr=0.5,0.3

Type RM Length L Ch R = 1 ,55396   ,197.6,191.7,187.4
XS GIS Cut Line= 4
 2303904.8388761527655.3626480142303624.06959531527887.745399255
2303664.57973204528091.0730296182303121.80311416528717.504419417
#Sta/Elev= 30
       0 2653.16    30.2 2638.67      53 2627.38    99.5 2609.72   115.8 2612.14
   178.5 2605.99   214.8 2605.06   230.6 2594.84     235 2592.69   260.5 2592.38
   274.5 2592.66   280.2 2594.75   286.4 2598.08   341.6  2598.3     476  2598.6
   504.6 2601.02   545.4 2599.75   633.1 2598.91   682.4 2602.81     738 2600.57
   802.2  2600.6     843 2600.56   933.7 2601.89   993.9 2602.18  1066.8 2602.07
  1143.5 2602.65  1193.8 2602.96  1293.2 2605.06  1322.2 2606.06  1400.7 2608.23
#Mann= 15 ,-1,0
       0     .12       0    30.2     .06       0   230.6     .04       0
   280.2      .1       0   341.6     .06       0   545.4     .05       0
   802.2     .06       0     843     .05       0   933.7     .06       0
   993.9     .05       0  1066.8     .06       0  1143.5     .05       0
  1193.8     .06       0  1293.2     .05       0  1322.2     .06       0
#XS Ineff= 2 , 0
             225  2602.5     285            2600
Permanent Ineff=
       F       F
Bank Sta=230.6,280.2
XS Rating Curve= 0 ,0
Exp/Cntr(USF)=0,0
Minor Loss Coefficient=0
Exp/Cntr=0.5,0.3

Type RM Length L Ch R = 1 ,55205   ,216,219.5,223.1
XS GIS Cut Line= 2
2303817.53709582527448.1243557432302747.30258519528510.411580406
#Sta/Elev= 30
       0 2610.59    18.5 2607.54    52.6 2605.24    75.2 2607.54    92.1 2607.17
   103.4 2604.95   115.1 2600.64   120.7 2600.34   148.5 2603.07   204.8 2602.74
   238.6 2598.15   255.5 2598.41   264.8 2594.97   272.4 2592.51   300.6 2592.41
   311.9    2595   319.5 2597.64   330.8 2596.76   347.9 2597.87   363.8 2597.02
   512.5 2597.63   557.9 2600.07   691.8 2598.71   782.4  2600.8    1069 2599.35
    1184 2600.41  1219.3 2604.46  1247.5 2613.08  1257.5 2614.96  1507.9 2618.33
#Mann= 9 ,-1,0
       0     .12       0      50      .1       0   264.8     .04       0
   311.9      .1       0     460     .05       0     740     .07       0
     880     .05       0    1020     .07       0    1160     .05       0
#XS Ineff= 2 , 0
                         1064.42         2604.76
Permanent Ineff=
       F       F
Bank Sta=264.8,311.9
XS Rating Curve= 0 ,0
Exp/Cntr(USF)=0,0
Minor Loss Coefficient=0
Exp/Cntr=0.3,0.1

Type RM Length L Ch R = 1 ,54985   ,663.9,650,638.4
XS GIS Cut Line= 3
2303664.78687638527323.5400970022302792.05417735   528061.555668
2302715.90971367528477.421584991
#Sta/Elev= 30
       0 2674.63    53.2 2671.45   115.1 2657.94   177.6 2635.61   203.1 2621.28
   231.3 2597.57   244.1 2596.44   250.3 2594.18   262.7 2592.16   281.3 2592.43
   293.7 2594.37   299.9  2595.7   330.9 2596.53   356.4 2595.47   367.7 2598.59
   374.2 2598.99   424.5 2597.17   464.2 2599.51   516.7  2598.7   547.7 2600.22
   648.7 2598.75   807.7 2599.59   981.3 2598.43  1006.1 2600.07  1037.1 2611.65
  1064.2 2617.12    1130 2617.65  1268.6 2618.31  1419.1 2617.17  1565.7 2618.44
#Mann= 11 ,-1,0
       0      .1       0      90     .12       0     100      .1       0
   250.3     .04       0   293.7      .1       0     360     .05       0
     490     .03       0     540     .05       0     620     .03       0
     690     .07       0    1130     .05       0
Bank Sta=250.3,293.7
XS Rating Curve= 0 ,0
Exp/Cntr(USF)=0,0
Exp/Cntr=0.3,0.1

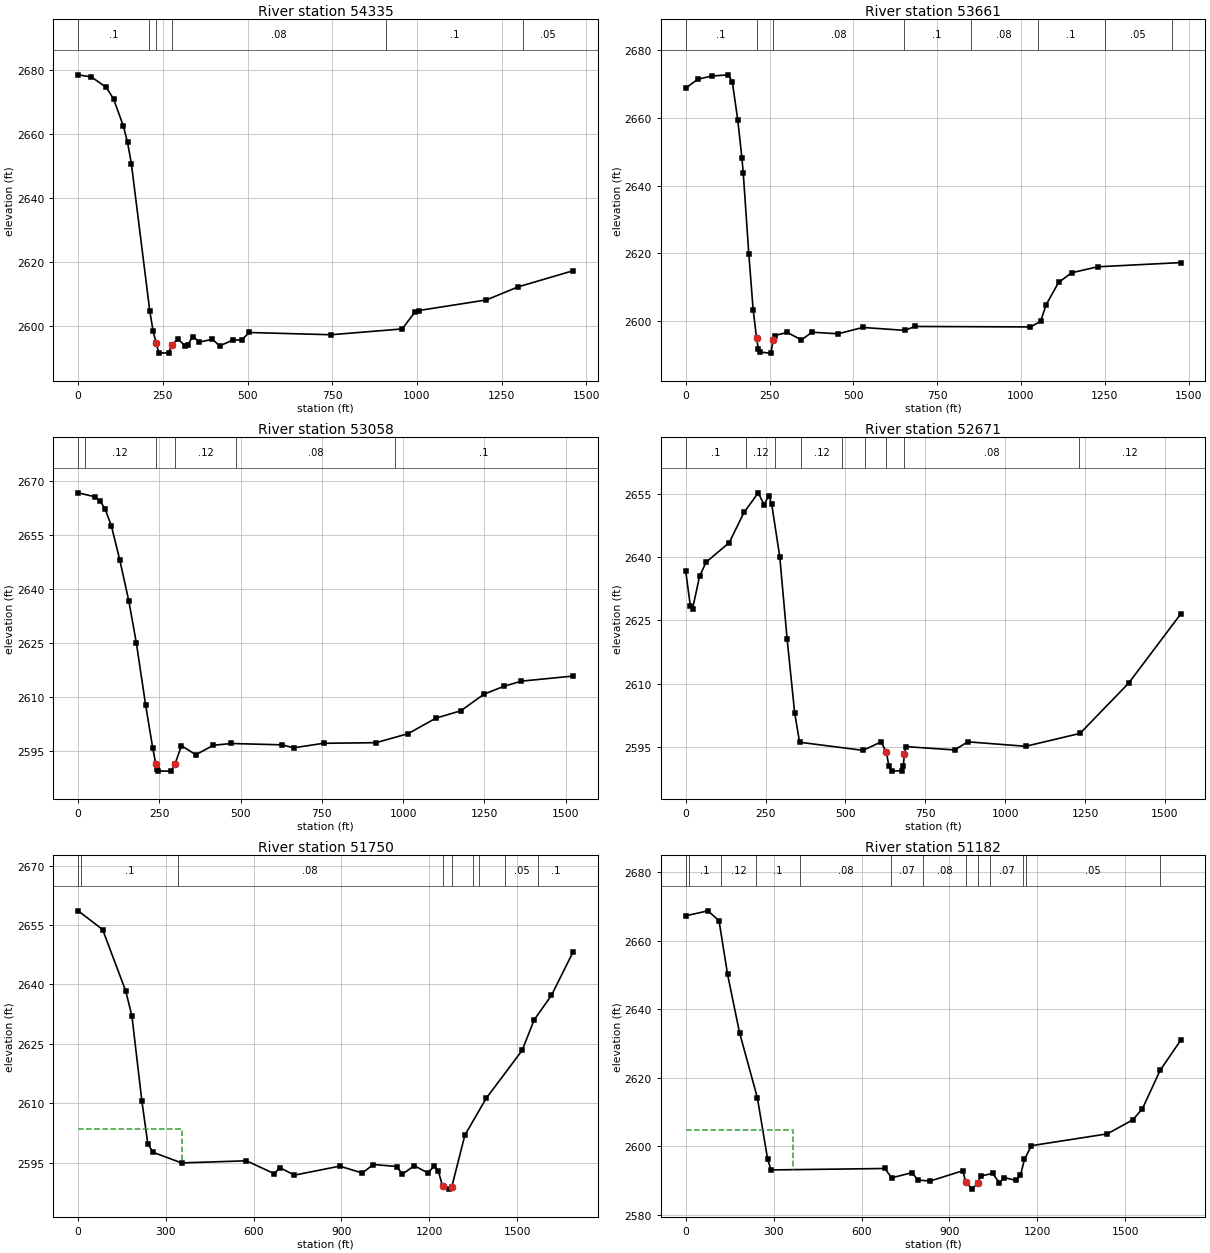
Type RM Length L Ch R = 1 ,54335   ,689.9,673.8,658.1
XS GIS Cut Line= 3
2303181.56239537526813.9579170272302554.83488667527768.692346175
2302279.54336415527929.767173179
#Sta/Elev= 30
       0 2678.51      39 2677.85    82.7 2674.62   104.4 2671.02   133.3 2662.56
   145.7 2657.46     157 2650.82   211.3 2604.87   221.2 2598.52   230.3 2594.77
   238.3 2591.75     267 2591.64   276.6 2594.31   295.1 2595.99   314.9    2594
   323.2 2594.22   338.4 2596.81   357.9 2595.12   396.1 2595.94     418 2593.91
   456.8 2595.73   482.3 2595.77   505.5 2598.08   745.7 2597.38   956.6 2599.19
   994.1 2604.45  1005.7 2604.94  1205.4 2608.25  1298.1  2612.3    1461 2617.36
#Mann= 6 ,-1,0
       0      .1       0     210     .08       0   230.3     .04       0
   276.6     .08       0     910      .1       0 1312.06     .05       0
Bank Sta=230.3,276.6
XS Rating Curve= 0 ,0
Exp/Cntr(USF)=0,0
Exp/Cntr=0.3,0.1

Type RM Length L Ch R = 1 ,53661   ,609.5,603.2,597.9
XS GIS Cut Line= 2
2302516.76265483526453.7360311822302194.61300082 527894.62357456
#Sta/Elev= 30
       0 2668.86    36.3 2671.47    77.1  2672.4   126.5 2672.77   138.8 2670.73
   155.2 2659.41   167.5 2648.22   171.6 2643.66     188 2619.95     201 2603.37
  211.42 2594.84   216.7 2591.72   220.8  2590.8   253.6 2590.51   261.12594.431
   265.8 2595.72   302.7 2596.62   345.1 2594.43   376.5 2596.69   454.4 2596.23
   528.2  2598.1   653.1 2597.24   683.9 2598.39  1028.4 2598.25  1058.6  2599.9
  1075.3 2604.86  1112.2 2611.39  1151.2 2614.26  1229.1 2616.03  1476.5 2617.27
#Mann= 8 ,-1,0
       0      .1       0  211.42     .04       0   261.1     .08       0
     650      .1       0     850     .08       0    1050      .1       0
    1250     .05       0    1450      .1       0
Bank Sta=211.42,261.1
XS Rating Curve= 0 ,0
Exp/Cntr(USF)=0,0
Exp/Cntr=0.3,0.1

Type RM Length L Ch R = 1 ,53058   ,379.9,387.2,395
XS GIS Cut Line= 4
 2302030.6095406526483.0223633652301866.60608038 526623.59675784
2301802.17614958527399.6845606762302051.10997313527865.337242378
#Sta/Elev= 30
       0 2666.81    50.6 2665.73    66.4 2664.61    82.7 2662.41   102.5 2657.51
   128.1 2648.12     156 2636.69   179.1 2625.04   207.5 2607.89   229.6 2595.79
  239.32 2591.34   241.7 2590.01   245.7  2589.5   285.8 2589.46   297.6 2591.36
   317.9  2596.5   362.1 2594.03   416.1 2596.64   470.5 2597.14     627 2596.77
   663.1 2595.94   755.4  2597.2   916.5 2597.36  1015.1 2599.87  1100.8 2604.19
  1177.6 2606.24  1248.6 2610.84  1309.4 2613.02  1363.8 2614.47  1522.8 2615.88
#Mann= 6 ,-1,0
       0      .1       0      20     .12       0  239.32     .04       0
   297.6     .12       0  486.01     .08       0  976.01      .1       0
Bank Sta=239.32,297.6
XS Rating Curve= 0 ,0
Exp/Cntr(USF)=0,0
Exp/Cntr=0.3,0.1

Type RM Length L Ch R = 1 ,52671   ,889.5,920.9,944.1
XS GIS Cut Line= 4
2301849.10795706526093.2400968062301557.44769865526287.450793531
2301404.95853754526919.8943528792301022.72084774527313.298999187
#Sta/Elev= 30
       0  2636.6    14.3 2628.48    21.5 2627.81    43.2 2635.43    63.6 2638.78
   136.2 2643.42   182.4 2650.57     227 2655.21   245.3 2652.37   259.7 2654.52
   268.9 2652.62   294.3 2640.08   317.4 2620.56     341  2603.1   356.4 2596.15
   555.1 2594.23   611.4 2596.22   628.1  2593.8   636.1 2590.44   644.6 2589.31
   677.2 2589.42   681.4 2590.63   684.4 2593.36   689.6 2595.11   841.8 2594.33
     883 2596.25  1064.1 2595.19  1234.4 2598.24  1386.7 2610.15  1549.5  2626.5
#Mann= 9 ,-1,0
       0      .1       0     190     .12       0     280      .1       0
   360.4     .12       0   490.4      .1       0   560.4     .08       0
   628.1     .04       0   684.4     .08       0 1230.97     .12       0
Bank Sta=628.1,684.4
XS Rating Curve= 0 ,0
Exp/Cntr(USF)=0,0
Exp/Cntr=0.3,0.1

Type RM Length L Ch R = 1 ,51750   ,570.8,567.6,560.2
XS GIS Cut Line= 2
2301721.61790665525935.5609364492300235.20598518526743.044169469
#Sta/Elev= 30
       0 2658.58    83.6 2653.85   162.6 2638.34   183.7 2632.04   217.6 2610.66
   238.2  2599.7   256.6 2597.62   353.3 2594.96   575.2 2595.49   670.8 2592.22
     689 2593.79   739.1 2591.87   893.9 2594.14   971.2 2592.41  1008.9 2594.55
  1089.6 2594.05  1107.8 2592.09  1148.8 2594.25  1194.3 2592.48  1217.1 2594.08
  1230.7 2593.03  1245.3 2589.11  1267.1 2588.34  1277.1 2588.95  1321.8 2601.97
  1394.8 2611.27  1517.5 2623.36  1558.5 2631.05  1617.6 2637.24  1691.6  2648.2
#Mann= 9 ,-1,0
       0     .06       0      10      .1       0     340     .08       0
  1245.3     .04       0  1277.1     .08       0    1350     .05       0
    1370     .08       0    1460     .05       0    1570      .1       0
#XS Ineff= 2 , 0
          356.21  2603.4
Permanent Ineff=
       F       F
Bank Sta=1245.3,1277.1
XS Rating Curve= 0 ,0
Exp/Cntr(USF)=0,0
Exp/Cntr=0.3,0.1

Type RM Length L Ch R = 1 ,51182   ,573.7,540.4,502
XS GIS Cut Line= 2
2301525.25760861525502.2556389422300080.46522094526377.591567507
#Sta/Elev= 30
       0 2667.27    75.7 2668.72   113.6 2665.83   142.7 2650.22   183.5  2633.2
   244.5 2614.17   279.6 2596.18   291.2 2593.13   679.4 2593.55   702.8 2590.84
   772.9 2592.34   791.7  2590.2   833.7 2589.88     946  2592.9   955.3  2589.6
   978.3 2587.53   996.5 2589.42  1007.7 2591.39  1047.8  2592.1  1070.9 2589.28
  1086.3 2590.91  1128.4 2590.05  1142.4 2591.59  1156.2 2596.22  1179.8 2600.21
  1438.7 2603.65  1525.9 2607.74  1558.7 2610.98  1619.3  2622.2  1689.3 2630.94
#Mann= 13 ,-1,0
       0     .12       0      10      .1       0     120     .12       0
     240      .1       0     390     .08       0     700     .07       0
     810     .08       0   955.3     .04       0   996.5     .08       0
    1040     .07       0    1150     .08       0    1160     .05       0
    1620      .1       0
#XS Ineff= 2 , 0
          367.58  2604.9
Permanent Ineff=
       F       F
Bank Sta=955.3,996.5
XS Rating Curve= 0 ,0
Exp/Cntr(USF)=0,0
Exp/Cntr=0.3,0.1

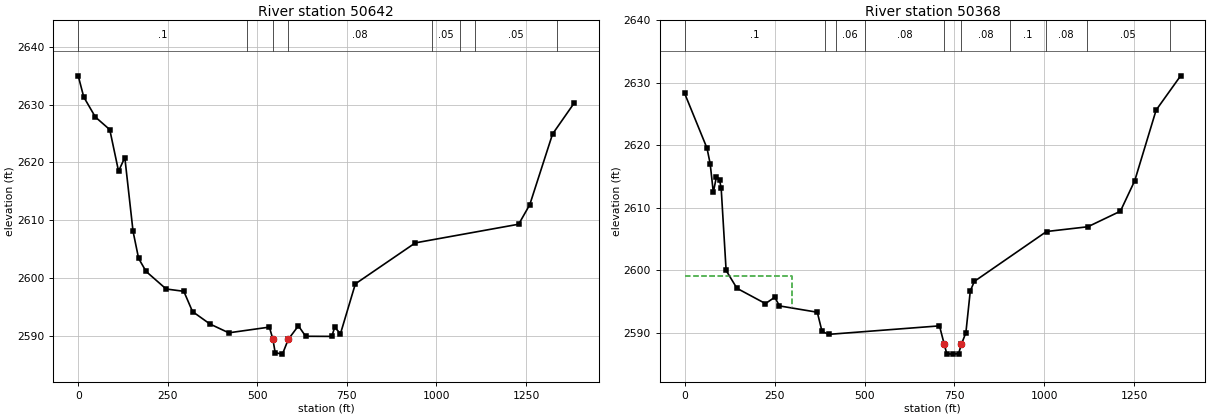
Type RM Length L Ch R = 1 ,50642   ,285.7,273.8,258.7
XS GIS Cut Line= 3
 2300493.7279084525049.9445085682300360.31239513525895.994104951
 2300067.4490733526335.289087688
#Sta/Elev= 30
       0 2634.98    15.4 2631.32    47.8 2627.85    88.1 2625.66   112.6 2618.47
   130.1 2620.83   153.1 2608.04   168.6 2603.36   189.5  2601.1   245.5 2598.06
   294.8 2597.66   319.1 2594.15   367.7    2592   420.3 2590.47   533.7 2591.46
  543.39 2589.38   549.9 2587.03   570.2 2586.78   586.4 2589.34   614.7 2591.68
     635 2589.87   707.9 2589.85     716 2591.42   732.2 2590.33   773.7 2598.95
   941.1 2606.05  1229.6 2609.28  1260.6 2612.66  1324.2  2624.9  1384.5 2630.26
#Mann= 8 ,-1,0
       0      .1       0     470     .08       0  543.39     .04       0
   586.4     .08       0   986.5     .05       0  1066.5     .08       0
  1106.5     .05       0  1336.5      .1       0
Bank Sta=543.39,586.4
XS Rating Curve= 0 ,0
Exp/Cntr(USF)=0,0
Exp/Cntr=0.3,0.1

Type RM Length L Ch R = 1 ,50368   ,210.6,247.2,286.1
XS GIS Cut Line= 4
2300415.63102258525056.4525823872300161.81614367 525625.90904149
2300236.65899258526003.3773229542300047.92485185526322.272940052
#Sta/Elev= 30
       0  2628.3    62.1 2619.54    70.9 2617.06    79.6 2612.49    88.4    2615
    97.1 2614.46   101.5 2613.11   115.2 2599.99   145.3 2597.14   224.6 2594.69
   250.4 2595.71   263.6 2594.32   368.7 2593.31   381.8 2590.25     400 2589.77
   708.4 2591.13   721.3 2588.26   728.7 2586.67   745.1 2586.61   761.4 2586.69
   769.62588.222   781.8 2590.04     794 2596.69   805.2 2598.24    1006 2606.22
  1120.9 2606.98  1211.4 2609.47  1251.2 2614.34  1310.7 2625.64  1378.8 2631.12
#Mann= 10 ,-1,0
       0      .1       0     390     .08       0     420     .06       0
     500     .08       0   721.3     .04       0   769.6     .08       0
  903.46      .1       0 1003.46     .08       0 1118.28     .05       0
 1348.28      .1       0
#XS Ineff= 2 , 0
          297.65 2599.11
Permanent Ineff=
       F       F
Bank Sta=721.3,769.6
XS Rating Curve= 0 ,0
Exp/Cntr(USF)=0,0
Exp/Cntr=0.5,0.3