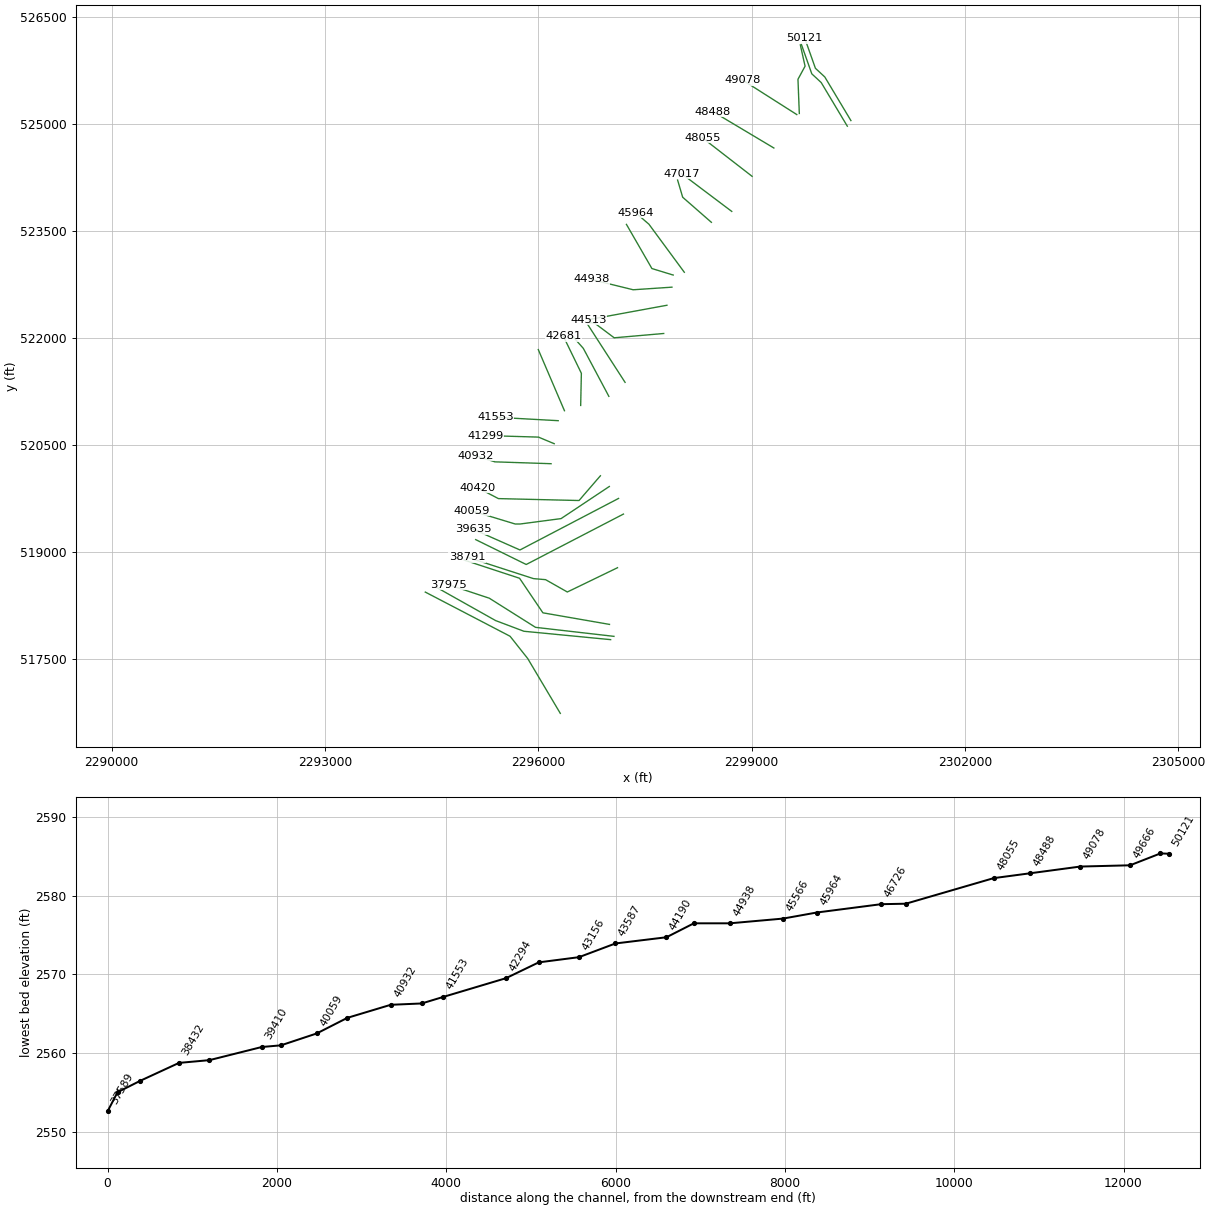
HEC-RAS study DEERCK.prj: DEERCK

--- DEERCK.g01 (geometry) --- (continued)

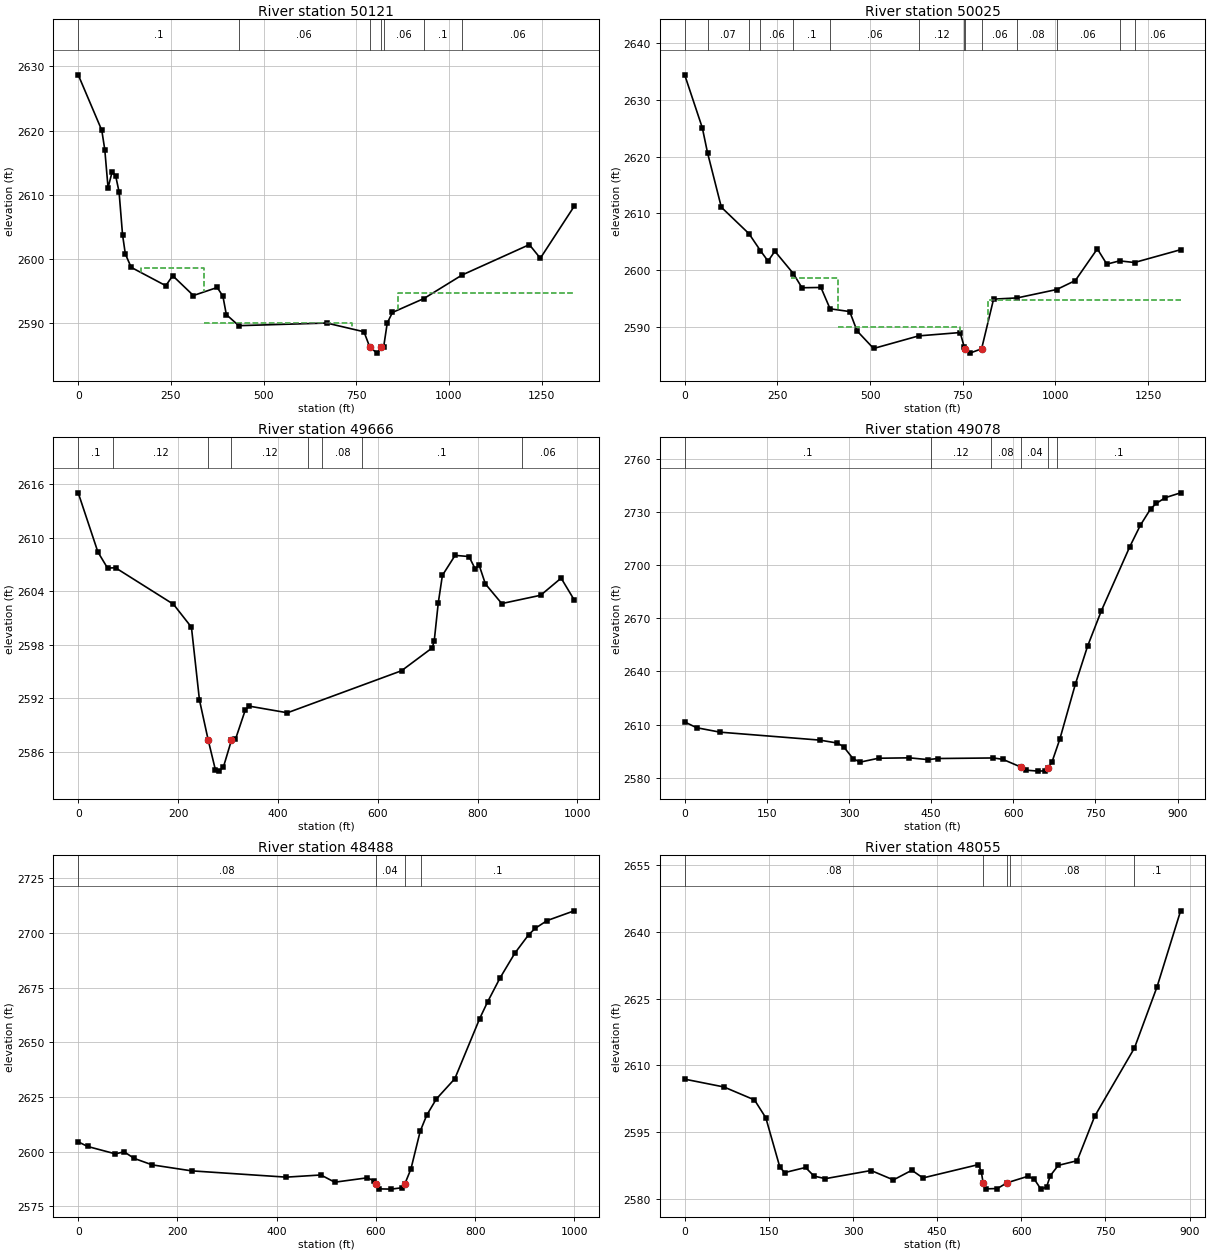
Type RM Length L Ch R = 1 ,50121   ,103.1,96.1,97.5
XS GIS Cut Line= 4
2300396.10680113525046.6904716592300028.40063039525658.449410582
2299896.57885475525779.907064282 2299747.5589991526199.079007795
#Sta/Elev= 30
       0 2628.69    63.6 2620.04    71.7 2617.02    80.5 2611.09    91.6 2613.58
   100.9 2612.97   110.2 2610.45   119.6 2603.76   127.1 2600.77   142.9 2598.68
   236.3 2595.82   254.9 2597.38   310.7 2594.29   374.9 2595.54   390.3  2594.2
   399.6 2591.31   433.2 2589.59   670.3    2590   770.9 2588.64   786.6 2586.24
   806.3 2585.31   817.8 2586.21     824 2586.28   833.7 2590.01   847.7 2591.65
   932.6 2593.82  1035.3 2597.48    1217 2602.22  1246.7  2600.1  1337.9 2608.19
#Mann= 7 ,-1,0
       0      .1       0   433.2     .06       0   786.6     .04       0
   817.8     .08       0     824     .06       0   932.6      .1       0
  1035.3     .06       0
#XS Ineff= 4 ,-1
       0  169.74    2590  169.74  338.272598.506  338.27   737.5    2590
   862.5  1337.9  2594.7
Permanent Ineff=
       F       F       F       F
Bank Sta=786.6,817.8
XS Rating Curve= 0 ,0
Exp/Cntr(USF)=0,0
Exp/Cntr=0.5,0.3

Type RM Length L Ch R = 1 ,50025   ,393,358.8,329.9
XS GIS Cut Line= 4
2300345.53209626 524968.402491622299977.82592552525580.161430543
2299846.00414989525701.6190842432299696.98429423526120.791027756
#Sta/Elev= 30
       0 2634.43    47.6 2625.08    61.6  2620.7    98.9 2611.08   173.5 2606.41
   204.5 2603.41   224.9 2601.58   243.3 2603.32     293 2599.39   316.4 2596.88
   367.6 2596.93   392.2 2593.17   445.2 2592.68     465 2589.27   509.6 2586.17
   631.2 2588.39   743.2 2588.98   754.1 2586.44   755.32586.138   769.4 2585.35
     8012586.111   833.3 2594.87   897.2 2595.09  1003.7 2596.57  1053.8 2598.15
  1113.2 2603.74  1138.8 2601.04  1173.1 2601.62  1213.5 2601.33  1337.9 2603.59
#Mann= 14 ,-1,0
       0     .06       0    61.6     .07       0   173.5      .1       0
   204.5     .06       0     293      .1       0   392.2     .06       0
   631.2     .12       0   754.1     .06       0   755.3     .04       0
     801     .06       0   897.2     .08       0  1003.7     .06       0
  1173.1      .1       0  1213.5     .06       0
#XS Ineff= 4 ,-1
       0  287.79    2590  287.79   414.9 2598.68   414.9   742.5    2590
   817.5  1337.9  2594.7
Permanent Ineff=
       F       F       F       F
Bank Sta=755.3,801
XS Rating Curve= 0 ,0
Exp/Cntr(USF)=0,0
Exp/Cntr=0.5,0.3

Type RM Length L Ch R = 1 ,49666   ,542.3,588.5,628.8
XS GIS Cut Line= 4
2299670.48323665525146.5446027052299651.42449076525625.395593131
2299751.48290667525808.8360222982299684.77729606526106.628926792
#Sta/Elev= 30
       0 2615.03    39.4  2608.4    58.7  2606.6    74.7 2606.63   190.8 2602.54
   226.8 2599.97   242.8 2591.83   260.3 2587.34   274.9 2583.96   282.9 2583.84
   290.9 2584.31   306.9  2587.3   314.9 2587.39   334.9 2590.73   342.9 2591.12
     419 2590.38   647.6 2595.09     709 2597.65   713.1 2598.42   721.2 2602.69
   729.5 2605.78   754.9 2608.02   782.8 2607.89   795.1 2606.51   803.3 2606.89
   815.6 2604.82   848.4 2602.62   926.3 2603.55   967.3 2605.47   993.4 2603.04
#Mann= 8 ,-1,0
       0      .1       0      70     .12       0   260.3     .04       0
   306.9     .12       0     460      .1       0  489.23     .08       0
  569.23      .1       0  888.18     .06       0
Bank Sta=260.3,306.9
XS Rating Curve= 0 ,0
Exp/Cntr(USF)=0,0
Exp/Cntr=0.3,0.1

Type RM Length L Ch R = 1 ,49078   ,588.2,589.2,590.1
XS GIS Cut Line= 2
2299634.66216438525131.2954312982298869.96349073525616.146930763
#Sta/Elev= 30
       0 2611.46    21.9  2608.2    64.5  2605.7   246.6 2601.21   278.5 2599.56
   290.1  2597.5   307.5  2590.7   320.3 2588.76   353.9 2590.96   410.3 2591.19
   444.2 2590.19   462.4 2590.81   563.8 2591.12   580.8 2590.35   613.9 2585.98
   623.4 2584.22   645.9 2583.68   658.2 2583.85     664  2585.5   670.8 2588.97
     685 2601.81   713.3 2632.82   735.6 2654.26   760.7 2674.22   812.8 2710.57
   832.1 2722.66   850.7 2731.86   861.1 2734.97   877.5 2738.19   905.5 2740.93
#Mann= 6 ,-1,0
       0      .1       0     450     .12       0     560     .08       0
   613.9     .04       0     664     .08       0     680      .1       0
Bank Sta=613.9,664
XS Rating Curve= 0 ,0
Exp/Cntr(USF)=0,0
Exp/Cntr=0.3,0.1

Type RM Length L Ch R = 1 ,48488   ,437.3,433.2,428.5
XS GIS Cut Line= 2
2299312.51251038524662.7141163782298453.44676636525173.597911117
#Sta/Elev= 30
       0 2604.46      19 2602.34    74.9 2598.96    92.5 2599.89   112.9 2596.87
   149.3 2593.91   228.4 2591.19   419.2 2588.31   489.1  2589.3     517    2586
   582.8 2588.01   596.1 2586.57   599.6 2584.99   605.4 2582.95   630.9 2582.83
   652.8 2583.47  658.05 2585.08   670.6 2592.08   689.2  2609.3   702.4 2616.65
   721.7 2624.04     759 2633.33   809.1 2660.82     825 2668.44     850 2679.36
     880 2690.75   907.9 2699.21   921.3 2702.15   945.1 2705.66   999.5 2710.11
#Mann= 4 ,-1,0
       0     .08       0   599.6     .04       0  658.05     .08       0
     690      .1       0
Bank Sta=599.6,658.05
XS Rating Curve= 0 ,0
Exp/Cntr(USF)=0,0
Exp/Cntr=0.3,0.1

Type RM Length L Ch R = 1 ,48055   ,1030,1037.9,1028.6
XS GIS Cut Line= 2
2299006.63304092 524265.721613462298307.01510544524805.891740381
#Sta/Elev= 30
       0  2606.9    69.8 2605.15   124.4 2602.24   144.6 2598.22   169.6 2587.15
   178.2 2585.92   215.4 2587.07   230.5 2585.14   250.7 2584.56   332.2 2586.39
     372 2584.28   404.9 2586.45   424.6 2584.72   523.6 2587.72   528.7 2586.08
   531.8 2583.69   537.5 2582.27   557.5 2582.35   574.2 2583.62   611.6 2585.09
     623 2584.47   634.8 2582.21   644.9 2582.66   651.6 2585.22   665.8 2587.54
   699.5 2588.59   730.8 2598.58   801.6 2613.89     842 2627.67   883.9 2644.69
#Mann= 5 ,-1,0
       0     .08       0   531.8     .04       0   574.2     .07       0
     580     .08       0     800      .1       0
Bank Sta=531.8,574.2
XS Rating Curve= 0 ,0
Exp/Cntr(USF)=0,0
Exp/Cntr=0.3,0.1

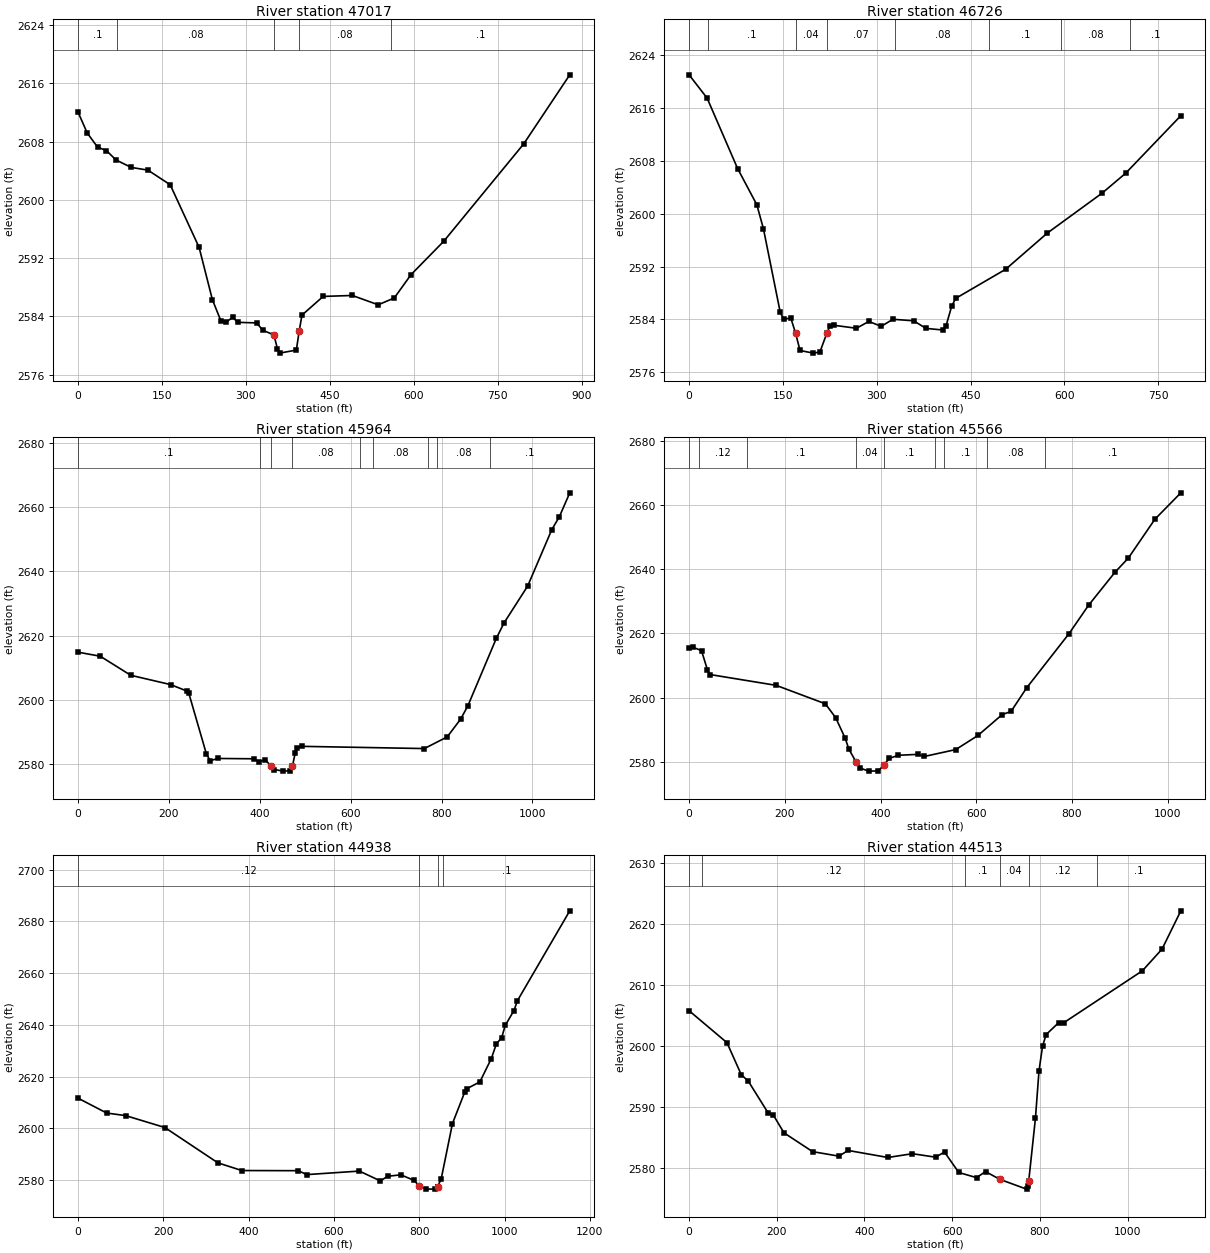
Type RM Length L Ch R = 1 ,47017   ,294.1,291.7,286.6
XS GIS Cut Line= 2
2298720.27779291523774.3620401762298017.40582053524301.516019461
#Sta/Elev= 30
       0 2612.08    16.4 2609.21    35.1 2607.24    50.7 2606.79    67.8  2605.5
    95.1 2604.47   124.9  2604.1   164.7 2602.09   216.4 2593.48   240.1  2586.3
   255.1 2583.43   264.7 2583.21   276.4 2583.88   285.1 2583.19   319.2 2583.11
   330.1 2582.11   350.1 2581.45   356.4 2579.52   360.1 2578.96   390.1 2579.38
   395.1 2581.95   400.1 2584.18     438 2586.75   490.1 2586.88   536.4  2585.6
   565.1 2586.54   595.1 2589.75   653.5 2594.33   796.4 2607.71   878.6 2617.19
#Mann= 5 ,-1,0
       0      .1       0      70     .08       0   350.1     .04       0
   395.1     .08       0     560      .1       0
Bank Sta=350.1,395.1
XS Rating Curve= 0 ,0
Exp/Cntr(USF)=0,0
Exp/Cntr=0.3,0.1

Type RM Length L Ch R = 1 ,46726   ,769.5,761.4,750.2
XS GIS Cut Line= 3
 2298433.9225449523621.4223054452298030.42196817523972.858291635
2297958.83315616524213.657022913
#Sta/Elev= 30
       0 2620.99    28.8 2617.48    77.6 2606.82   108.4 2601.33     119 2597.67
   145.8 2585.06   151.3 2584.05   162.7  2584.2   170.2 2581.96   177.4  2579.3
   198.6  2578.9   209.2 2579.07   220.32581.905   225.1 2582.95   231.1 2583.12
   267.6 2582.66   287.4 2583.69   307.3 2582.95   325.9 2584.02     359 2583.79
   378.9 2582.64   405.5  2582.4   410.8    2583   419.9    2586   426.3 2587.18
   506.2 2591.58     573 2597.07   660.6 2603.11     698  2606.1   786.3 2614.81
#Mann= 8 ,-1,0
       0     .08       0      30      .1       0   170.2     .04       0
   220.3     .07       0     330     .08       0     480      .1       0
  595.09     .08       0  705.09      .1       0
Bank Sta=170.2,220.3
XS Rating Curve= 0 ,0
Exp/Cntr(USF)=0,0
Exp/Cntr=0.3,0.1

Type RM Length L Ch R = 1 ,45964   ,400.9,398.5,388
XS GIS Cut Line= 3
2298053.20022653522921.8043699752297555.33257943523595.390010172
2297369.85247561523754.837818721
#Sta/Elev= 30
       0 2614.85      49 2613.59   116.1 2607.66   203.6 2604.77   240.5 2602.71
     244 2602.01   282.7  2583.1   291.1 2581.08   307.6 2581.78   387.2 2581.68
   397.8 2580.79   412.1 2581.35   425.7  2579.3   432.2 2578.34   451.9 2577.84
   466.5 2577.97   471.8 2579.31   477.9 2583.45   481.7 2585.12     493 2585.55
   762.2 2584.86   812.5 2588.49   841.8 2593.98   857.6 2598.04   920.5 2619.13
   937.6 2623.96   989.5 2635.41  1042.5 2652.93  1059.5 2657.05  1082.2 2664.43
#Mann= 9 ,-1,0
       0      .1       0     400     .08       0   425.7     .04       0
   471.8     .08       0     620      .1       0     650     .08       0
     770      .1       0     790     .08       0  907.61      .1       0
Bank Sta=425.7,471.8
XS Rating Curve= 0 ,0
Exp/Cntr(USF)=0,0
Exp/Cntr=0.3,0.1

Type RM Length L Ch R = 1 ,45566   ,590.9,628,656.6
XS GIS Cut Line= 3
2297897.00645489522882.7559270652297597.63505925522973.868960521
2297239.69099924523592.135973263
#Sta/Elev= 30
       0 2615.28     9.2 2615.59      26  2614.6    38.5 2608.55    44.3 2607.14
   182.1 2603.78   284.7 2598.04   306.1 2593.75     326 2587.37     334 2583.85
  348.52 2580.04   357.4 2578.04     375 2577.07   395.7 2577.14   407.52579.133
   418.4 2581.03   436.9 2582.01   477.4 2582.28   491.5 2581.64   557.1 2583.78
   603.4 2588.17   654.2 2594.69   672.6 2595.65     705 2602.96   793.6 2619.86
   834.5 2628.72   889.9 2639.04   917.6 2643.42   973.1 2655.52  1027.3 2663.75
#Mann= 9 ,-1,0
       0      .1       0      20     .12       0     120      .1       0
  348.52     .04       0   407.5      .1       0  512.93     .08       0
  532.93      .1       0  622.93     .08       0  742.93      .1       0
Bank Sta=348.52,407.5
XS Rating Curve= 0 ,0
Exp/Cntr(USF)=0,0
Exp/Cntr=0.3,0.1

Type RM Length L Ch R = 1 ,44938   ,402.8,424.4,441.3
XS GIS Cut Line= 3
2297879.37037831522713.0639282452297334.33928267522676.626749522
2296745.07738905522820.929225791
#Sta/Elev= 30
       0 2611.66    67.3 2605.89   111.4 2604.92   203.6  2600.3   327.9 2586.64
   384.1 2583.66   516.3  2583.6   536.4 2582.09   659.7 2583.45   709.1 2579.63
   725.6 2581.44   756.9    2582   787.3 2579.89   799.9 2577.79   816.2 2576.47
   836.3  2576.5   842.9 2577.46   842.9 2577.47   851.3 2580.27   877.9 2601.85
   906.8 2614.05   912.4 2615.37   942.2 2617.97     969 2626.96   980.9 2632.67
   993.2 2635.04  1001.7 2639.82  1022.1 2645.55  1030.3 2649.38  1152.9 2684.11
#Mann= 4 ,-1,0
       0     .12       0   799.9     .04       0   842.9     .12       0
  856.25      .1       0
Bank Sta=799.9,842.9
XS Rating Curve= 0 ,0
Exp/Cntr(USF)=0,0
Exp/Cntr=0.3,0.1

Type RM Length L Ch R = 1 ,44513   ,327.2,323.4,318.2
XS GIS Cut Line= 2
2297809.14745834522459.7311288732296706.02894614522257.980840505
#Sta/Elev= 30
       0 2605.73    86.4 2600.49   118.9 2595.26   135.2 2594.16   179.9 2589.01
   192.1 2588.62   216.5  2585.7   281.6 2582.62   341.4 2581.88   362.9 2582.81
   453.4 2581.66   509.3 2582.28   562.1 2581.71   582.5 2582.55     615  2579.2
   655.7 2578.35     676 2579.35   708.5 2578.08   769.5 2576.47   773.6 2577.03
  774.64 2577.85   789.9 2588.13     798 2595.88   806.1 2599.93   814.3 2601.82
   842.7 2603.76   854.9 2603.78  1033.8 2612.28  1078.6 2615.84  1121.4 2622.11
#Mann= 6 ,-1,0
       0      .1       0      30     .12       0     630      .1       0
   708.5     .04       0  774.64     .12       0     930      .1       0
Bank Sta=708.5,774.64
XS Rating Curve= 0 ,0
Exp/Cntr(USF)=0,0
Exp/Cntr=0.3,0.1

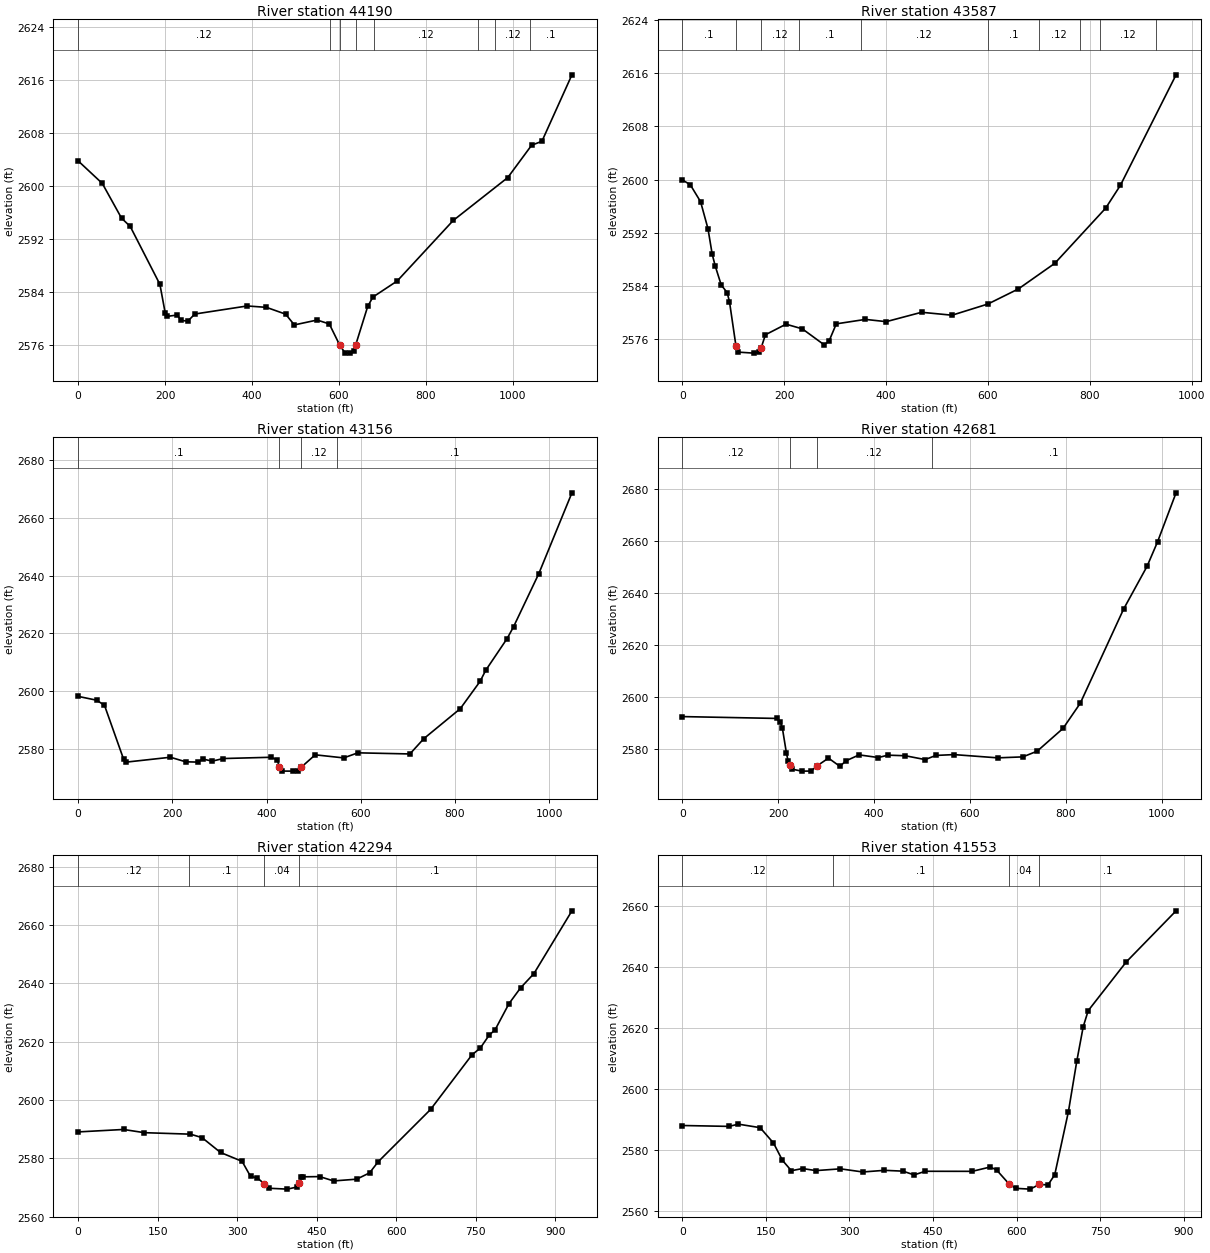
Type RM Length L Ch R = 1 ,44190   ,643.1,603.2,545.3
XS GIS Cut Line= 4
2297763.57800797 522064.11343822 2297067.1365075522003.687416512
2296791.71483847522209.4098190082296699.52087232522218.932397595
#Sta/Elev= 30
       0 2603.81    55.6 2600.39    99.8 2595.14   119.9 2593.87   188.1 2585.11
   200.2  2580.8   204.2 2580.26   228.3 2580.47   236.3 2579.66   252.3 2579.54
   268.4 2580.62   388.9 2581.84     433 2581.63   477.2  2580.6   497.2 2578.97
   549.5 2579.71   577.6 2579.12   601.7 2575.89   613.7 2574.75   625.7  2574.7
   633.8 2575.05     638 2575.88   665.9 2581.77   677.9 2583.19   733.7 2585.62
   862.5 2594.78     988 2601.28  1042.8 2606.17  1066.5 2606.77  1135.5 2616.83
#Mann= 8 ,-1,0
       0     .12       0     580      .1       0   601.7     .04       0
     638      .1       0     680     .12       0  919.06      .1       0
  959.06     .12       0 1039.06      .1       0
Bank Sta=601.7,638
XS Rating Curve= 0 ,0
Exp/Cntr(USF)=0,0
Exp/Cntr=0.3,0.1

Type RM Length L Ch R = 1 ,43587   ,423.8,430.3,418.9
XS GIS Cut Line= 2
2297220.16677778521379.390875031 2296693.0127985522192.900102322
#Sta/Elev= 30
       0 2599.95    15.7 2599.23      36 2596.67    50.5 2592.62    58.8 2588.78
    64.9 2586.97    76.5 2584.16    88.1 2583.01    92.7 2581.66   105.4 2575.01
   110.3 2574.06   140.1 2573.91   149.9 2574.02   154.92574.706   163.3 2576.67
   203.7 2578.26   235.7 2577.56   278.6 2575.16   288.1 2575.71   302.4 2578.31
   359.6 2578.98   400.4 2578.64   469.8 2580.05   529.6 2579.61     600 2581.29
   659.9 2583.56   731.4 2587.41   831.2  2595.7   860.1 2599.13   969.4 2615.74
#Mann= 10 ,-1,0
       0      .1       0   105.4     .04       0   154.9     .12       0
     230      .1       0     350     .12       0     600      .1       0
     700     .12       0     780      .1       0     820     .12       0
     930      .1       0
Bank Sta=105.4,154.9
XS Rating Curve= 0 ,0
Exp/Cntr(USF)=0,0
Exp/Cntr=0.3,0.1

Type RM Length L Ch R = 1 ,43156   ,501.6,475.4,436.8
XS GIS Cut Line= 3
2296991.98830277 521183.808712782296633.36271587521855.401155071
2296442.46364178522069.802258127
#Sta/Elev= 30
       0 2598.11    39.3 2596.78      56 2595.01    96.8 2576.21   101.3 2575.28
     196 2576.99   228.3 2575.41   254.4  2575.3   264.6 2576.38   284.7 2575.64
   308.3 2576.54   409.7 2576.98   423.3 2576.02   426.5 2573.74   432.3 2572.19
   456.1 2572.17   467.9 2572.35   473.8 2573.54   503.4 2577.83   563.8 2576.76
     594 2578.52   704.4 2578.13     734 2583.44   811.3 2593.83   853.4 2603.31
   865.4 2607.16   910.8 2618.17   924.4 2622.24     978 2640.67  1048.4 2668.74
#Mann= 4 ,-1,0
       0      .1       0   426.5     .04       0   473.8     .12       0
     550      .1       0
Bank Sta=426.5,473.8
XS Rating Curve= 0 ,0
Exp/Cntr(USF)=0,0
Exp/Cntr=0.3,0.1

Type RM Length L Ch R = 1 ,42681   ,364.9,387,409.4
XS GIS Cut Line= 3
2296595.94839127521056.1960470292296605.54572264 521506.37707914
2296351.18805657522027.669723747
#Sta/Elev= 30
       0 2592.46     197 2591.75     205 2590.23     209 2587.94   217.4 2578.41
     221 2575.25   224.5 2573.77     229 2572.28     249 2571.51     269 2571.53
     281 2573.49   305.1 2576.51   329.1 2573.32   341.1 2575.43   369.1 2577.75
   409.1 2576.73   429.1 2577.64   465.4 2577.42   506.8 2575.94   529.1 2577.54
   567.1 2577.86   658.1 2576.61   710.6 2576.98   740.6 2579.18   794.4 2587.91
   830.3 2597.54   920.7  2633.7   969.7 2650.15   991.6 2659.54  1030.3 2678.41
#Mann= 4 ,-1,0
       0     .12       0   224.5     .04       0     281     .12       0
  520.28      .1       0
Bank Sta=224.5,281
XS Rating Curve= 0 ,0
Exp/Cntr(USF)=0,0
Exp/Cntr=0.3,0.1

Type RM Length L Ch R = 1 ,42294   ,681.8,741,788.6
XS GIS Cut Line= 2
2296367.60910758520982.3983721132295999.90293685521838.210079223
#Sta/Elev= 30
       0  2589.1    85.7 2589.94   124.9 2588.84     212 2588.33   233.8 2587.14
   268.6 2582.06   309.3 2579.02   325.2 2573.88   338.3 2573.31   351.3  2571.3
     360  2569.8   394.8  2569.5   412.3  2570.2   415.8 2571.56     421 2573.58
   424.1 2573.72   455.8 2573.79   481.9 2572.31   525.5 2572.91   549.8 2575.07
     566 2578.87   664.8 2596.79   743.1 2615.54   758.5 2617.79   775.2  2622.2
   786.7 2624.14   812.8 2633.06   834.6 2638.45   859.8 2643.34   931.5 2664.85
#Mann= 4 ,-1,0
       0     .12       0     210      .1       0   351.3     .04       0
   415.8      .1       0
Bank Sta=351.3,415.8
XS Rating Curve= 0 ,0
Exp/Cntr(USF)=0,0
Exp/Cntr=0.3,0.1

Type RM Length L Ch R = 1 ,41553   ,253,254.5,255.4
XS GIS Cut Line= 2
2296279.75011104520842.4747850192295394.65207174520891.285338656
#Sta/Elev= 30
       0 2587.97    83.7 2587.68   100.9 2588.41   139.8 2587.26   163.8 2582.23
   179.8 2576.57   195.9 2573.15   215.9 2573.87   239.9 2573.19     284 2573.77
   324.1 2572.74   362.9 2573.28   396.2 2573.01   416.2 2571.78   436.2 2572.97
   520.4 2572.95   552.7 2574.36   564.1 2573.43   586.9 2568.76   598.2 2567.38
   624.5 2567.12   640.82568.638   656.6 2568.52   668.6 2571.83   693.2 2592.54
   708.3 2609.15   719.7 2620.31   728.7 2625.61   796.8 2641.53   886.4 2658.32
#Mann= 4 ,-1,0
       0     .12       0     270      .1       0   586.9     .04       0
   640.8      .1       0
Bank Sta=586.9,640.8
XS Rating Curve= 0 ,0
Exp/Cntr(USF)=0,0
Exp/Cntr=0.3,0.1

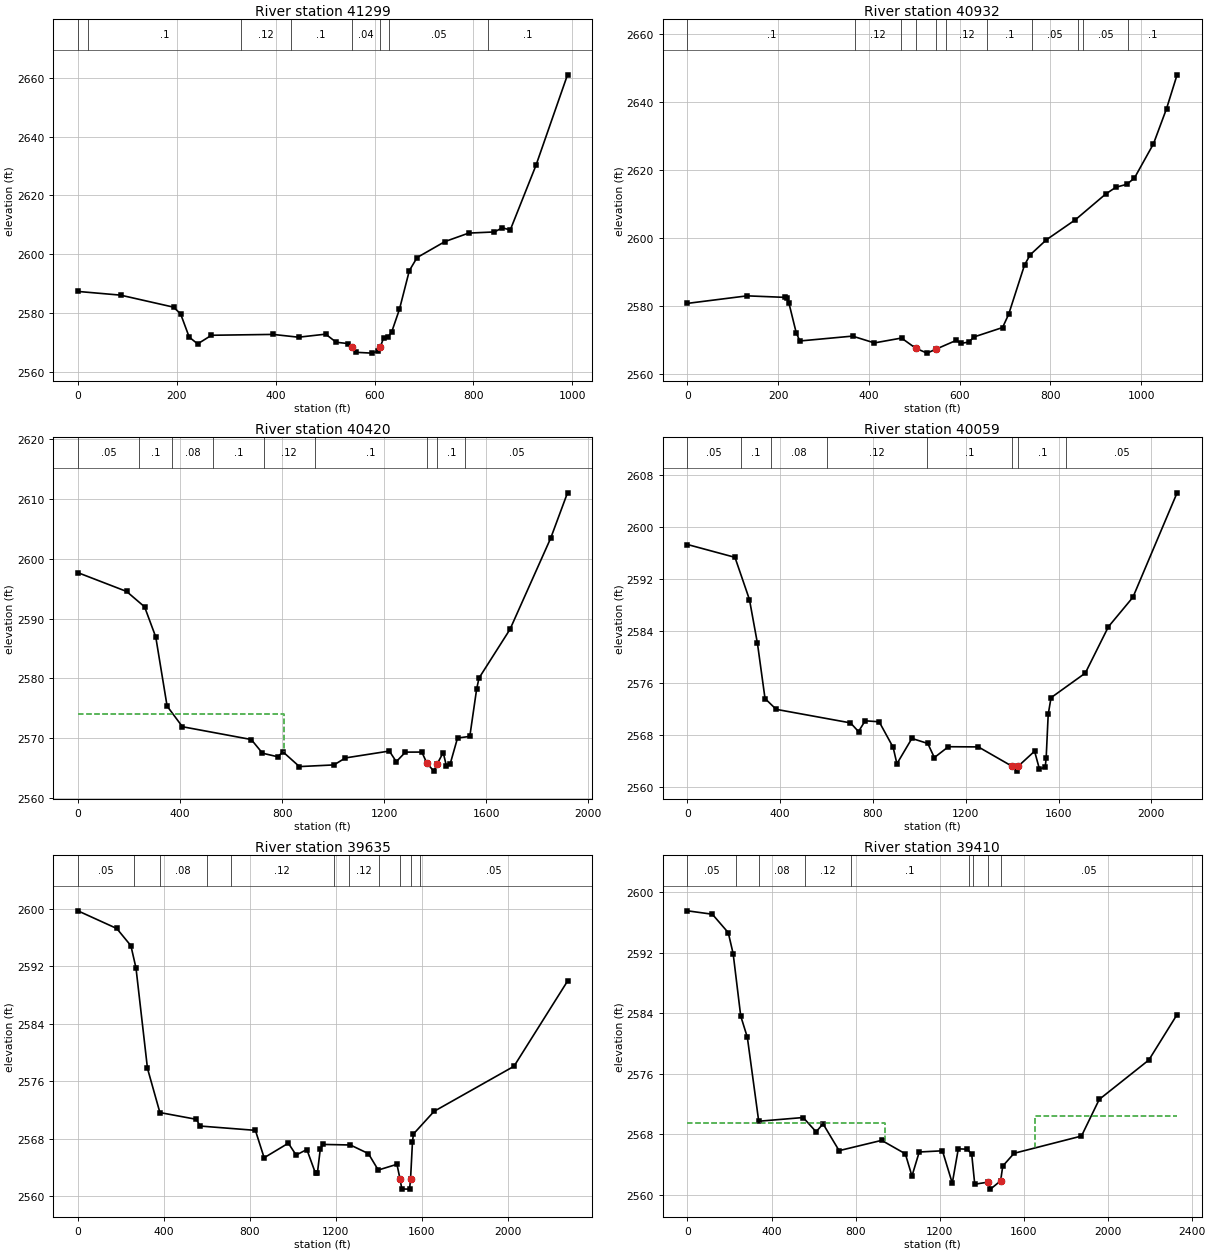
Type RM Length L Ch R = 1 ,41299   ,365.7,366.1,365.6
XS GIS Cut Line= 3
2296223.86157669 520519.935852362296002.29869438520612.456616404
2295252.39355423 520634.36942894
#Sta/Elev= 30
       0 2587.29    86.3 2586.03   193.4 2581.94   207.7 2579.67   225.1 2571.75
   242.2 2569.43   270.2 2572.37   394.5 2572.66   446.3 2571.71   501.2 2572.75
   522.3    2570   546.4 2569.54   553.9 2568.27   562.4 2566.57   594.4 2566.29
   606.4 2566.92   611.4 2568.26   618.4 2571.52   626.4 2571.65   634.4 2573.35
   650.4 2581.22   670.4 2594.38   686.1 2598.83   742.4 2604.26   790.5 2607.15
   842.5 2607.54   858.5 2608.96   874.5  2608.2   926.5  2630.2   990.3 2661.02
#Mann= 8 ,-1,0
       0     .12       0      20      .1       0   330.1     .12       0
   430.1      .1       0   553.9     .04       0   611.4      .1       0
   630.1     .05       0   830.1      .1       0
Bank Sta=553.9,611.4
XS Rating Curve= 0 ,0
Exp/Cntr(USF)=0,0
Exp/Cntr=0.3,0.1

Type RM Length L Ch R = 1 ,40932   ,512.4,512.8,513.2
XS GIS Cut Line= 3
2296179.64495576520239.7869825152295388.91398684520265.819277788
2295114.50426839520352.871453455
#Sta/Elev= 30
       0 2580.74   131.5 2582.95   215.6  2582.5   219.6 2582.21   223.6 2580.81
   239.6 2572.15   247.6 2569.69   363.7 2571.12   411.9 2569.12   471.7 2570.55
   502.9 2567.57   527.8 2566.12   547.8 2567.29   591.8 2569.84   603.8    2569
   619.8 2569.37   631.8 2570.89   694.4 2573.64   707.9 2577.55   742.9 2592.05
   755.3 2595.01   791.2 2599.44     855 2605.32     922  2612.9   944.2 2614.86
   968.2 2615.72     985 2617.56    1027 2627.63  1055.7 2637.92    1079 2647.89
#Mann= 11 ,-1,0
       0      .1       0     370     .12       0     470      .1       0
   502.9     .04       0   547.8      .1       0     570     .12       0
     660      .1       0     760     .05       0  861.16      .1       0
  871.16     .05       0  971.16      .1       0
Bank Sta=502.9,547.8
XS Rating Curve= 0 ,0
Exp/Cntr(USF)=0,0
Exp/Cntr=0.3,0.1

Type RM Length L Ch R = 1 ,40420   ,361.7,361,361.3
XS GIS Cut Line= 4
2296873.05544659  520070.66677922296572.76979283519724.094884653
2295439.39641691519750.911457225  2295149.787132519900.597155047
#Sta/Elev= 30
       0 2597.67   190.7 2594.53   261.3 2591.95   305.1  2586.9   349.5 2575.34
   409.5 2571.89   679.2 2569.75   723.2 2567.46   783.3 2566.86   803.3 2567.69
   867.9 2565.22  1003.3  2565.5  1048.2 2566.67  1220.3 2567.82  1247.4 2566.04
  1283.4 2567.64  1347.5 2567.65 1367.43 2565.79  1394.4 2564.46  1407.4 2565.65
  1431.4 2567.56  1443.4 2565.39    1458 2565.57  1487.4    2570  1535.5 2570.27
  1562.4 2578.22  1571.5 2580.03    1693 2588.19  1852.5 2603.45  1918.3 2611.03
#Mann= 9 ,-1,0
       0     .05       0     240      .1       0     370     .08       0
  528.57      .1       0  728.57     .12       0  928.57      .1       0
 1367.43     .04       0  1407.4      .1       0 1518.57     .05       0
#XS Ineff= 2 , 0
          805.56 2573.94
Permanent Ineff=
       F       F
Bank Sta=1367.43,1407.4
XS Rating Curve= 0 ,0
Exp/Cntr(USF)=0,0
Exp/Cntr=0.3,0.1

Type RM Length L Ch R = 1 ,40059   ,313,423.4,425
XS GIS Cut Line= 5
2296998.84207899519920.7982746392296320.01100765519470.645044307
2295743.81487282519395.0193016112295675.39158181519395.019301611
2295055.98073688519582.283045429
#Sta/Elev= 30
       0 2597.29   204.8 2595.32   267.2 2588.84   301.8 2582.09   334.4 2573.63
   382.6 2571.97   702.9 2569.89   737.5 2568.56   766.3 2570.21   826.6 2570.06
   886.9 2566.13   903.1 2563.61   967.7  2567.5  1036.2 2566.73  1064.5 2564.56
    1125 2566.23  1254.3  2566.2 1398.57 2563.25  1419.3 2562.48  1427.3 2563.27
  1496.7 2565.54  1517.6 2562.81  1542.7 2563.08  1546.8 2564.57  1555.5 2571.19
  1567.7 2573.76  1715.5 2577.54  1814.9 2584.65  1920.8 2589.19  2111.2 2605.23
#Mann= 8 ,-1,0
       0     .05       0     230      .1       0     360     .08       0
     600     .12       0 1034.52      .1       0 1398.57     .04       0
  1427.3      .1       0 1634.09     .05       0
Bank Sta=1398.57,1427.3
XS Rating Curve= 0 ,0
Exp/Cntr(USF)=0,0
Exp/Cntr=0.3,0.1

Type RM Length L Ch R = 1 ,39635   ,223.3,225.1,177.9
XS GIS Cut Line= 3
2297128.48620933519753.341272956 2295742.0142599519031.295491502
2295088.39176946519319.393558915
#Sta/Elev= 30
       0 2599.75   180.7 2597.29   246.5 2594.89   270.2 2591.79   323.6  2577.8
   381.4 2571.64   550.6  2570.7   568.6 2569.76   825.7 2569.16   866.3 2565.34
   978.9 2567.37  1015.1 2565.72    1065 2566.49  1105.3 2563.17  1114.3 2563.26
  1127.8 2566.62  1141.4  2567.2  1267.6 2567.12  1351.3 2565.92  1397.1 2563.63
  1484.1 2564.43  1498.5 2562.37  1506.8 2560.99  1542.7 2560.97  1547.3 2562.32
  1556.3 2567.55  1560.8 2568.65  1656.9 2571.81  2028.6 2578.09  2277.5 2589.95
#Mann= 11 ,-1,0
       0     .05       0     260      .1       0     380     .08       0
     600      .1       0     710     .12       0    1190      .1       0
    1260     .12       0    1400      .1       0  1498.5     .04       0
  1547.3      .1       0 1593.22     .05       0
Bank Sta=1498.5,1547.3
XS Rating Curve= 0 ,0
Exp/Cntr(USF)=0,0
Exp/Cntr=0.3,0.1

Type RM Length L Ch R = 1 ,39410   ,467.1,618.9,172.3
XS GIS Cut Line= 3
2297197.38851942519534.3519475352295830.24429305518827.826231392
2295119.59300263519176.196922865
#Sta/Elev= 30
       0 2597.57   118.4 2597.12   194.2 2594.68   217.5 2591.89   253.5 2583.65
     285 2580.84   339.1 2569.74   550.7 2570.23   612.4 2568.34   645.2  2569.4
   721.8 2565.85   924.4 2567.21    1037 2565.43  1068.5 2562.49  1103.1 2565.67
  1213.6 2565.83  1260.4 2561.55  1289.1 2566.09  1331.7 2566.04    1353 2565.36
  1367.3 2561.41  1428.12561.674  1442.2 2560.76  1490.52561.859  1500.7 2563.81
  1554.6  2565.5  1875.3 2567.78    1960 2572.63  2196.1 2577.84  2330.4 2583.85
#Mann= 9 ,-1,0
       0     .05       0     230      .1       0     340     .08       0
     560     .12       0     780      .1       0    1340     .12       0
    1360      .1       0  1428.1     .04       0  1490.5     .05       0
#XS Ineff= 2 , 0
          942.31 2569.47 1653.85         2570.44
Permanent Ineff=
       F       F
Bank Sta=1428.1,1490.5
XS Rating Curve= 0 ,0
Exp/Cntr(USF)=0,0
Exp/Cntr=0.3,0.1

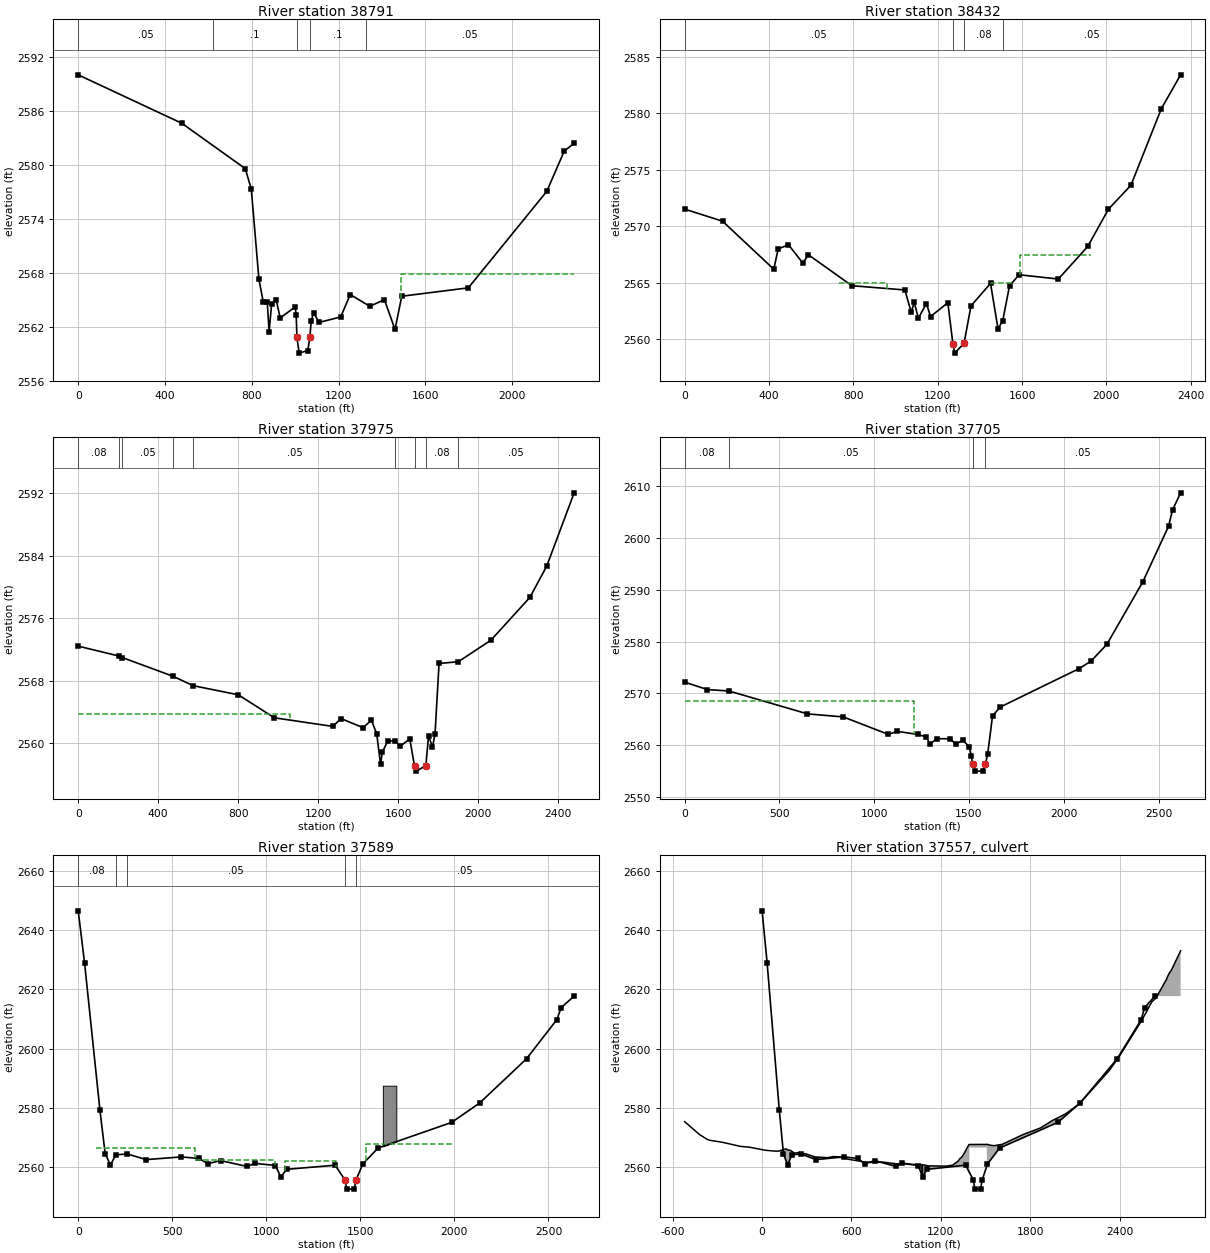
Type RM Length L Ch R = 1 ,38791   ,368.9,359.6,56
XS GIS Cut Line= 5
2297114.08130596518782.810908359 2296408.2410408518442.495066227
2296102.13684417518615.3539066752295932.87922956518629.758810046
2295000.16173632518930.461167908
#Sta/Elev= 30
       0    2590   477.3 2584.62   769.7 2579.58   797.4 2577.32   832.6 2567.28
   852.6 2564.77   870.8 2564.79   879.6 2561.48   891.3 2564.59   911.9 2565.03
   930.7    2563   999.6 2564.22  1004.2 2563.36 1007.81 2560.83    1018 2559.09
  1057.5 2559.38  1067.5 2560.85  1073.3 2562.68  1085.1 2563.57  1109.8  2562.5
  1209.4 2563.11  1253.3  2565.6  1343.6 2564.29  1410.8 2565.03  1459.5 2561.72
  1490.7 2565.41  1797.5 2566.34  2158.9 2577.06  2239.5 2581.54    2285 2582.39
#Mann= 5 ,-1,0
       0     .05       0     620      .1       0 1007.81     .04       0
  1067.5      .1       0 1325.01     .05       0
#XS Ineff= 2 , 0
                         1487.97          2567.9
Permanent Ineff=
       F       F
Bank Sta=1007.81,1067.5
XS Rating Curve= 0 ,0
Exp/Cntr(USF)=0,0
Exp/Cntr=0.3,0.1

Type RM Length L Ch R = 1 ,38432   ,341.9,457,440.5
Node Name=D
XS GIS Cut Line= 4
2297001.05130937517988.5969084442296064.73259027518150.652071365
2295736.62090238518634.8168791062294960.35666518518888.903369119
#Sta/Elev= 30
       0 2571.51   179.5 2570.44   422.5 2566.18   443.4 2567.98   492.1 2568.35
   561.1 2566.71   585.5 2567.48   792.5 2564.72  1044.6 2564.34  1074.1 2562.36
  1088.6 2563.25    1108 2561.84  1146.6 2563.14  1165.9 2561.98    1248 2563.21
  1272.1 2559.54  1280.8 2558.74 1325.06 2559.62  1357.7 2562.93  1450.3 2564.92
    1486  2560.9  1508.3 2561.61  1540.5 2564.71  1586.1 2565.69    1772 2565.31
  1911.5  2568.2  2009.8 2571.51  2116.4 2573.63  2260.3 2580.41  2351.9 2583.42
#Mann= 4 ,-1,0
       0     .05       0  1272.1     .04       0 1325.06     .08       0
  1508.3     .05       0
#XS Ineff= 3 ,-1
  732.21  958.41 2564.93  1450.6 1556.68    2565 1587.88 1925.62  2567.4
Permanent Ineff=
       F       F       F
Bank Sta=1272.1,1325.06
XS Rating Curve= 0 ,0
Exp/Cntr(USF)=0,0
Exp/Cntr=0.3,0.1

Type RM Length L Ch R = 1 ,37975   ,179.2,269.4,268
XS GIS Cut Line= 4
2297063.63562867517821.0906960642295960.89433347517947.328991937
2295310.98393211518355.4988357112294737.94561336518544.696542316
#Sta/Elev= 30
       0 2572.43   203.9 2571.17     220 2570.98   474.5 2568.58   575.2 2567.38
   800.7 2566.22   981.4 2563.28  1274.3 2562.18  1313.9 2563.19  1425.1 2562.02
  1466.9 2562.98  1493.4 2561.21  1512.2 2557.38  1521.7 2558.93  1549.9 2560.37
  1587.2 2560.26  1610.8 2559.65  1658.7 2560.59  1682.3 2557.12  1691.8 2556.47
    1739 2557.18  1752.7    2561  1772.1 2559.52  1784.9 2561.21  1805.1 2570.22
  1901.4 2570.44  2064.6 2573.19  2259.5 2578.66  2343.3 2582.63  2480.9 2592.01
#Mann= 9 ,-1,0
       0     .08       0   203.9    .016       0     220     .05       0
   474.5     .04       0   575.2     .05       0  1587.2     .08       0
  1682.3     .04       0    1739     .08       0  1901.4     .05       0
#XS Ineff= 2 , 0
            1061 2563.72
Permanent Ineff=
       F       F
Bank Sta=1682.3,1739
XS Rating Curve= 0 ,0
Exp/Cntr(USF)=0,0
Exp/Cntr=0.3,0.1

Type RM Length L Ch R = 1 ,37705   ,127.3,116.7,111.9
BEGIN DESCRIPTION:
xs 4
END DESCRIPTION:
XS GIS Cut Line= 4
2297017.07640679517774.9340373372295797.56197413517892.382136314
2295399.82998777518042.0238737542294556.45940565518514.035660549
#Sta/Elev= 30
       0 2572.18   120.2 2570.75     234 2570.47     648 2566.06   836.8 2565.47
  1073.8 2562.11  1122.1 2562.68    1230 2562.09  1274.1 2561.61    1295 2560.21
  1328.9 2561.27  1397.5 2561.25  1431.8 2560.28  1469.1 2560.98  1500.2 2559.69
    1513 2558.01  1518.8 2556.38  1531.2 2555.01  1572.8 2555.01  1586.32556.304
  1598.5 2558.29  1624.1 2565.64  1663.9 2567.36  2081.3  2574.8  2144.8 2576.27
  2227.3 2579.47  2416.3 2591.48  2552.7 2602.24  2573.9 2605.41  2616.6 2608.72
#Mann= 4 ,-1,0
       0     .08       0     234     .05       0  1518.8     .04       0
  1586.3     .05       0
#XS Ineff= 2 , 0
         1210.96 2568.56
Permanent Ineff=
       F       F
Bank Sta=1518.8,1586.3
XS Rating Curve= 0 ,0
Exp/Cntr(USF)=0,0
Exp/Cntr=0.5,0.3

Type RM Length L Ch R = 1 ,37589   ,81.6,81.3,80
BEGIN DESCRIPTION:
xs 3 - Invert lowered vs. LIDAR based on approximate underclearance from Effective FIS
invert = 2552.6
bw = 38.6'
END DESCRIPTION:
XS GIS Cut Line= 4
2296309.36675848516742.0119620352295850.78087296517510.837296476
2295603.07610578517822.3262685642294410.71760573518441.310189344
#Sta/Elev= 30
       0 2646.48    33.6 2629.01   115.5 2579.19   143.4 2564.55   171.4 2560.71
   199.3 2564.15   259.9 2564.47     362 2562.56   548.6 2563.47   642.1 2562.94
   688.3 2561.19   758.2  2562.2   898.7 2560.24     938 2561.31    1048 2560.57
  1077.1  2556.7  1107.7 2559.28  1365.7 2560.66  1418.1 2555.71  1428.1  2552.6
  1466.7  2552.6  1476.7 2555.63  1512.8 2561.07  1594.1 2566.46  1985.7 2575.12
  2134.7 2581.68  2383.3 2596.57  2544.9  2609.8  2567.4 2613.84  2636.6 2617.71
#Mann= 5 ,-1,0
       0     .08       0   199.3    .016       0   259.9     .05       0
  1418.1     .04       0  1476.7     .05       0
#XS Ineff= 4 ,-1
   94.28     623 2566.34     623 1047.212562.348  1101.5 1370.252562.138
 1529.36    2000  2567.7
Permanent Ineff=
       F       F       F       F
#Block Obstruct= 1 ,-1
  1619.5  1691.2  2587.5
Bank Sta=1418.1,1476.7
XS Rating Curve= 0 ,0
Exp/Cntr(USF)=0,0
Minor Loss Coefficient=0
Exp/Cntr=0.5,0.3

Type RM Length L Ch R = 2 ,37557   ,,,
BEGIN DESCRIPTION:
State bridge, no access. Deck elevation based on LIDAR. Structure geometry assumed no piers, no obstructive railing. Effective profile suggests ~1.1' deck thickness and ~14 ft underclearance. Invert lowered to reflect Effective underclearance. LOB deck tapered ~150' into ground to better reflect ground tie-in. Multiple opening: assumed 5' diameter corrugated metal pipe on LOB.
END DESCRIPTION:
Bridge Culvert--1,0,-1,-1, 0
Deck Dist Width WeirC Skew NumUp NumDn MinLoCord MaxHiCord MaxSubmerge Is_Ogee
23.42717,15,2.6,0, 60, 60, , , 0.98, 0, 0,0,,
  -519.6-421.897-369.394-353.239-271.472-144.098 -83.142  22.223  91.341 111.714
  160.88 176.201 188.445 217.331 250.951 260.633 289.681 356.322 439.322 476.007
 511.342 578.333 705.022 813.073 904.654 962.5291006.2821069.1941117.5881235.246
1277.8371314.9521328.8111337.2531352.9971387.0481391.2541508.3641514.7481526.175
1559.0021612.635 1753.751868.8351947.8682034.3292114.1212137.7642332.8112400.782
2542.6342583.6932600.6482617.6032647.691  2663.82711.0842729.3522747.4992809.021
2575.3532571.0892569.4062569.0912568.4472567.0152566.7352565.7062565.408 2565.43
2566.1952565.7252565.707 2564.752564.9042564.6342564.5572563.4562563.2112563.579
2563.5232562.686  2561.62561.7022561.1252561.2492560.9422560.8742560.4492560.351
2560.6722562.0162562.995 2563.252564.3682567.5332567.6632567.6832567.7052567.441
2567.259 2567.732571.0632573.2552575.7262577.9122580.7932581.8312592.7692597.648
2609.075 2612.732614.4822615.8852617.1862618.8812623.0962625.1392626.5082632.992
                                                                                
                                                                                
                                                                                
                                                  2566.6  2566.6
                                                                                
                                                                                
    -580-482.297-429.794-413.639-331.872-204.498-143.542 -38.177  30.941  51.314
  100.48 115.801 128.045 156.931 190.551 200.233 229.281 295.922 378.922 415.607
 450.942 517.933 644.622 752.673 844.254 902.129 945.8821008.7941057.1881174.846
1217.4371254.5521268.4111276.8531292.5971326.6481330.8541447.9641454.3481465.775
1498.6021552.235 1693.351808.4351887.4681973.9292053.7212077.3642272.4112340.382
2482.2342523.2932540.2482557.2032587.291  2603.42650.6842668.9522687.0992748.621
2575.3532571.0892569.4062569.0912568.4472567.0152566.7352565.7062565.408 2565.43
2566.1952565.7252565.707 2564.752564.9042564.6342564.5572563.4562563.2112563.579
2563.5232562.686  2561.62561.7022561.1252561.2492560.9422560.8742560.4492560.351
2560.6722562.0162562.995 2563.252564.3682567.5332567.6632567.6832567.7052567.441
2567.259 2567.732571.0632573.2552575.7262577.9122580.7932581.8312592.7692597.648
2609.075 2612.732614.4822615.8852617.1862618.8812623.0962625.1392626.5082632.992
                                                                                
                                                                                
                                                                                
                                                  2566.6  2566.6
                                                                                
                                                                                
BR Coef=-1 ,-1 , 0 ,, 0 ,,,0.8,0,1.2,0,
WSPro=,,,, 1 ,,,, 0 ,,,, 0 ,,,,-1 ,-1 ,-1 , 0 , 0 , 0 , 0 , 0
Culvert=1,4,4,15,0.024,0.5,1,2,1,2556.7,1075,2556.7,1019.5,Culvert #1  , 0 ,24
    1075  1019.5
BC Culvert Barrel=1,Barrel #1,0
Culvert Bottom n=0.024
BR U #Sta/Elev= 30
       0 2646.48    33.6 2629.01   115.5 2579.19   143.4 2564.55   171.4 2560.71
   199.3 2564.15   259.9 2564.47     362 2562.56   548.6 2563.47   642.1 2562.94
   688.3 2561.19   758.2  2562.2   898.7 2560.24     938 2561.31    1048 2560.57
  1077.1  2556.7  1107.7 2559.28  1365.7 2560.66  1418.1 2555.71  1428.1  2552.6
  1466.7  2552.6  1476.7 2555.63  1512.8 2561.07  1594.1 2566.46  1985.7 2575.12
  2134.7 2581.68  2383.3 2596.57  2544.9  2609.8  2567.4 2613.84  2636.6 2617.71
BR U #Mann= 5
       0     .08   199.3    .016   259.9     .05  1418.1    .035  1476.7     .05
BR D #Sta/Elev= 30
       0 2646.26      29 2632.16    67.6 2609.98    82.3    2603   117.7 2580.63
   150.7 2563.06   165.3 2560.84     219 2563.84   394.9 2561.98   505.4 2563.32
   879.1 2559.41   974.5 2560.28  1003.9 2559.53  1018.2 2556.72  1045.2 2558.14
  1245.9 2560.44  1308.9 2559.86  1340.5 2558.03  1351.1 2555.91  1368.8  2552.6
  1405.2  2552.6  1426.1 2556.12  1444.1  2560.2  1497.3 2562.91  1538.8 2566.78
  1874.1 2573.39  2013.5 2577.79  2192.3 2587.05  2476.2 2605.68  2607.6 2617.72
BR D #Mann= 3
       0     .05  1351.1    .035  1426.1     .05
BC Design=,, 0 ,, 0 ,,,,,,
BC Use User HTab Curves=0
BC User HTab FreeFlow(D)= 0