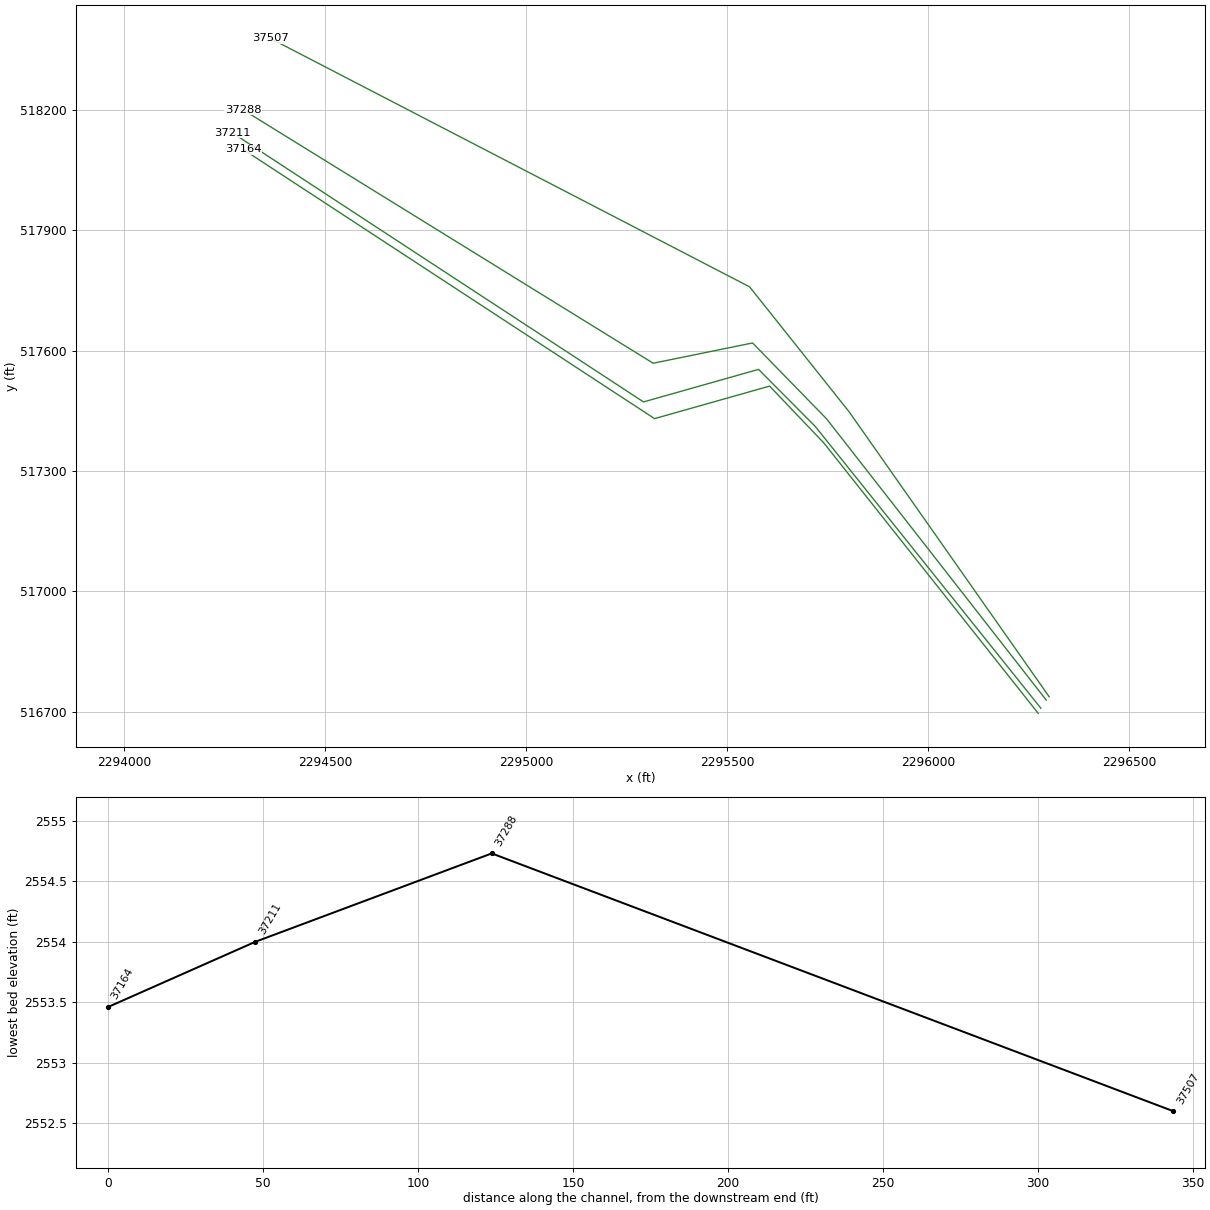
HEC-RAS study DEERCK.prj: DEERCK

--- DEERCK.g01 (geometry) --- (continued)

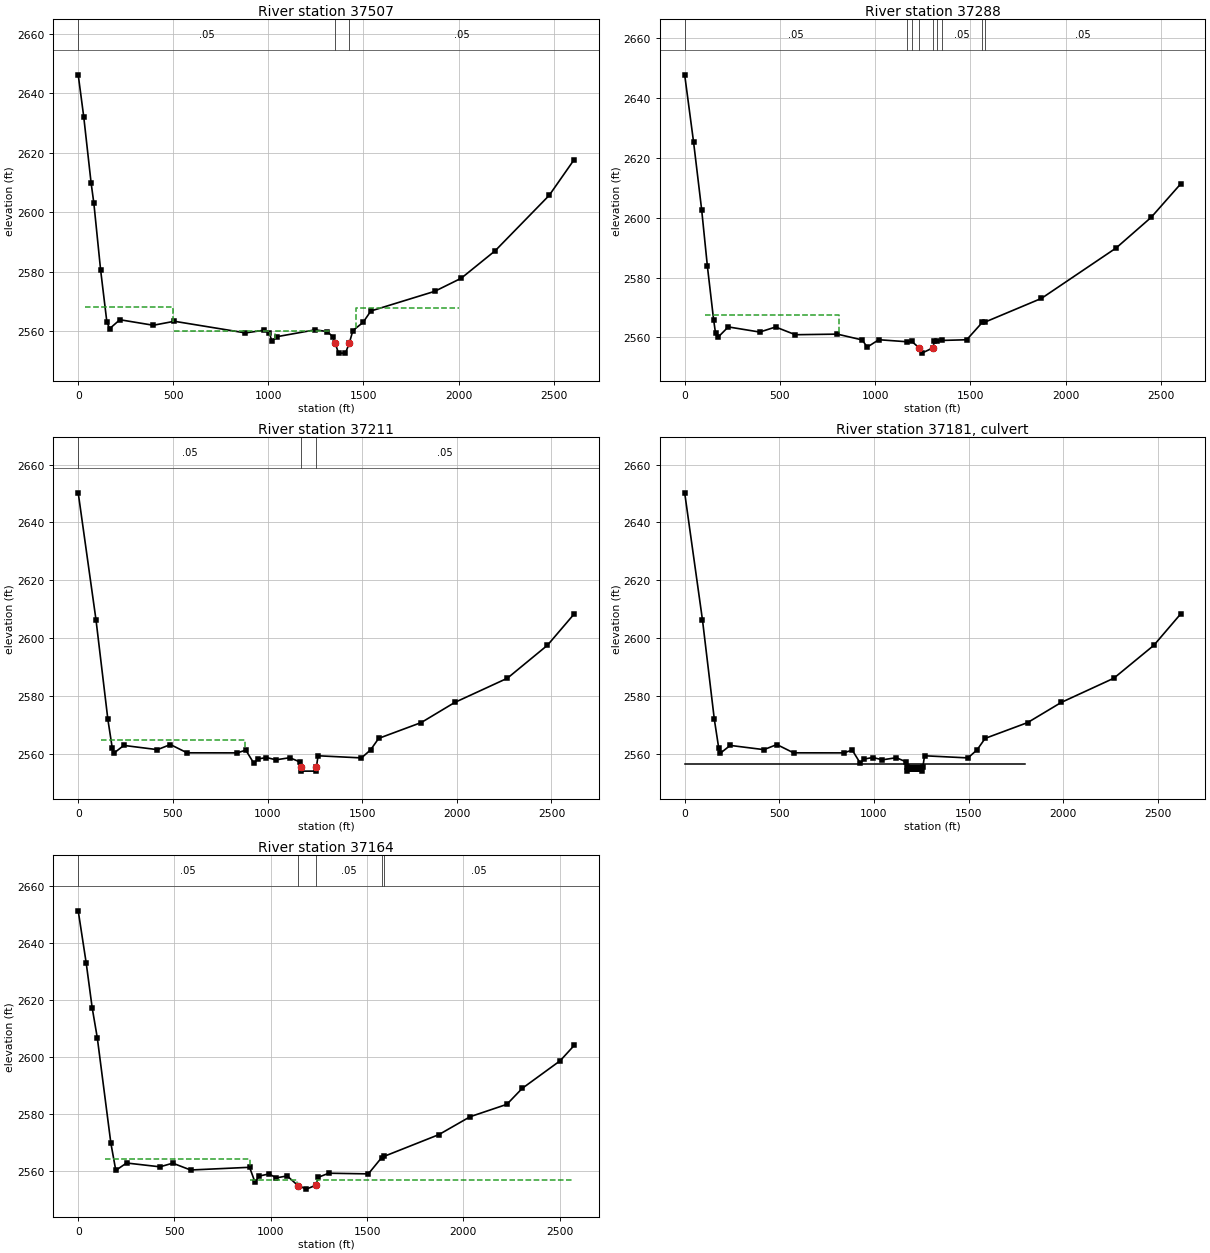
Type RM Length L Ch R = 1 ,37507   ,224.5,219.8,264.9
BEGIN DESCRIPTION:
xs 2 Invert lowered vs. LIDAR based on approximate underclearance from Effective FIS
invert = 2552.6
bw = 36.4
END DESCRIPTION:
XS GIS Cut Line= 4
2296300.81993699516737.8165034542295803.59394106 517447.09365909
2295555.88917388517758.5826311792294363.53067383518377.566551958
#Sta/Elev= 30
       0 2646.26      29 2632.16    67.6 2609.98    82.3    2603   117.7 2580.63
   150.7 2563.06   165.3 2560.84     219 2563.84   394.9 2561.98   505.4 2563.32
   879.1 2559.41   974.5 2560.28  1003.9 2559.53  1018.2 2556.72  1045.2 2558.14
  1245.9 2560.44  1308.9 2559.86  1340.5 2558.03  1351.1 2555.91  1368.8  2552.6
  1405.2  2552.6  1426.1 2556.12  1444.1  2560.2  1497.3 2562.91  1538.8 2566.78
  1874.1 2573.39  2013.5 2577.79  2192.3 2587.05  2476.2 2605.68  2607.6 2617.72
#Mann= 3 ,0,0
       0     .05       0  1351.1     .04       0  1426.1     .05       0
#XS Ineff= 4 ,-1
   37.18  498.59 2568.19  505.79 1009.092559.928 1032.17 1320.072560.005
    1461    2000  2567.7
Permanent Ineff=
       F       F       F       F
Bank Sta=1351.1,1426.1
XS Rating Curve= 0 ,0
Exp/Cntr(USF)=0,0
Minor Loss Coefficient=0
Exp/Cntr=0.5,0.3

Type RM Length L Ch R = 1 ,37288   ,71.2,76.2,92.2
BEGIN DESCRIPTION:
xs 4
END DESCRIPTION:
XS GIS Cut Line= 5
2296293.56433471516729.4507582782295747.52974408517429.576829763
2295563.31181428517618.8418261262295316.00555237517568.371160429
2294296.49810529 518199.25448164
#Sta/Elev= 30
       0 2647.73    46.4  2625.4    89.1 2602.67   119.3  2583.7   151.8 2565.94
     162 2561.36   174.6 2560.02   228.8 2563.49   394.1 2561.77   477.1 2563.46
   581.1 2560.88   801.1 2561.08   932.4 2559.13   957.9 2556.72  1018.9 2559.21
  1167.4 2558.53  1191.9 2558.66  1230.7 2556.49    1245 2554.73 1304.14 2556.51
  1310.3 2558.78  1323.2 2558.85  1351.2 2558.97  1480.4  2559.2  1561.8 2564.97
  1578.2 2565.15  1872.7 2573.02  2264.9 2589.87  2448.5 2600.09  2603.3 2611.26
#Mann= 9 ,-1,0
       0     .05       0  1167.4    .016       0  1191.9     .05       0
  1230.7     .04       0 1304.14     .05       0  1323.2    .016       0
  1351.2     .05       0  1561.8    .016       0  1578.2     .05       0
#XS Ineff= 1 ,-1
  107.86  811.56 2567.39
Permanent Ineff=
       F
Bank Sta=1230.7,1304.14
XS Rating Curve= 0 ,0
Exp/Cntr(USF)=0,0
Exp/Cntr=0.5,0.3

Type RM Length L Ch R = 1 ,37211   ,17.5,47.6,52.9
BEGIN DESCRIPTION:
xs 3
invert = 2554
c/e of 0.5/0.7 used to correct drawdown
END DESCRIPTION:
XS GIS Cut Line= 5
2296280.29586706516709.0696322032295719.10990782517410.980952655
2295578.12039382517553.0138413662295291.96953516 517471.98837338
2294268.72158128518142.672207286
#Sta/Elev= 30
       0 2650.24    94.1 2606.23   156.7 2571.86   179.5 2562.12     188 2560.19
   240.8 2562.89   418.5 2561.43     487 2563.19     575 2560.33   839.7 2560.31
   885.2 2561.26   927.8 2556.71   948.3 2558.18   993.7 2558.71  1044.8 2557.91
  1117.5 2558.64 1171.49 2557.16    1176 2555.57    1177    2554  1254.6    2554
 1258.15 2555.48  1267.1 2559.31  1496.4 2558.57  1544.2 2561.34  1587.3 2565.33
    1812  2570.8    1989 2577.75  2266.7 2586.12  2478.3 2597.51  2619.7 2608.34
#Mann= 3 ,0,0
       0     .05       0    1176     .04       0 1258.15     .05       0
#XS Ineff= 3 ,-1
  120.09  882.38 2564.91  882.38    1164  2556.5    1268  2619.7  2556.5
Permanent Ineff=
       F       F       F
Bank Sta=1176,1258.15
XS Rating Curve= 0 ,0
Exp/Cntr(USF)=0,0
Minor Loss Coefficient=0
Exp/Cntr=0.9,0.7

Type RM Length L Ch R = 2 ,37181   ,,,
BEGIN DESCRIPTION:
Low-water crossing. Private. No survey data available. Deck elevation based on LIDAR. Structure dimensions based on distance photographs. Concrete with low water passage openings. Assumed 2' diameter openings, 0.5' "deck depth", 1' spacing between openings. On left overbank side 4 wide oval openings, about 2' high and 4' wide estimated.
END DESCRIPTION:
Bridge Culvert--1,0,-1,-1, 0
Deck Dist Width WeirC Skew NumUp NumDn MinLoCord MaxHiCord MaxSubmerge Is_Ogee
16.99951,15,2.6,0, 2, 2, , , 0.98, 0, 0,0,,
       0    1800
  2556.5  2556.5
                
       0    1800
  2556.5  2556.5
                
BR Coef=-1 ,-1 , 0 ,, 0 ,,,0.8,0,,0,
WSPro=,,,, 1 ,,,, 0 ,,,, 0 ,,,,-1 ,-1 ,-1 , 0 , 0 , 0 , 0 , 0
Multiple Barrel Culv=4,2,4,15,0.016,0.5,1,29,1,2554,2554, 3,Culvert #2  , 0 ,17
    1179    1150    1184    1155    1189    1160
BC Culvert Barrel=1,Barrel #10,0
BC Culvert Barrel=2,Barrel #11,0
BC Culvert Barrel=3,Barrel #9,0
Culvert Bottom n=0.016
Multiple Barrel Culv=1,2,2,15,0.016,0.5,1,1,1,2554,2554, 21,Culvert #1  , 0 ,17
    1194    1165    1197    1168    1200    1171    1203    1174    1206    1177
    1209    1180    1212    1183    1215    1186    1218    1189    1221    1192
    1224    1195    1227    1198    1230    1201    1233    1204    1236    1207
    1239    1210    1242    1213    1245    1216    1248    1219    1251    1222
    1254    1225
BC Culvert Barrel=1,Barrel #11,0
BC Culvert Barrel=2,Barrel #10,0
BC Culvert Barrel=3,Barrel #9,0
BC Culvert Barrel=4,Barrel #3,0
BC Culvert Barrel=5,Barrel #2,0
BC Culvert Barrel=6,Barrel #1,0
BC Culvert Barrel=7,Barrel #4,0
BC Culvert Barrel=8,Barrel #5,0
BC Culvert Barrel=9,Barrel #6,0
BC Culvert Barrel=10,Barrel #7,0
BC Culvert Barrel=11,Barrel #8,0
BC Culvert Barrel=12,Barrel #12,0
BC Culvert Barrel=13,Barrel #13,0
BC Culvert Barrel=14,Barrel #14,0
BC Culvert Barrel=15,Barrel #15,0
BC Culvert Barrel=16,Barrel #16,0
BC Culvert Barrel=17,Barrel #17,0
BC Culvert Barrel=18,Barrel #18,0
BC Culvert Barrel=19,Barrel #19,0
BC Culvert Barrel=20,Barrel #20,0
BC Culvert Barrel=21,Barrel #21,0
Culvert Bottom n=0.016
BC Design=,, 0 ,, 0 ,,,,,,
BC Use User HTab Curves=0
BC User HTab FreeFlow(D)= 0

Type RM Length L Ch R = 1 ,37164   ,289.5,259.3,142.1
BEGIN DESCRIPTION:
xs 2
c/e of 0.5/0.7 used to correct drawdown
END DESCRIPTION:
XS GIS Cut Line= 5
2296273.74510091516696.2297780592295740.90516634517369.349357319
2295605.65716953 517511.382246032295319.50631087517430.356778044
2294296.25835699 518101.04061195
#Sta/Elev= 30
       0 2651.26    41.2 2633.04    72.6 2617.16    99.2 2606.59   169.6  2569.6
   195.1 2560.05   251.2 2562.64   424.6  2561.3     491 2562.58   583.7 2560.18
     890 2561.13   917.6 2555.98   940.8 2558.07   991.9 2558.81  1027.8 2557.39
  1085.3 2558.11  1140.6 2554.73    1185 2553.46  1233.4 2554.82  1247.4 2557.65
  1301.4 2559.05  1506.7 2558.82    1576 2564.56  1587.6 2564.95  1872.5  2572.6
  2035.1  2578.9  2226.1 2583.26  2305.7 2588.86  2502.8 2598.57  2575.5 2603.95
#Mann= 5 ,-1,0
       0     .05       0  1140.6     .04       0  1233.4     .05       0
    1576    .016       0  1587.6     .05       0
#XS Ineff= 3 ,-1
  140.68  889.79 2563.98  889.79  1134.6  2556.5    1239  2575.5  2556.5
Permanent Ineff=
       F       F       F
Bank Sta=1140.6,1233.4
XS Rating Curve= 0 ,0
Exp/Cntr(USF)=0,0
Minor Loss Coefficient=0
Exp/Cntr=0.5,0.3