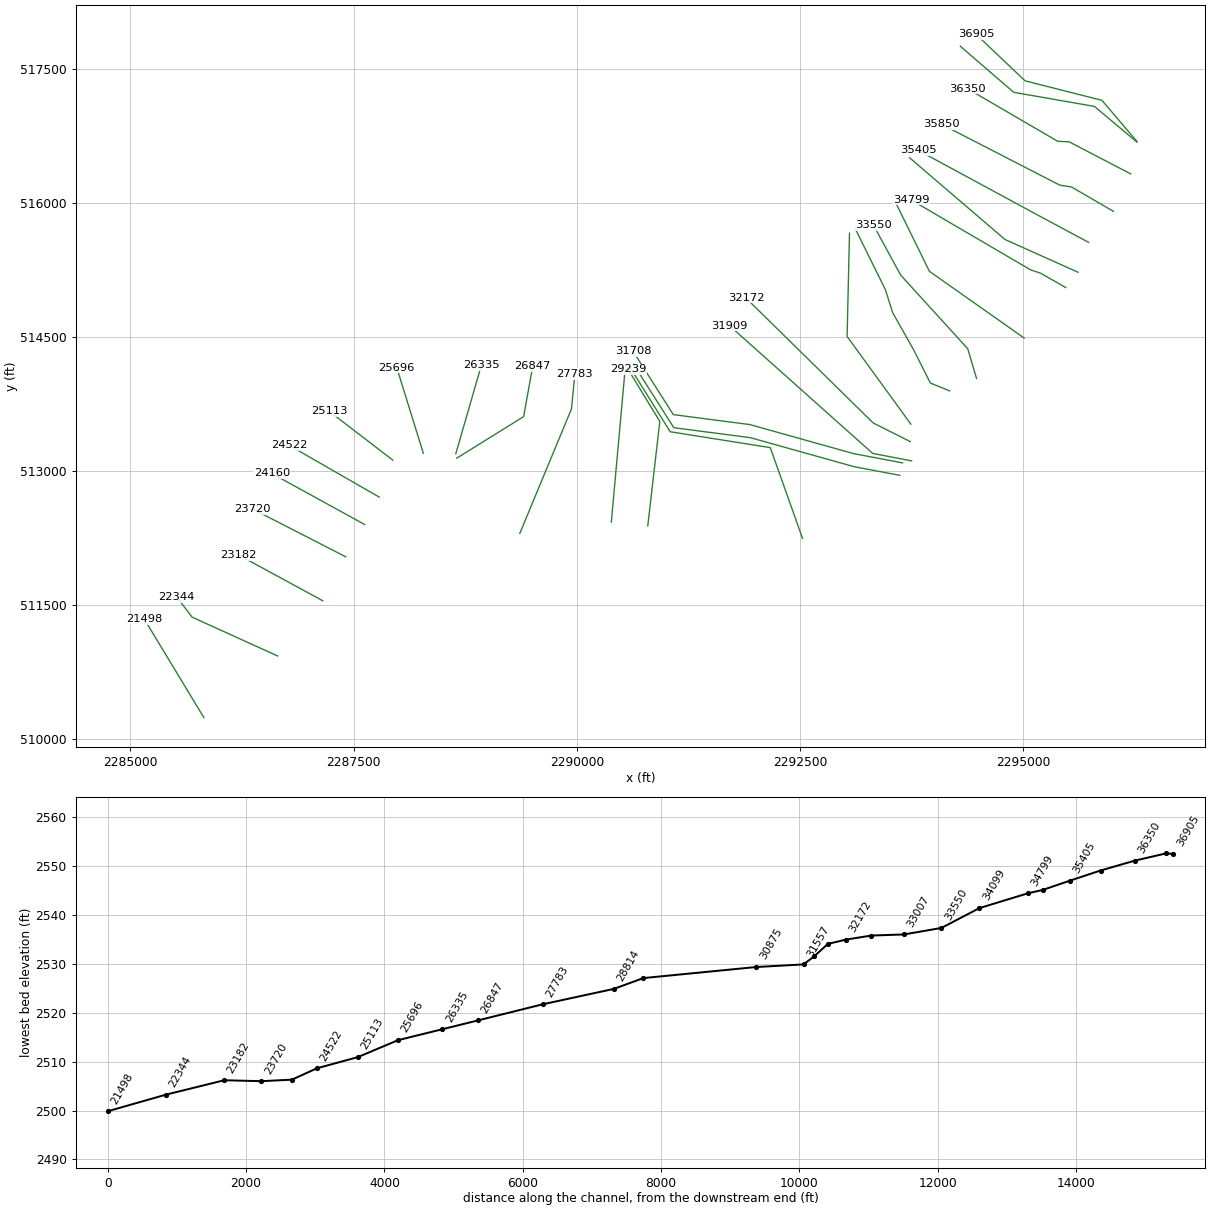
HEC-RAS study DEERCK.prj: DEERCK

--- DEERCK.g01 (geometry) --- (continued)

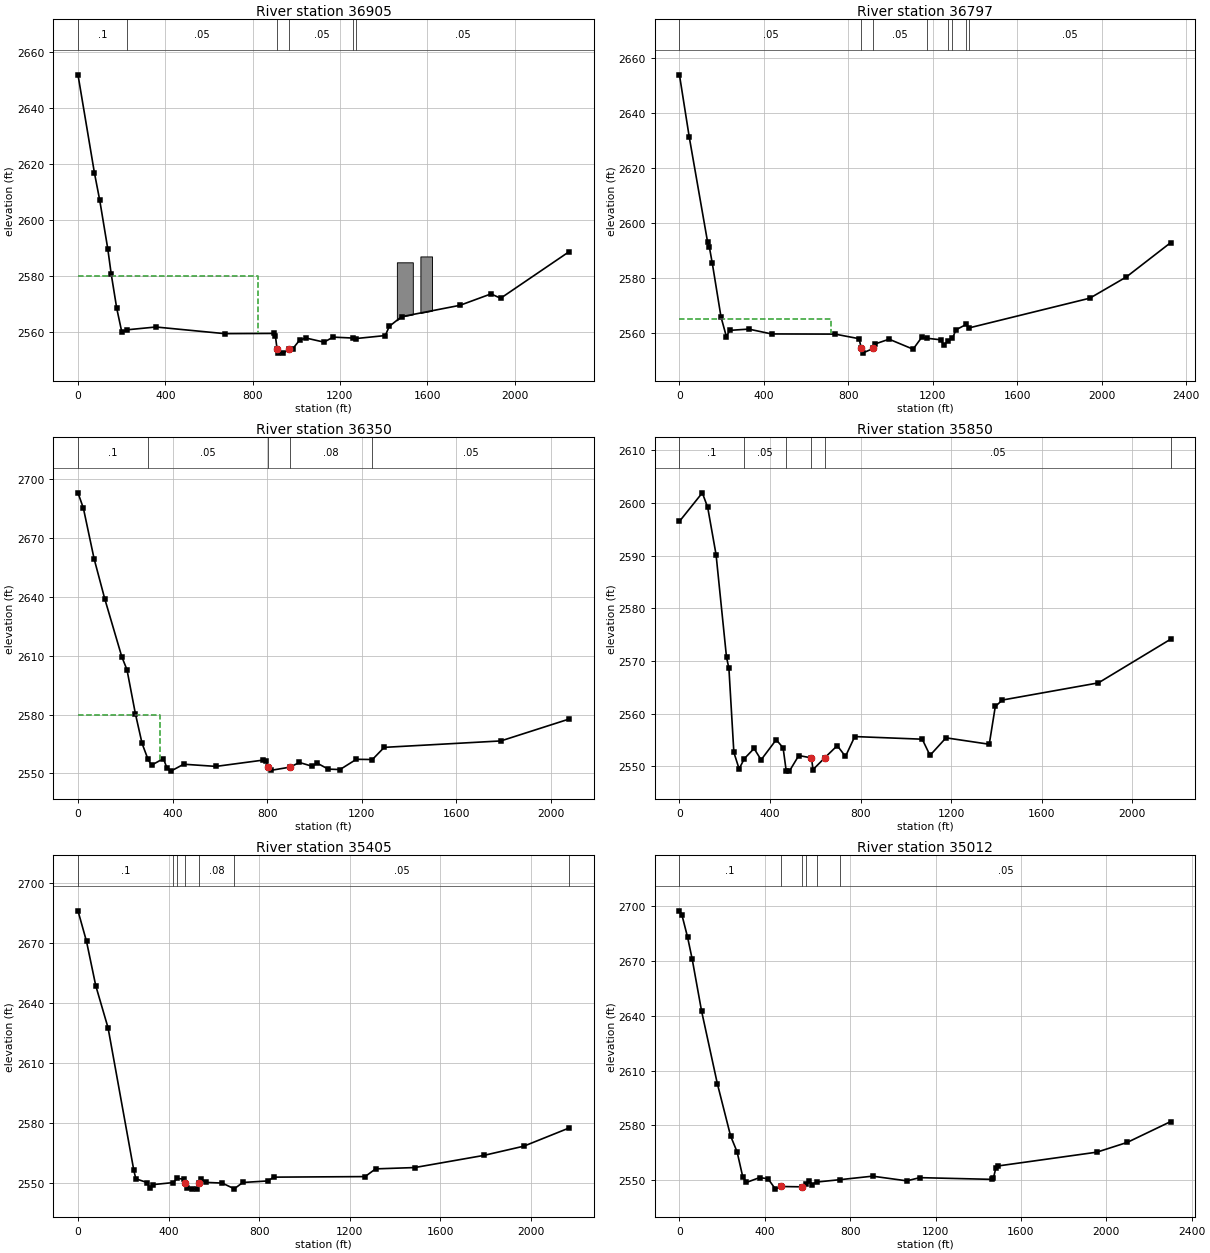
Type RM Length L Ch R = 1 ,36905   ,106,107.3,126.2
BEGIN DESCRIPTION:
xs 1
END DESCRIPTION:
XS GIS Cut Line= 4
2296270.51781963516689.2248281772295878.62520158517150.017991801
2295017.71865948517368.1558603962294467.79584892517890.202399456
#Sta/Elev= 30
       0 2651.79    75.4 2616.77    99.7 2607.01   136.5 2589.71     152 2580.83
   177.6 2568.45   201.2 2559.86     223 2560.81     357 2561.82   672.1 2559.45
   896.3 2559.53   904.5 2558.66  911.95    2554   916.9 2552.66   941.1  2552.5
   968.7 2553.93   982.9 2553.95  1015.9 2557.17  1044.8 2557.88  1127.4 2556.42
  1168.6 2558.21  1261.6 2557.87  1274.6 2557.71    1408 2558.77    1426 2562.04
  1482.2  2565.5  1750.1 2569.56  1892.3 2573.63  1936.4 2572.08  2251.3 2588.75
#Mann= 6 ,-1,0
       0      .1       0     223     .05       0  911.95     .04       0
   968.7     .05       0  1261.6    .016       0  1274.6     .05       0
#XS Ineff= 2 , 0
             825    2580
Permanent Ineff=
       F       F
#Block Obstruct= 2 ,-1
    1461    1534  2584.9  1568.8    1622    2587
Bank Sta=911.95,968.7
XS Rating Curve= 0 ,0
Exp/Cntr(USF)=0,0
Exp/Cntr=0.3,0.1

Type RM Length L Ch R = 1 ,36797   ,488.7,447,420.6
XS GIS Cut Line= 4
2296270.50665554516681.9083743612295794.57783134517081.720753063
2294891.15355204517239.4029151152294292.94458866517755.132397026
#Sta/Elev= 30
       0 2653.72    46.6 2631.05   133.6 2592.87   141.9 2591.08   155.7 2585.25
     197 2565.72   222.5 2558.59   238.1 2560.87   328.5 2561.33   436.6 2559.57
   737.3 2559.51   851.4 2557.84  861.55 2554.32   867.6  2552.6  918.73 2554.32
   927.4 2555.94   993.5 2557.66  1107.2 2554.03  1147.8 2558.31  1171.2 2558.02
  1237.1 2557.45  1253.4 2555.49  1273.7 2557.12  1293.9 2557.98  1310.2 2561.07
    1359 2563.03  1371.1 2561.74  1944.8 2572.57  2117.8 2580.28  2328.5 2592.79
#Mann= 8 ,-1,0
       0     .05       0  861.55     .04       0  918.73     .05       0
  1171.2      .1       0  1273.7     .07       0  1293.9     .04       0
    1359     .07       0  1371.1     .05       0
#XS Ineff= 2 , 0
          717.22 2564.99
Permanent Ineff=
       F       F
Bank Sta=861.55,918.73
XS Rating Curve= 0 ,0
Exp/Cntr(USF)=0,0
Minor Loss Coefficient=0
Exp/Cntr=0.3,0.1

Type RM Length L Ch R = 1 ,36350   ,505.3,500.1,472.9
XS GIS Cut Line= 4
2296200.60789714516326.169161438 2295511.1461378516685.384531849
2295383.68261926516691.178328146 2294369.7682673517282.145550436
#Sta/Elev= 30
       0 2692.98      23 2685.07    68.1 2659.41   113.2 2638.97   185.4 2609.39
   207.2 2602.85   242.7 2580.47   271.1 2565.25   296.1  2557.2     311 2554.16
   361.4 2557.53   376.2 2552.77   392.9 2551.14     447 2554.66   583.8 2553.55
   780.8 2556.72   796.4 2556.36   804.4 2553.22   818.4 2551.58  895.76 2553.15
   936.9 2555.55     991  2553.6  1010.9 2555.28  1058.2 2552.17  1108.2 2551.94
  1177.6 2557.17  1245.4 2557.05  1295.2 2563.25  1788.8 2566.53  2078.6 2577.72
#Mann= 5 ,-1,0
       0      .1       0   296.1     .05       0   804.4     .04       0
  895.76     .08       0  1245.4     .05       0
#XS Ineff= 2 , 0
          344.93  2579.6
Permanent Ineff=
       F       F
Bank Sta=804.4,895.76
XS Rating Curve= 0 ,0
Exp/Cntr(USF)=0,0
Exp/Cntr=0.3,0.1

Type RM Length L Ch R = 1 ,35850   ,460.9,445.3,413.2
XS GIS Cut Line= 4
2296007.98174254 515906.461632582295538.18385385516179.392988581
2295406.31155913516200.2424585442294078.53221573516883.485905717
#Sta/Elev= 30
       0  2596.5     101 2601.92   124.7 2599.17   161.7  2590.2   207.9 2570.69
   218.4 2568.66   240.3 2552.67   263.5 2549.52   286.6 2551.47   329.6  2553.4
   360.6 2551.24   427.4 2555.06   457.8 2553.52   471.6 2549.12   485.5  2549.1
   527.1 2552.06     583 2551.61   589.9 2549.39   641.1  2551.6   696.9 2553.94
   733.2 2551.88   774.2 2555.66  1072.3 2555.16  1106.6 2552.09  1177.2 2555.42
  1368.2  2554.2  1394.9 2561.37    1426 2562.59  1850.3 2565.85  2170.1 2574.16
#Mann= 6 ,-1,0
       0      .1       0   286.6     .05       0   471.6     .08       0
     583     .04       0   641.1     .05       0  2170.1     .05       0
Bank Sta=583,641.1
XS Rating Curve= 0 ,0
Exp/Cntr(USF)=0,0
Exp/Cntr=0.3,0.1

Type RM Length L Ch R = 1 ,35405   ,381,392.4,405.4
Node Name=C
XS GIS Cut Line= 3
2295729.37913165515559.4567848062295196.34987233 515845.28406879
2293819.35761909516590.752525666
#Sta/Elev= 30
       0 2686.09    37.7  2670.8    78.5 2648.67     133 2627.55   246.5 2556.48
   255.5 2552.19   305.5 2550.28   316.8 2547.55   333.1 2549.29   418.7 2550.26
   439.4 2552.37   468.9 2551.96  473.76 2549.99   482.5  2547.5     503 2547.01
   527.9 2547.27     534 2549.95   545.4  2552.2   563.5 2550.38   636.9 2550.04
   690.5 2547.17   727.8 2550.33   839.9 2551.11   864.3    2553  1268.4 2553.27
  1314.6 2557.13  1487.4 2557.79  1792.2 2563.85  1969.6 2568.48  2170.7 2577.62
#Mann= 7 ,-1,0
       0      .1       0   418.7     .05       0   439.4     .08       0
  473.76     .04       0     534     .08       0   690.5     .05       0
  2170.7     .05       0
Bank Sta=473.76,534
XS Rating Curve= 0 ,0
Exp/Cntr(USF)=0,0
Exp/Cntr=0.3,0.1

Type RM Length L Ch R = 1 ,35012   ,186.7,213.6,170.1
XS GIS Cut Line= 3
 2295610.7761126515225.0894266082294793.78597681 515591.10100744
2293725.16287921516506.129959518
#Sta/Elev= 30
       0 2697.56    11.1 2695.54    38.4 2682.97    59.8 2671.05   103.7 2642.66
   177.6 2602.87   239.5  2574.3   270.2  2565.5   296.5  2551.9     314 2548.78
   375.4 2551.44   414.9  2550.8   449.9 2545.12   473.5 2546.56   574.1 2546.38
   594.6 2547.71   607.7 2549.56   620.9 2547.64   642.8    2549   752.4  2550.3
   904.6 2552.22  1065.2 2549.66    1126 2551.41  1466.1 2550.46  1471.3 2551.32
  1482.2 2556.67  1490.8 2557.78  1955.8 2565.37    2098 2570.72  2302.1 2582.16
#Mann= 6 ,-1,0
       0      .1       0   473.5     .04       0   574.1      .1       0
   594.6     .08       0   642.8      .1       0   752.4     .05       0
Bank Sta=473.5,574.1
XS Rating Curve= 0 ,0
Exp/Cntr(USF)=0,0
Exp/Cntr=0.3,0.1

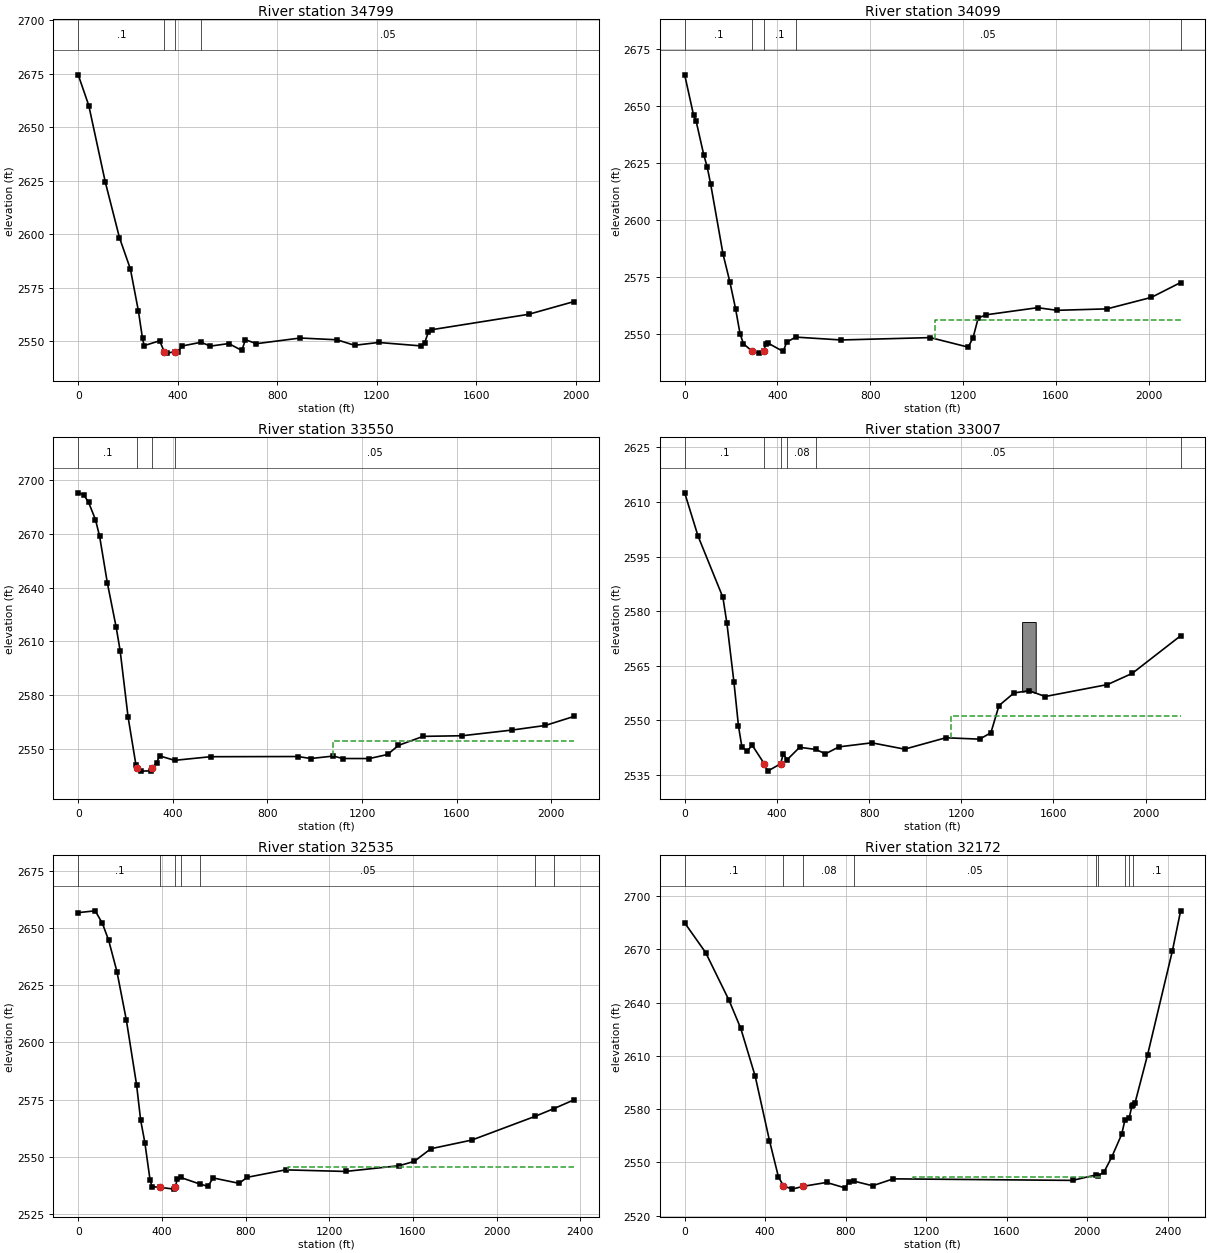
Type RM Length L Ch R = 1 ,34799   ,717.9,699.5,664.1
XS GIS Cut Line= 4
2295474.45209458515053.4652415382295192.48734147515213.760272421
2295078.54268096515252.3855810672293742.10700179516034.548081157
#Sta/Elev= 30
       0 2674.44    42.5 2660.08   108.4 2624.55   165.7  2598.4   209.7 2583.73
   241.9 2564.11   258.4 2551.29   264.9 2547.92   327.3  2550.2   346.2 2544.99
   358.8 2544.43     388 2545.14   400.7 2545.08   417.6 2547.76   493.8  2549.5
   530.8  2547.7     605  2548.9   657.5 2545.68   672.1 2550.71   715.9 2548.84
   892.3 2551.49  1040.2 2550.66  1110.6 2548.09  1207.1 2549.41    1379 2547.79
  1392.9 2549.39  1406.8 2554.14  1420.5 2555.37    1810 2562.56  1993.2 2568.53
#Mann= 4 ,-1,0
       0      .1       0   346.2     .04       0     388      .1       0
   493.8     .05       0
Bank Sta=346.2,388
XS Rating Curve= 0 ,0
Exp/Cntr(USF)=0,0
Exp/Cntr=0.3,0.1

Type RM Length L Ch R = 1 ,34099   ,570.8,549.2,474.1
XS GIS Cut Line= 3
 2295007.4139778514488.3726856732293946.78825784515235.323595068
2293576.06641144515990.143221903
#Sta/Elev= 30
       0 2663.67    38.2 2646.01    48.8 2643.57    82.2 2628.56    96.9 2623.24
   111.6 2615.92   165.4 2584.88   194.8  2572.7   219.2 2561.01   238.8  2549.9
   253.5 2545.52     290  2542.3     322 2541.41  342.61 2542.48   348.7 2545.46
   361.1 2545.71   424.9 2542.13   439.4  2546.2   478.5 2548.45   674.6 2547.19
  1059.3 2548.23  1222.2 2544.05    1243 2548.08  1265.7 2556.88  1300.6 2558.26
  1521.7 2561.37  1605.4 2560.22  1820.7 2560.85  2011.9 2565.89  2138.2 2572.42
#Mann= 5 ,-1,0
       0      .1       0     290     .04       0  342.61      .1       0
   478.5     .05       0  2138.2     .05       0
#XS Ineff= 2 , 0
                         1080.54         2556.01
Permanent Ineff=
       F       F
Bank Sta=290,342.61
XS Rating Curve= 0 ,0
Exp/Cntr(USF)=0,0
Exp/Cntr=0.3,0.1

Type RM Length L Ch R = 1 ,33550   ,533.2,542.9,479.4
XS GIS Cut Line= 4
2294474.58744696514035.1880841312294376.03497195 514368.38930917
2293625.15897186515192.7885842652293321.97296435515749.120190283
#Sta/Elev= 30
       0 2692.94    22.9 2691.93    43.8 2687.64      73 2677.91    90.5 2668.59
     123 2642.67   160.6  2617.7   177.3 2604.61   210.6 2567.76     244 2540.81
   248.2    2539   264.9 2537.35   306.6  2537.5   312.42539.208   331.6 2542.08
   344.1 2545.87   407.4 2543.38   559.5 2545.41   929.4 2545.51   982.9  2544.4
  1077.9 2545.77  1118.1  2544.4  1230.4 2544.38  1307.8 2546.66  1353.1 2551.72
  1457.7 2556.78  1623.4 2557.14  1835.1 2560.33  1974.5 2562.89  2096.2 2567.96
#Mann= 4 ,-1,0
       0      .1       0   248.2     .04       0   312.4      .1       0
   407.4     .05       0
#XS Ineff= 2 , 0
                         1077.06         2553.95
Permanent Ineff=
       F       F
Bank Sta=248.2,312.4
XS Rating Curve= 0 ,0
Exp/Cntr(USF)=0,0
Exp/Cntr=0.3,0.1

Type RM Length L Ch R = 1 ,33007   ,461.9,472.4,518.5
XS GIS Cut Line= 6
2294173.73083578513896.0411707762293957.56563468513984.164351652
2293774.32113693514348.2474722232293534.10645098514775.473681468
2293453.50535685 515030.910215972293119.76775878515705.588531241
#Sta/Elev= 30
       0 2612.51    57.8 2600.64   165.8 2583.78   183.1 2576.72   213.8 2560.45
   233.4  2548.4     248 2542.78   270.4 2541.45   292.8 2543.15  345.99 2537.98
     360 2536.02  416.14 2538.04   427.1 2540.63     445 2539.19   498.8 2542.57
   568.9 2541.98   610.6 2540.78   669.6 2542.69   811.9  2543.8   954.2 2542.06
    1133 2545.19  1279.8 2544.81  1328.6 2546.57  1363.6 2554.03  1429.1 2557.52
  1494.3 2558.11  1564.4 2556.53  1834.4 2559.81  1941.5 2562.88  2151.7 2573.22
#Mann= 6 ,-1,0
       0      .1       0  345.99     .04       0  416.14      .1       0
     445     .08       0   568.9     .05       0  2151.7     .05       0
#XS Ineff= 2 , 0
                            1155         2551.17
Permanent Ineff=
       F       F
#Block Obstruct= 1 ,-1
    1464    1523    2577
Bank Sta=345.99,416.14
XS Rating Curve= 0 ,0
Exp/Cntr(USF)=0,0
Exp/Cntr=0.3,0.1

Type RM Length L Ch R = 1 ,32535   ,352.1,362.5,400.8
Node Name=B
XS GIS Cut Line= 3
2293739.44585513513523.5453052772293025.25394091 514505.55918733
 2293052.0361377515661.657348474
#Sta/Elev= 30
       0 2656.78    81.2 2657.57   115.8 2652.05   145.5 2644.68     185 2631.01
     230 2609.82     279 2581.44   298.4 2566.02   318.6 2556.11   343.3 2539.84
   353.2 2536.86   392.9 2536.56   457.1 2535.79   464.1 2536.63   473.1 2540.13
     4902540.882     5802538.063   620.3 2537.01   644.8 2540.69   768.6 2538.33
   808.1 2540.97   991.2 2544.22  1277.9 2543.53    1534 2546.03    1606 2547.92
    1686 2553.47  1881.5 2557.26 2184.262567.645 2274.262571.039  2370.7 2574.88
#Mann= 7 ,-1,0
       0      .1       0   392.9     .04       0   464.1     .08       0
     490      .1       0     580     .05       0 2184.26     .04       0
 2274.26     .05       0
#XS Ineff= 2 , 0
                         1004.69         2545.59
Permanent Ineff=
       F       F
Bank Sta=392.9,464.1
XS Rating Curve= 0 ,0
Exp/Cntr(USF)=0,0
Exp/Cntr=0.3,0.1

Type RM Length L Ch R = 1 ,32172   ,259.2,263,276.8
XS GIS Cut Line= 3
2293733.28766076 513328.316868912293318.07588094513536.544860108
2291891.09488339514937.508452102
#Sta/Elev= 30
       0 2684.93   104.2 2668.21   220.5  2641.3   278.7 2625.48   350.2 2598.63
   421.3 2562.31   465.4 2542.03   490.4 2536.81   534.4 2534.97   587.9 2536.53
   705.2 2538.74   797.9 2535.61   814.2 2539.12   842.2 2539.45   933.6 2536.86
  1036.4 2540.76  1927.1 2539.89  2042.3 2542.92  2055.9 2542.49  2084.2 2544.77
    2121 2552.79  2171.2 2565.83  2188.1 2574.14  2208.7 2575.18  2222.8 2582.07
  2228.5 2582.53    2237 2583.24  2300.2 2610.71  2423.5 2669.27  2464.2 2691.72
#Mann= 9 ,-1,0
       0      .1       0   490.4     .04       0   587.9     .08       0
   842.2     .05       0  2042.3     .04       0  2055.9     .05       0
  2188.1    .016       0  2208.7     .04       0  2228.5      .1       0
#XS Ineff= 3 ,-1
 1037.44 1119.02 2540.63 1134.46 1262.35 2541.58  1283.3 2079.31 2541.61
Permanent Ineff=
       F       F       F
Bank Sta=490.4,587.9
XS Rating Curve= 0 ,0
Exp/Cntr(USF)=0,0
Exp/Cntr=0.3,0.1

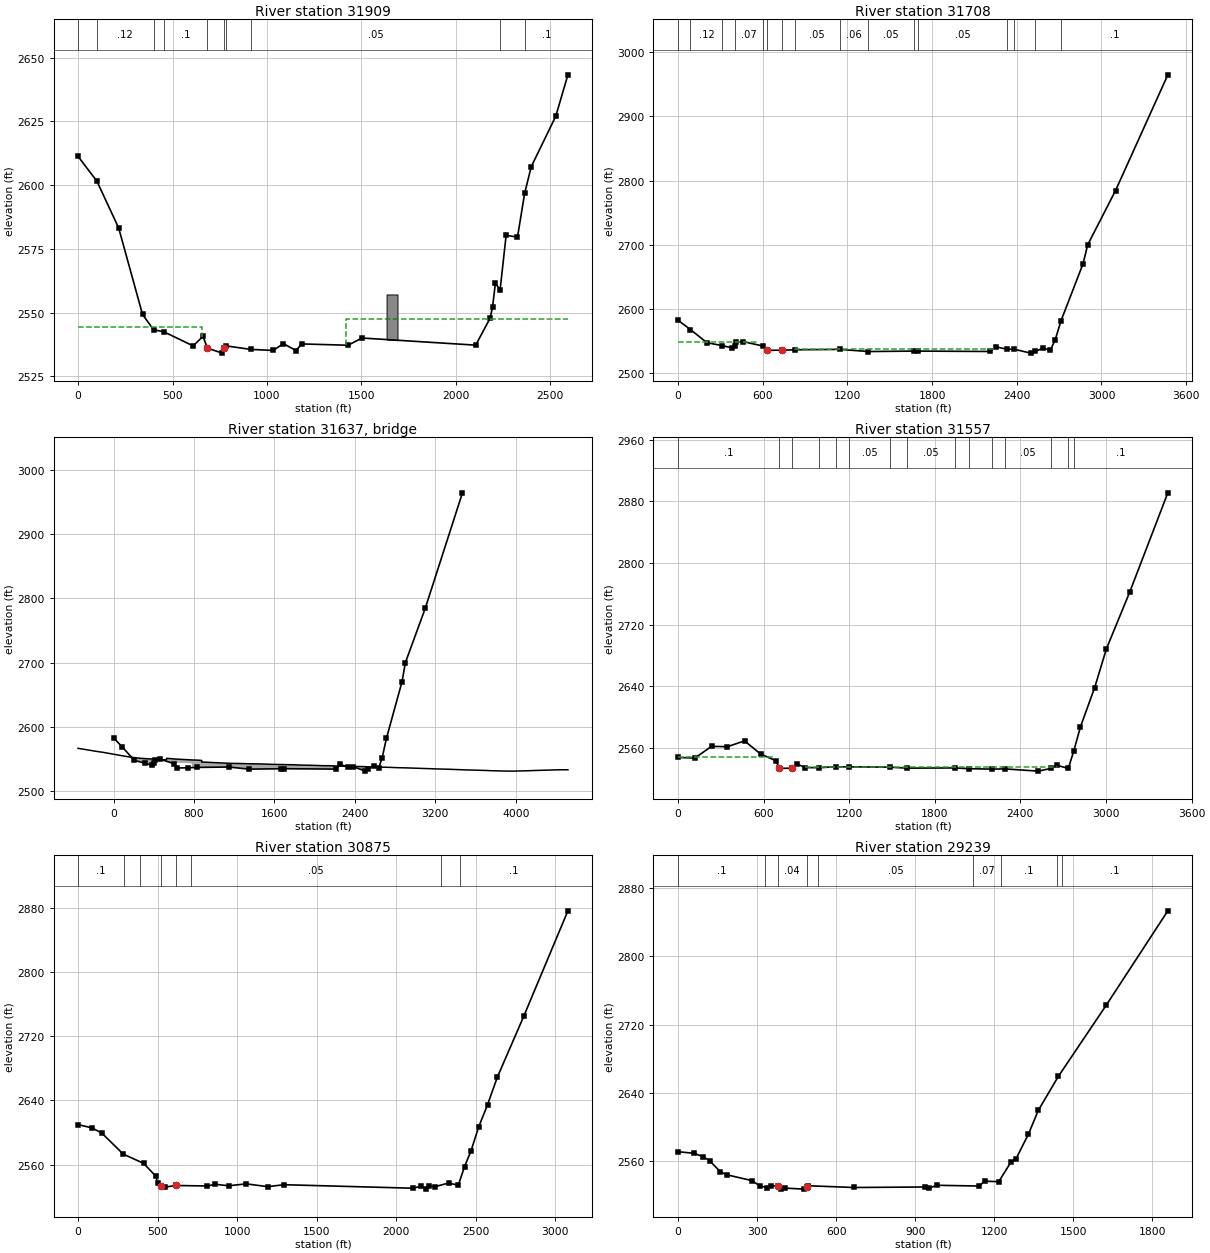
Type RM Length L Ch R = 1 ,31909   ,172.6,201,319.4
BEGIN DESCRIPTION:
xs 4
lidar = 2534.12
difference frm the effective = 3.69
END DESCRIPTION:
XS GIS Cut Line= 3
2293747.42049275513112.5031849492293311.58122712 513196.31842834
2291707.91623691514626.765248872
#Sta/Elev= 30
       0 2611.26     1002601.526   215.2 2583.15   341.4 2549.26     4002543.231
  453.832542.472   609.2 2536.93   661.4 2540.67  684.95 2536.03   763.6 2534.09
  771.74 2536.03  783.832536.931  913.832535.549  1032.6 2535.15  1087.1 2537.81
  1154.2 2535.08  1183.4  2537.7  1429.3 2537.18  1502.7 2540.02  2104.6 2537.22
  2180.7 2547.74  2193.8 2552.05    2209 2561.55 2233.832558.858  2265.9 2580.32
    2326 2579.59 2363.832596.782  2398.8 2607.24  2528.1 2626.92  2592.8 2643.25
#Mann= 10 ,-1,0
       0      .1       0     100     .12       0     400     .06       0
  453.83      .1       0  684.95     .04       0  771.74     .08       0
  783.83      .1       0  913.83     .05       0 2233.83     .06       0
 2363.83      .1       0
#XS Ineff= 2 , 0
          657.46 2544.21 1419.97         2547.66
Permanent Ineff=
       F       F
#Block Obstruct= 1 ,-1
    1633  1690.9  2557.1
Bank Sta=684.95,771.74
XS Rating Curve= 0 ,0
Exp/Cntr(USF)=0,0
Exp/Cntr=0.5,0.3

Type RM Length L Ch R = 1 ,31708   ,149.4,151.7,145.2
BEGIN DESCRIPTION:
xs 3
END DESCRIPTION:
XS GIS Cut Line= 5
2293646.55848113513090.241534987 2293101.1368318 513193.23154495
2291936.11127173513519.0816058132291079.08097466 513630.67409241
2290628.24732881514340.402307167
#Sta/Elev= 30
       0  2582.8    87.9 2568.27     206 2547.69   315.5 2543.17     381 2539.81
   401.4 2543.17   413.6 2548.69   462.4 2549.37   601.7  2542.6   630.52535.845
   738.8 2536.14     826 2536.71  1146.5 2537.34  1349.4    2534  1669.2 2534.69
  1698.3 2534.69  2212.5 2534.09  2252.8 2541.29  2330.5 2537.54  2380.5 2537.66
  2498.9 2531.52  2532.1 2534.26  2587.8 2539.42  2636.8 2535.62  2671.8 2552.13
  2714.1 2582.29    2869 2670.41  2902.1 2699.98  3099.6 2784.59  3469.9 2964.69
#Mann= 16 ,-1,0
       0     .06       0    87.9     .12       0   315.5     .06       0
   401.4     .07       0   601.7      .1       0   630.5     .04       0
   738.8      .1       0     826     .05       0  1146.5     .06       0
  1349.4     .05       0  1669.2     .07       0  1698.3     .05       0
  2330.5     .08       0  2380.5     .05       0  2532.1     .06       0
  2714.1      .1       0
#XS Ineff= 2 ,-1
       0     550 2548.39     830 2254.22 2537.58
Permanent Ineff=
       F       F
Bank Sta=630.5,738.8
XS Rating Curve= 0 ,0
Exp/Cntr(USF)=0,0
Exp/Cntr=0.5,0.3

Type RM Length L Ch R = 3 ,31637   ,,,
BEGIN DESCRIPTION:
Cass Road (Route 66)
no survey data provided
road deck updated per lidar elevations
structure opening measured from imagery - approx. 178'
deck thickness assumed at 3'
guardrail measured per imagery, 2.5' height
channel not burned
END DESCRIPTION:
Bridge Culvert--1,0,-1,-1, 0
Deck Dist Width WeirC Skew NumUp NumDn MinLoCord MaxHiCord MaxSubmerge Is_Ogee
51,34,2.6,0, 60, 60, , , 0.98, 0, 0,0,,
    -354-192.281-144.263-112.201 112.323 174.083 219.478  281.38 339.515 389.719
 475.339     526     526 590.889 595.016     601     779 785.926 826.736     876
     876  918.25  983.891022.0361063.4591179.4421233.2921336.4021457.1341575.887
1718.3611783.2431852.1812009.5892086.3192138.8182268.0472381.1222413.4292478.644
2522.4312578.7562727.8692816.4272907.3563232.0393324.8763526.5673591.1083708.256
3768.9993933.3643990.2194067.023 4087.424244.7954349.7534386.1094465.1094518.918
2566.4922562.2792561.0992560.4362554.1422552.6412551.6982550.802 2550.132549.773
2548.8212548.3942550.8942550.199 2549.93 2549.882548.3782548.3142548.1612547.591
2545.0912544.9072544.3442544.1352543.7262542.9692542.8942542.4792542.1542541.549
2541.0312540.8962540.4382539.8662539.3952539.4012538.5872538.1722538.2432538.036
2537.6912537.4092536.8932536.3542536.0122534.2812533.9062532.716 2532.522531.936
2531.505 2530.94 2530.972531.3682531.3762532.2162532.6082532.8722533.0822533.042
                                                                                
                                         2544.382542.878
                                                                                
                                                                                
                                                                                
                                                                                
    -268-106.281 -58.263 -26.201 198.323 260.083 305.478  367.38 425.515 475.719
 561.339     612     612 676.889 681.016     687     865 871.926 912.736     962
     962 1004.25 1069.891108.0361149.4591265.4421319.2921422.4021543.1341661.887
1804.3611869.2431938.1812095.5892172.3192224.8182354.0472467.1222499.4292564.644
2608.4312664.7562813.8692902.4272993.3563318.0393410.8763612.5673677.1083794.256
3854.9994019.3644076.2194153.023 4173.424330.7954435.7534472.1094551.1094604.918
2566.4922562.2792561.0992560.4362554.1422552.6412551.6982550.802 2550.132549.773
2548.8212548.3942550.8942550.199 2549.93 2549.882548.3782548.3142548.1612547.591
2545.0912544.9072544.3442544.1352543.7262542.9692542.8942542.4792542.1542541.549
2541.0312540.8962540.4382539.8662539.3952539.4012538.5872538.1722538.2432538.036
2537.6912537.4092536.8932536.3542536.0122534.2812533.9062532.716 2532.522531.936
2531.505 2530.94 2530.972531.3682531.3762532.2162532.6082532.8722533.0822533.042
                                                                                
                                         2544.382542.878
                                                                                
                                                                                
                                                                                
                                                                                
BR Coef=-1 ,-1 , 0 ,, 0 ,,,0.8,0,1.2,0,
WSPro=,,,, 1 ,,,, 0 ,,,, 0 ,,,,-1 ,-1 ,-1 , 0 , 0 , 0 , 0 , 0
BR U #Sta/Elev= 30
       0  2582.8    87.9 2568.27     206 2547.69   315.5 2543.17     381 2539.81
   401.4 2543.17   413.6 2548.69   462.4 2549.37   601.7  2542.6   630.52535.845
   738.8 2536.14     826 2536.71  1146.5 2537.34  1349.4    2534  1669.2 2534.69
  1698.3 2534.69  2212.5 2534.09  2252.8 2541.29  2330.5 2537.54  2380.5 2537.66
  2498.9 2531.52  2532.1 2534.26  2587.8 2539.42  2636.8 2535.62  2671.8 2552.13
  2714.1 2582.29    2869 2670.41  2902.1 2699.98  3099.6 2784.59  3469.9 2964.69
BR U #Mann= 16
       0     .06    87.9     .12   315.5     .06   401.4     .07   601.7      .1
   630.5    .035   738.8      .1     826     .05  1146.5     .06  1349.4     .05
  1669.2     .07  1698.3     .05  2330.5     .08  2380.5     .05  2532.1     .06
  2714.1      .1
BR D #Sta/Elev= 30
       0  2547.7   117.9 2546.81   235.9 2562.07   345.8 2561.56   466.7 2569.11
     579 2552.13     687 2543.31   710.6 2533.51   799.2 2533.65   832.4 2539.38
   890.5 2534.53   986.1 2534.36  1106.6  2535.5  1202.1 2535.47  1484.5 2535.02
  1606.4  2533.8  1940.5 2534.04  2040.1 2533.04  2201.5  2532.5  2290.1 2532.81
  2524.2 2529.89  2613.6  2533.4    2655 2537.47  2735.5 2533.48  2773.5 2555.79
  2820.8 2587.43  2920.4 2638.37  3001.9 2688.24  3166.8 2762.64  3432.9    2891
BR D #Mann= 15
       0      .1   710.6    .035   799.2     .07   986.1     .05  1106.6     .06
  1202.1     .05  1484.5     .07  1606.4     .05  1940.5      .1  2040.1     .07
  2201.5     .08  2290.1     .05  2613.6     .07  2735.5     .06  2773.5      .1
BC Design=,, 0 ,, 0 ,,,,,,
BC Use User HTab Curves=0
BC User HTab FreeFlow(D)= 0

Type RM Length L Ch R = 1 ,31557   ,745.6,681.2,615.6
BEGIN DESCRIPTION:
xs 2
END DESCRIPTION:
XS GIS Cut Line= 5
2293616.03630358512950.9285612962293106.84044778513046.673412553
2291941.81488771513372.5234734162291084.78459064513484.115960013
2290633.95094479514193.844174769
#Sta/Elev= 30
       0  2547.7   117.9 2546.81   235.9 2562.07   345.8 2561.56   466.7 2569.11
     579 2552.13     687 2543.31   710.6 2533.51   799.2 2533.65   832.4 2539.38
   890.5 2534.53   986.1 2534.36  1106.6  2535.5  1202.1 2535.47  1484.5 2535.02
  1606.4  2533.8  1940.5 2534.04  2040.1 2533.04  2201.5  2532.5  2290.1 2532.81
  2524.2 2529.89  2613.6  2533.4    2655 2537.47  2735.5 2533.48  2773.5 2555.79
  2820.8 2587.43  2920.4 2638.37  3001.9 2688.24  3166.8 2762.64  3432.9    2891
#Mann= 15 ,-1,0
       0      .1       0   710.6     .04       0   799.2     .07       0
   986.1     .05       0  1106.6     .06       0  1202.1     .05       0
  1484.5     .07       0  1606.4     .05       0  1940.5      .1       0
  2040.1     .07       0  2201.5     .08       0  2290.1     .05       0
  2613.6     .07       0  2735.5     .06       0  2773.5      .1       0
#XS Ineff= 2 ,-1
       0   664.3  2547.7   887.7    2654    2535
Permanent Ineff=
       F       F
Bank Sta=710.6,799.2
XS Rating Curve= 0 ,0
Exp/Cntr(USF)=0,0
Exp/Cntr=0.5,0.3

Type RM Length L Ch R = 1 ,30875   ,1633.8,1636,1590.4
XS GIS Cut Line= 4
2292526.21496556512244.7205059122292164.95533817 513261.14589824
2291044.43818879513438.7141896712290585.20984888514173.479533523
#Sta/Elev= 30
       0 2609.87    86.5 2605.83   148.9  2599.4   283.8 2573.11   412.3  2561.5
   488.7 2545.55   501.4 2536.93  523.81 2533.61   543.9 2531.78   613.9 2533.92
   813.1 2533.26   863.2 2535.41   947.2 2533.55  1057.7 2535.94  1192.9 2532.41
  1294.2 2534.87  2108.2 2530.48  2156.8 2533.21  2187.6 2529.36  2205.1 2533.45
  2244.2 2532.46  2329.3 2536.89  2390.7 2534.28    2430 2557.54  2470.8 2577.21
    2518 2606.59  2574.6 2634.71  2635.9 2668.94  2801.6 2744.77  3079.7 2876.53
#Mann= 8 ,-1,0
       0      .1       0     290     .12       0     390      .1       0
  523.81     .04       0   613.9      .1       0     710     .05       0
 2283.22     .07       0 2403.22      .1       0
Bank Sta=523.81,613.9
XS Rating Curve= 0 ,0
Exp/Cntr(USF)=0,0
Exp/Cntr=0.3,0.1

Type RM Length L Ch R = 1 ,29239   ,428.3,425.4,426.8
XS GIS Cut Line= 3
2290793.39336298 512385.550530152290928.10034268513555.052035781
2290572.96375982 514136.74126633
#Sta/Elev= 30
       0 2570.94      60 2569.15    96.1 2565.08   120.4 2560.27   160.7 2547.57
   184.8 2543.95   281.5 2537.01   309.7  2530.9   337.8 2528.97     354 2531.05
   378.1  2530.5   390.2 2527.14   406.3 2528.31   478.8 2527.09   487.82529.924
   494.9 2531.05     668    2529   937.8 2529.62   953.9 2528.28   982.1 2531.59
  1143.1 2530.72  1163.3  2536.4  1217.2 2535.81  1264.1  2559.1  1282.8 2562.71
    1330 2591.58  1367.2 2619.39  1443.5 2659.31  1624.9 2742.63  1858.8 2853.38
#Mann= 9 ,-1,0
       0      .1       0     330     .07       0   378.1     .04       0
   487.8     .07       0     530     .05       0    1120     .07       0
 1227.23      .1       0 1437.23     .05       0 1457.23      .1       0
Bank Sta=378.1,487.8
XS Rating Curve= 0 ,0
Exp/Cntr(USF)=0,0
Exp/Cntr=0.3,0.1

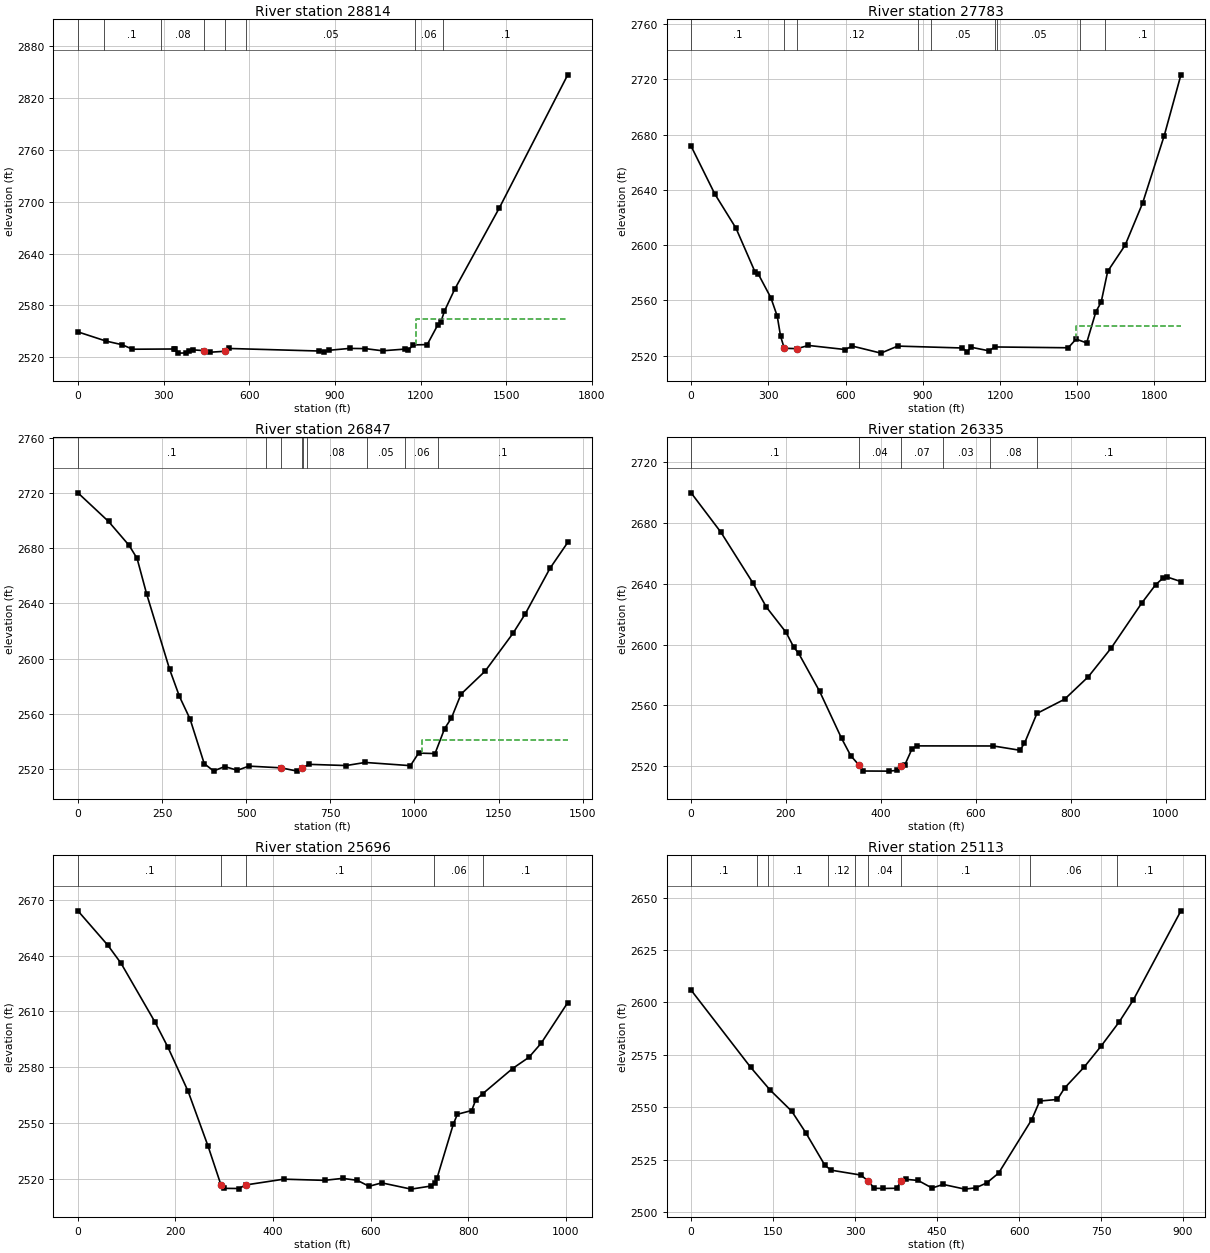
Type RM Length L Ch R = 1 ,28814   ,1036.9,1031.2,1017.1
XS GIS Cut Line= 2
2290385.22369133512426.8529221832290539.52441354 514135.18234663
#Sta/Elev= 30
       0 2549.46    98.7  2538.8     155  2534.6   191.1  2529.4   335.7 2529.66
   339.7 2529.53   351.8 2524.88     379  2525.1   387.8 2527.58     404 2528.62
   443.2 2527.78   464.2 2525.95   516.4 2527.07   528.5 2530.27   845.8 2527.31
   861.8 2525.87   877.9 2528.12   951.5 2530.34  1006.4 2530.09  1066.7 2527.59
    1147 2529.59    1155    2528  1175.1 2534.34  1223.3 2534.79  1259.4 2557.02
  1271.5 2561.44  1283.5 2573.46  1319.4 2598.75  1476.3 2693.21  1715.3 2846.86
#Mann= 8 ,-1,0
       0     .12       0      90      .1       0     290     .08       0
   443.2     .04       0   516.4     .08       0     590     .05       0
    1180     .06       0    1280      .1       0
#XS Ineff= 2 , 0
                         1184.05         2564.23
Permanent Ineff=
       F       F
Bank Sta=443.2,516.4
XS Rating Curve= 0 ,0
Exp/Cntr(USF)=0,0
Exp/Cntr=0.3,0.1

Type RM Length L Ch R = 1 ,27783   ,954.4,936.3,905.4
XS GIS Cut Line= 3
2289360.22603666512300.1059003692289938.85374494513694.323140321
 2289977.4289255 514085.58568592
#Sta/Elev= 30
       0 2671.67    92.1 2637.01   174.4  2612.2   248.7 2580.38   260.9 2579.05
   309.9 2561.82   334.6 2548.51   347.6 2533.94   361.9 2525.22   411.3 2524.97
   455.9 2527.28   598.8 2524.32     626 2526.84   737.4 2521.72   802.4 2526.82
  1053.6 2525.44    1072 2522.71  1088.2 2525.97  1157.5 2523.37  1179.1 2526.19
    1465  2525.6  1495.3 2531.88  1536.5 2529.12  1572.7 2551.86  1592.8  2558.6
  1618.2 2580.95  1686.1 2599.96  1753.6 2630.25    1838 2679.35  1902.7 2723.32
#Mann= 9 ,-1,0
       0      .1       0   361.9     .04       0   411.3     .12       0
     880     .07       0     930     .05       0    1180     .07       0
    1190     .05       0 1509.52     .06       0 1609.52      .1       0
#XS Ineff= 2 , 0
                         1495.02         2541.24
Permanent Ineff=
       F       F
Bank Sta=361.9,411.3
XS Rating Curve= 0 ,0
Exp/Cntr(USF)=0,0
Exp/Cntr=0.3,0.1

Type RM Length L Ch R = 1 ,26847   ,462.2,511.4,535.3
XS GIS Cut Line= 3
2288654.85130657513143.2491324352289403.09487152513607.710218757
2289505.15850074514173.206453174
#Sta/Elev= 30
       0 2720.21      91 2699.45   152.2 2682.06   175.8 2672.66     204 2647.05
   272.5 2592.21   301.6 2572.61   333.3 2556.13   375.3 2523.86   403.2 2518.52
     436 2521.73   473.9 2519.04   507.8 2522.05   604.2  2520.8   651.3 2518.42
   667.12520.782   686.3 2523.34   797.2 2522.47   853.5 2524.71   987.9 2522.39
  1012.2 2531.49    1061 2531.14  1089.4 2549.21  1109.8 2556.94  1138.2 2574.24
    1210 2590.95  1292.7 2618.36  1329.3 2632.53  1402.4 2665.41  1455.3 2684.26
#Mann= 9 ,-1,0
       0      .1       0     560     .08       0   604.2     .04       0
   667.1     .08       0     670      .1       0     680     .08       0
     860     .05       0  970.68     .06       0 1070.68      .1       0
#XS Ineff= 2 , 0
                         1023.26         2540.72
Permanent Ineff=
       F       F
Bank Sta=604.2,667.1
XS Rating Curve= 0 ,0
Exp/Cntr(USF)=0,0
Exp/Cntr=0.3,0.1

Type RM Length L Ch R = 1 ,26335   ,601.5,639.1,671.7
XS GIS Cut Line= 2
2288643.82982641513192.8457931452288930.38831051 514184.77900734
#Sta/Elev= 30
       0 2699.88    62.8 2673.94   129.8 2640.76   158.8 2624.58   200.2 2607.99
   216.6 2598.12   226.7 2594.23     271 2569.12   317.1 2538.26   336.5  2526.8
   354.3 2520.46   362.6 2516.71   416.7 2516.63   433.4 2517.09   443.1 2520.11
     450 2520.37   465.7 2531.31   475.4 2533.25   637.4 2533.19     693 2530.37
   702.6 2534.87     729 2554.62   787.3 2563.97   837.3 2578.79   885.7 2597.78
   949.6 2627.16   979.3 2639.41   995.4  2643.9  1003.8  2644.4  1032.5 2641.45
#Mann= 6 ,-1,0
       0      .1       0   354.3     .04       0   443.1     .07       0
     530     .03       0     630     .08       0     730      .1       0
Bank Sta=354.3,443.1
XS Rating Curve= 0 ,0
Exp/Cntr(USF)=0,0
Exp/Cntr=0.3,0.1

Type RM Length L Ch R = 1 ,25696   ,545.4,583.6,608.1
XS GIS Cut Line= 2
2288280.12098121513198.3565332242287982.54101695514157.225306945
#Sta/Elev= 30
       0 2664.08    61.6 2645.49    88.5 2635.83   157.9 2604.29   184.4 2590.77
     226 2566.92   266.8 2537.49   293.1 2516.76   300.3 2514.81   329.6 2514.73
   344.52516.667   421.8 2519.75   505.5 2519.12   542.4 2520.18   572.6 2519.14
   596.7 2515.92   622.8 2517.77     683  2514.4   723.3 2516.05   731.7 2517.63
   735.9 2520.16   769.3 2549.19   777.8 2554.67   807.1 2556.67   815.5 2562.43
     830 2565.77   890.8 2579.24   924.4 2585.28   949.5 2592.86    1004  2614.7
#Mann= 5 ,-1,0
       0      .1       0   293.1     .04       0   344.5      .1       0
     730     .06       0     830      .1       0
Bank Sta=293.1,344.5
XS Rating Curve= 0 ,0
Exp/Cntr(USF)=0,0
Exp/Cntr=0.3,0.1

Type RM Length L Ch R = 1 ,25113   ,570.5,590.4,600.1
XS GIS Cut Line= 2
2287938.45509632 513121.206172122287227.56962615513666.769439927
#Sta/Elev= 30
       0 2605.84   108.8 2569.07   144.2 2558.28   184.2 2548.04   209.9 2537.78
   244.9 2522.23   256.2 2519.96   310.4 2517.64     324  2514.8     335 2511.33
   350.8 2511.24     376 2511.33   384.62514.751   392.4 2515.61   415.3 2515.06
   440.9 2511.43   460.9 2513.17   500.8 2510.92   520.8 2511.55   540.8 2513.87
   562.6 2518.57   623.1 2544.05   637.8 2552.93   670.1  2553.7   683.4 2559.18
   718.9 2569.08   749.7 2579.01   783.3 2590.72     809 2601.16   896.1 2643.66
#Mann= 9 ,-1,0
       0      .1       0     120     .12       0     140      .1       0
     250     .12       0     300      .1       0     324     .04       0
   384.6      .1       0     620     .06       0     780      .1       0
Bank Sta=324,384.6
XS Rating Curve= 0 ,0
Exp/Cntr(USF)=0,0
Exp/Cntr=0.3,0.1

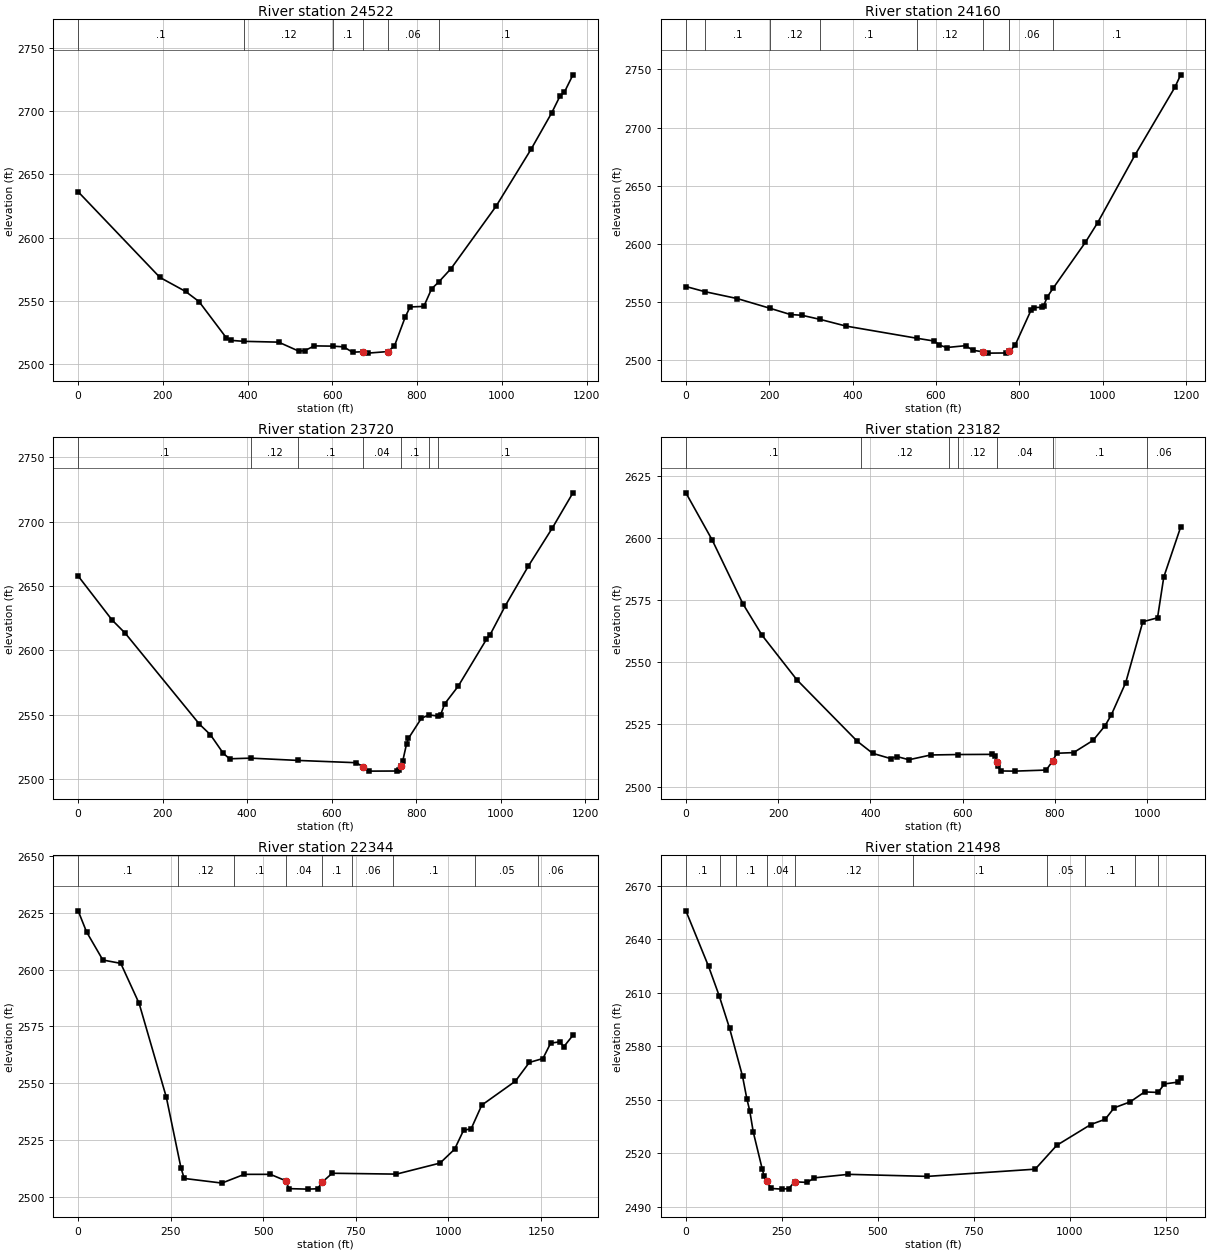
Type RM Length L Ch R = 1 ,24522   ,361.7,362.3,363.8
XS GIS Cut Line= 2
 2287787.4986742512706.4314782652286774.86968374513288.403486634
#Sta/Elev= 30
       0 2636.24     193 2568.52   253.5 2557.43   285.3 2549.42   349.8 2520.73
   361.9  2518.7   390.8 2517.97   473.2 2517.33   520.5 2510.26   534.4 2510.53
   557.5 2514.37   602.1 2514.16   626.7  2513.6   647.7 2509.36   672.8 2509.79
   684.2 2508.64     731 2509.88   746.6 2514.27     772 2537.09   783.5 2545.16
     816 2545.59   834.3 2559.47   851.1 2564.88   880.3 2575.52   986.5 2624.79
  1069.6 2670.14  1117.8 2698.63  1137.4 2711.92    1148 2715.18    1168 2728.74
#Mann= 6 ,-1,0
       0      .1       0   390.8     .12       0   602.1      .1       0
   672.8     .04       0     731     .06       0   851.1      .1       0
Bank Sta=672.8,731
XS Rating Curve= 0 ,0
Exp/Cntr(USF)=0,0
Exp/Cntr=0.3,0.1

Type RM Length L Ch R = 1 ,24160   ,439,439.8,441.9
XS GIS Cut Line= 2
2287624.12303623512399.5928003942286583.83315653512971.355177021
#Sta/Elev= 30
       0  2563.5    45.6 2559.07   123.2 2553.15   201.4 2544.85     251 2539.44
   278.4 2538.81   322.2 2535.26     384 2529.54   554.9 2519.04   596.1 2516.66
   607.9 2513.26   625.6 2511.12   670.9  2512.7   689.2  2508.7     712 2507.54
   725.7 2506.31     767 2506.44   775.8 2507.71   789.6 2512.86   828.8 2543.76
   835.2 2545.44   855.3 2545.67   858.3 2546.98   867.1 2554.57   881.8 2562.43
   958.5 2601.46   987.9 2618.29  1077.1 2676.14    1173 2734.42  1187.1 2745.24
#Mann= 8 ,-1,0
       0     .12       0    45.6      .1       0   201.4     .12       0
   322.2      .1       0   554.9     .12       0     712     .04       0
   775.8     .06       0   881.8      .1       0
Bank Sta=712,775.8
XS Rating Curve= 0 ,0
Exp/Cntr(USF)=0,0
Exp/Cntr=0.3,0.1

Type RM Length L Ch R = 1 ,23720   ,539.7,538,536.6
XS GIS Cut Line= 2
2287411.54316868512038.3121084662286370.01329378512572.853896115
#Sta/Elev= 30
       0 2657.79    80.2 2623.58   111.4 2613.27     287 2542.52   312.9 2534.32
   343.3  2519.9   358.2  2515.6   408.4  2516.1   520.8 2514.31   658.3 2512.54
   673.7 2509.34   687.2    2506   754.6 2506.09   759.3 2506.78   763.6 2509.83
   768.1 2514.04   777.1 2527.32   781.6 2531.52   812.2 2547.17   830.6  2549.7
   850.9 2548.88   857.4 2549.55     867 2558.24     899 2571.96   965.9 2608.45
   974.9 2612.23  1010.9  2634.8  1065.3 2665.57  1121.8 2695.05  1170.7  2722.5
#Mann= 7 ,-1,0
       0      .1       0   408.4     .12       0   520.8      .1       0
   673.7     .04       0   763.6      .1       0   830.6     .06       0
   850.9      .1       0
Bank Sta=673.7,763.6
XS Rating Curve= 0 ,0
Exp/Cntr(USF)=0,0
Exp/Cntr=0.3,0.1

Type RM Length L Ch R = 1 ,23182   ,830.9,838.4,839.6
XS GIS Cut Line= 2
 2287154.4378979511546.1689280022286212.10134442512058.667755336
#Sta/Elev= 30
       0 2618.22      57 2599.24   123.5 2573.58   165.4 2560.81   240.7 2542.94
   371.4 2518.24     405 2513.35   444.2 2511.23   457.9 2512.05   483.5 2510.77
   530.8 2512.69     590 2512.87   664.5 2512.94   670.4 2512.25  675.34 2509.95
   676.5 2508.29   682.2 2506.26   712.9 2506.19   781.2 2506.62   794.9 2510.21
     804 2513.39   840.4 2513.64   882.8 2518.57   908.7 2524.46   922.3 2528.82
   953.6 2541.85   990.6 2566.31  1022.5 2567.91  1036.1 2584.34  1072.7 2604.45
#Mann= 7 ,-1,0
       0      .1       0     380     .12       0     570      .1       0
     590     .12       0  675.34     .04       0   794.9      .1       0
    1000     .06       0
Bank Sta=675.34,794.9
XS Rating Curve= 0 ,0
Exp/Cntr(USF)=0,0
Exp/Cntr=0.3,0.1

Type RM Length L Ch R = 1 ,22344   ,884.3,846.1,817.1
XS GIS Cut Line= 3
2286648.94191787510927.9316207332285690.07314414511363.280086963
 2285519.2402017511589.220430196
#Sta/Elev= 30
       0    2626    22.7  2616.7    66.7 2604.31   115.1 2602.83   164.7 2585.14
   238.1 2543.81   277.6  2512.7   286.4 2507.97   388.2 2505.93   448.7 2509.78
   519.2 2509.78   560.5 2506.96   569.5 2503.47   620.3 2503.26   646.6 2503.42
   659.22506.368   686.1 2510.26   859.6 2509.88   977.4 2514.75  1016.7 2520.87
  1040.8 2529.18  1061.5 2529.91    1090  2540.3  1180.8 2550.86  1218.5 2559.13
  1255.2 2560.86  1276.1 2567.64  1301.2 2568.23  1311.2 2565.99  1336.3 2571.11
#Mann= 9 ,-1,0
       0      .1       0     270     .12       0     420      .1       0
   560.5     .04       0   659.2      .1       0     740     .06       0
     850      .1       0 1073.07     .05       0 1243.07     .06       0
Bank Sta=560.5,659.2
XS Rating Curve= 0 ,0
Exp/Cntr(USF)=0,0
Exp/Cntr=0.3,0.1

Type RM Length L Ch R = 1 ,21498   ,420.7,418.9,419.9
XS GIS Cut Line= 2
2285822.33090604510239.0891108762285155.53135649511341.237126648
#Sta/Elev= 30
       0 2655.91      59 2624.78    86.6 2608.33   113.8 2590.01   147.4 2563.22
   158.7 2550.53   166.1 2543.92   175.4 2531.89   198.8 2511.07   203.5 2507.23
   209.9 2504.56   222.2 2500.21   250.7 2499.85   268.2 2500.19     2832503.971
   315.7 2503.61   334.4 2506.17   423.2 2508.14   628.9    2507   909.4 2511.04
   965.5  2524.4  1054.3 2536.09  1091.7 2539.03  1115.1 2545.45  1156.6 2548.77
  1194.4 2554.36  1229.4 2554.07    1246 2558.86  1281.8 2559.86  1288.2 2562.25
#Mann= 10 ,-1,0
       0      .1       0      90     .12       0     130      .1       0
   209.9     .04       0     283     .12       0     590      .1       0
     940     .05       0    1040      .1       0    1170     .07       0
    1230     .06       0
Bank Sta=209.9,283
XS Rating Curve= 0 ,0
Exp/Cntr(USF)=0,0
Exp/Cntr=0.3,0.1