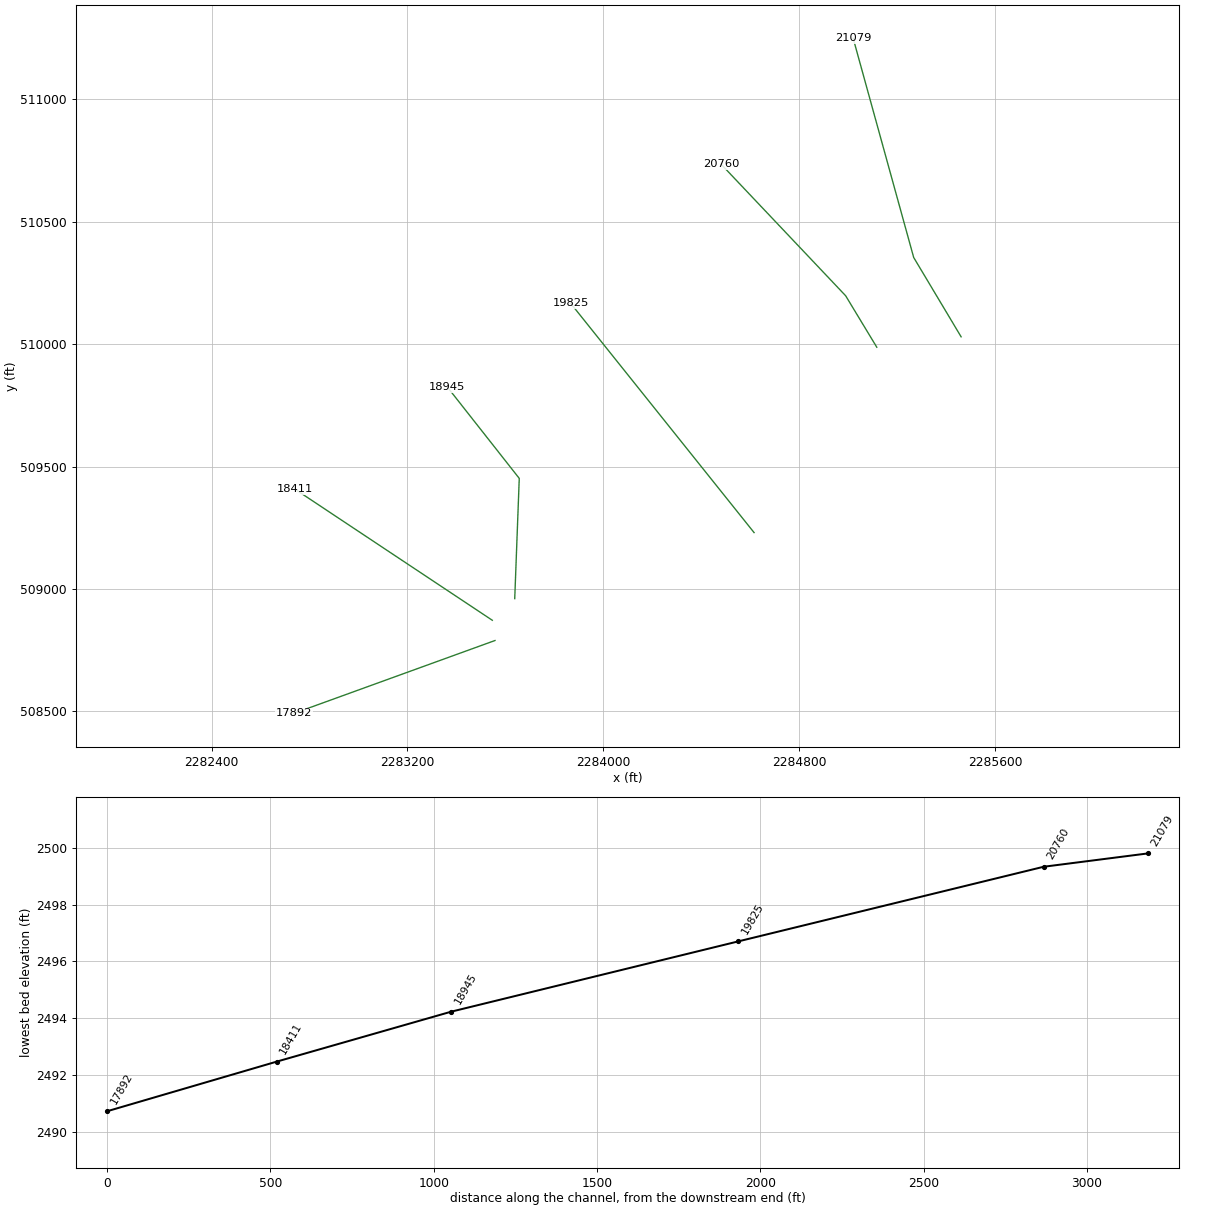
HEC-RAS study DEERCK.prj: DEERCK

--- DEERCK.g01 (geometry) --- (continued)

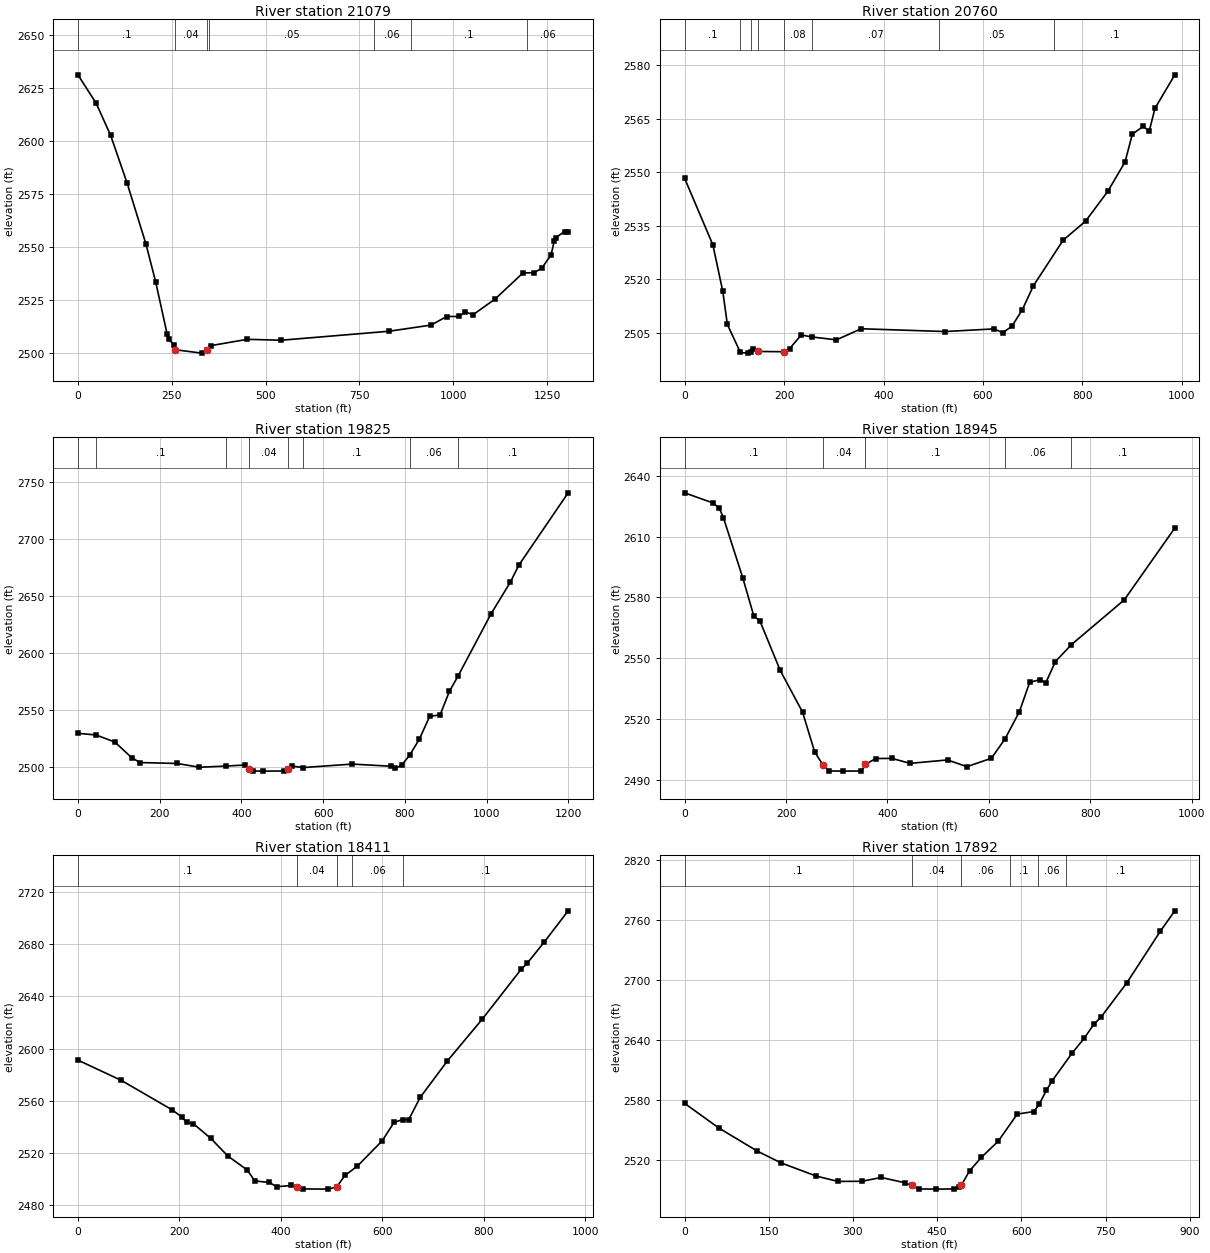
Type RM Length L Ch R = 1 ,21079   ,319.8,319,318.7
XS GIS Cut Line= 3
2285461.14041315510030.1368808472285267.42861203510354.103168921
2285020.27907268511249.185284426
#Sta/Elev= 30
       0 2631.07    48.6 2617.65    87.2  2602.5   131.3 2579.87   181.2 2551.27
   207.1 2533.43   237.8 2508.69   242.1 2506.35   255.2 2503.72   259.1 2501.41
   329.8 2499.81   343.8 2501.09   355.8  2503.4   451.2 2506.32   541.9  2505.9
   828.8 2510.13   940.9 2513.04   982.4 2517.08  1015.6  2517.1  1032.2 2519.27
  1052.5 2517.91    1111 2525.25  1185.7 2537.63  1215.1 2537.75  1235.5 2539.81
  1260.4 2546.08  1268.7 2552.48  1272.8 2554.22  1296.4 2557.17    1306 2557.04
#Mann= 7 ,-1,0
       0      .1       0   259.1     .04       0   343.8      .1       0
     350     .05       0  787.46     .06       0  887.46      .1       0
 1197.46     .06       0
Bank Sta=259.1,343.8
XS Rating Curve= 0 ,0
Exp/Cntr(USF)=0,0
Exp/Cntr=0.3,0.1

Type RM Length L Ch R = 1 ,20760   ,931.5,934.7,937.4
XS GIS Cut Line= 3
2285116.71524019509987.594775123 2284989.4301551510197.948894406
2284480.76139073510735.165234228
#Sta/Elev= 30
       0 2548.33    56.9 2529.66    76.7  2516.7      86 2507.38   112.2 2499.52
   126.8 2499.34   132.8 2499.56   138.4 2500.56   147.2 2499.81   199.6 2499.73
   211.3 2500.62   234.6 2504.43   255.8 2503.87   305.4 2503.06     355 2506.17
   523.5 2505.39   622.5 2506.13   639.5 2505.07     658 2506.83   679.1 2511.52
   701.5 2518.25   761.2 2530.99   806.2 2536.31   850.8 2544.64   885.7 2552.92
   900.3  2560.7   922.5 2562.91   934.2  2561.5   945.8 2567.94   985.7 2577.32
#Mann= 8 ,-1,0
       0      .1       0   112.2     .04       0   132.8     .08       0
   147.2     .04       0   199.6     .08       0   255.8     .07       0
   512.5     .05       0   742.7      .1       0
Bank Sta=147.2,199.6
XS Rating Curve= 0 ,0
Exp/Cntr(USF)=0,0
Exp/Cntr=0.3,0.1

Type RM Length L Ch R = 1 ,19825   ,890.8,879.6,784.9
XS GIS Cut Line= 2
2284615.47882877509230.6236764442283866.01817804510167.449489851
#Sta/Elev= 30
       0 2529.79    44.3 2528.39    90.4 2522.17   132.2  2508.3   152.2 2504.21
   242.2 2503.44   297.3 2500.12   361.8 2501.12   408.7 2502.08   419.7 2499.01
   428.2 2496.82   453.5 2496.71     505 2496.82   513.6  2498.6     525 2501.02
   551.4 2499.84   671.2 2502.88   766.5 2500.98   776.8 2499.02   792.5 2502.04
   812.1 2510.81   835.2 2524.43   860.8 2544.65   886.4 2545.98   909.1 2566.55
   930.4 2580.04  1010.6 2634.18  1058.5 2662.34    1079 2677.07  1199.7 2740.43
#Mann= 8 ,-1,0
       0     .12       0    44.3      .1       0   361.8     .07       0
   419.7     .04       0   513.6     .07       0   551.4      .1       0
   812.1     .06       0   930.4      .1       0
Bank Sta=419.7,513.6
XS Rating Curve= 0 ,0
Exp/Cntr(USF)=0,0
Exp/Cntr=0.3,0.1

Type RM Length L Ch R = 1 ,18945   ,470.5,534,593.3
XS GIS Cut Line= 3
2283638.00899794508960.741594996  2283656.475801509451.938141929
2283362.52227706509825.351057716
#Sta/Elev= 30
       0 2631.64    56.5 2626.58    68.5    2624    76.5 2619.41   114.7 2589.69
   136.5 2570.84   148.5 2568.39   188.6 2543.94   232.6 2523.38   256.6 2503.63
     273 2497.27   284.6 2494.32   312.7 2494.23   348.7 2494.31   356.7 2497.54
   376.7 2500.44   408.7 2500.52   444.8 2498.06   518.6 2499.76   556.7 2496.42
   605.1 2500.59   632.2 2510.25   660.2 2523.52   680.6 2538.12   701.8 2539.41
     712 2537.67   731.3 2548.32   762.9 2556.69   867.1 2578.78   966.8 2614.25
#Mann= 5 ,-1,0
       0      .1       0     273     .04       0   356.7      .1       0
   632.2     .06       0   762.9      .1       0
Bank Sta=273,356.7
XS Rating Curve= 0 ,0
Exp/Cntr(USF)=0,0
Exp/Cntr=0.3,0.1

Type RM Length L Ch R = 1 ,18411   ,456.2,519.4,570
XS GIS Cut Line= 2
2283546.39525347508872.4255713182282741.82720195509406.967358968
#Sta/Elev= 30
       0 2591.22    85.8 2575.63   185.2 2553.25   204.4 2547.79     214 2543.58
   227.2 2542.66     262 2531.24   295.6 2517.75   333.9 2507.04   348.4 2498.77
   377.3 2497.55   391.7 2494.31   420.5 2495.25   432.1 2494.35   443.6 2492.64
   492.7 2492.47     510 2494.11   526.1 2502.93   550.4 2509.99   599.4 2529.38
     623 2543.54   639.8 2545.74   651.9 2545.67   674.4 2562.64   727.8 2590.47
   796.5 2622.43   873.5 2660.77   885.1 2665.22   919.4  2681.8     966 2705.48
#Mann= 5 ,-1,0
       0      .1       0   432.1     .04       0     510      .1       0
     540     .06       0     640      .1       0
Bank Sta=432.1,510
XS Rating Curve= 0 ,0
Exp/Cntr(USF)=0,0
Exp/Cntr=0.3,0.1

Type RM Length L Ch R = 1 ,17892   ,267,268.8,270
XS GIS Cut Line= 2
2283557.41673363508789.7644701362282736.31646188508492.184505877
#Sta/Elev= 30
       0 2576.48    60.8 2551.92     129  2528.9   171.5 2517.02   234.6 2503.78
   273.1 2498.43   316.2 2498.56   350.2 2502.39   392.7 2497.07   404.3 2494.41
   416.8 2490.91     448 2490.72   479.2 2490.91   488.6 2492.49  493.15 2494.66
   507.6 2508.87   528.9 2522.55   558.7 2538.59   592.7 2565.77   622.5 2568.31
   632.2 2576.04   644.7 2589.63     655 2599.14   690.6 2626.85   711.8 2641.41
     729 2655.46   741.8  2662.6   788.3 2697.31   847.7 2748.66   873.4 2768.99
#Mann= 6 ,-1,0
       0      .1       0   404.3     .04       0  493.15     .06       0
     580      .1       0     630     .06       0     680      .1       0
Bank Sta=404.3,493.15
XS Rating Curve= 0 ,0
Exp/Cntr(USF)=0,0
Exp/Cntr=0.3,0.1