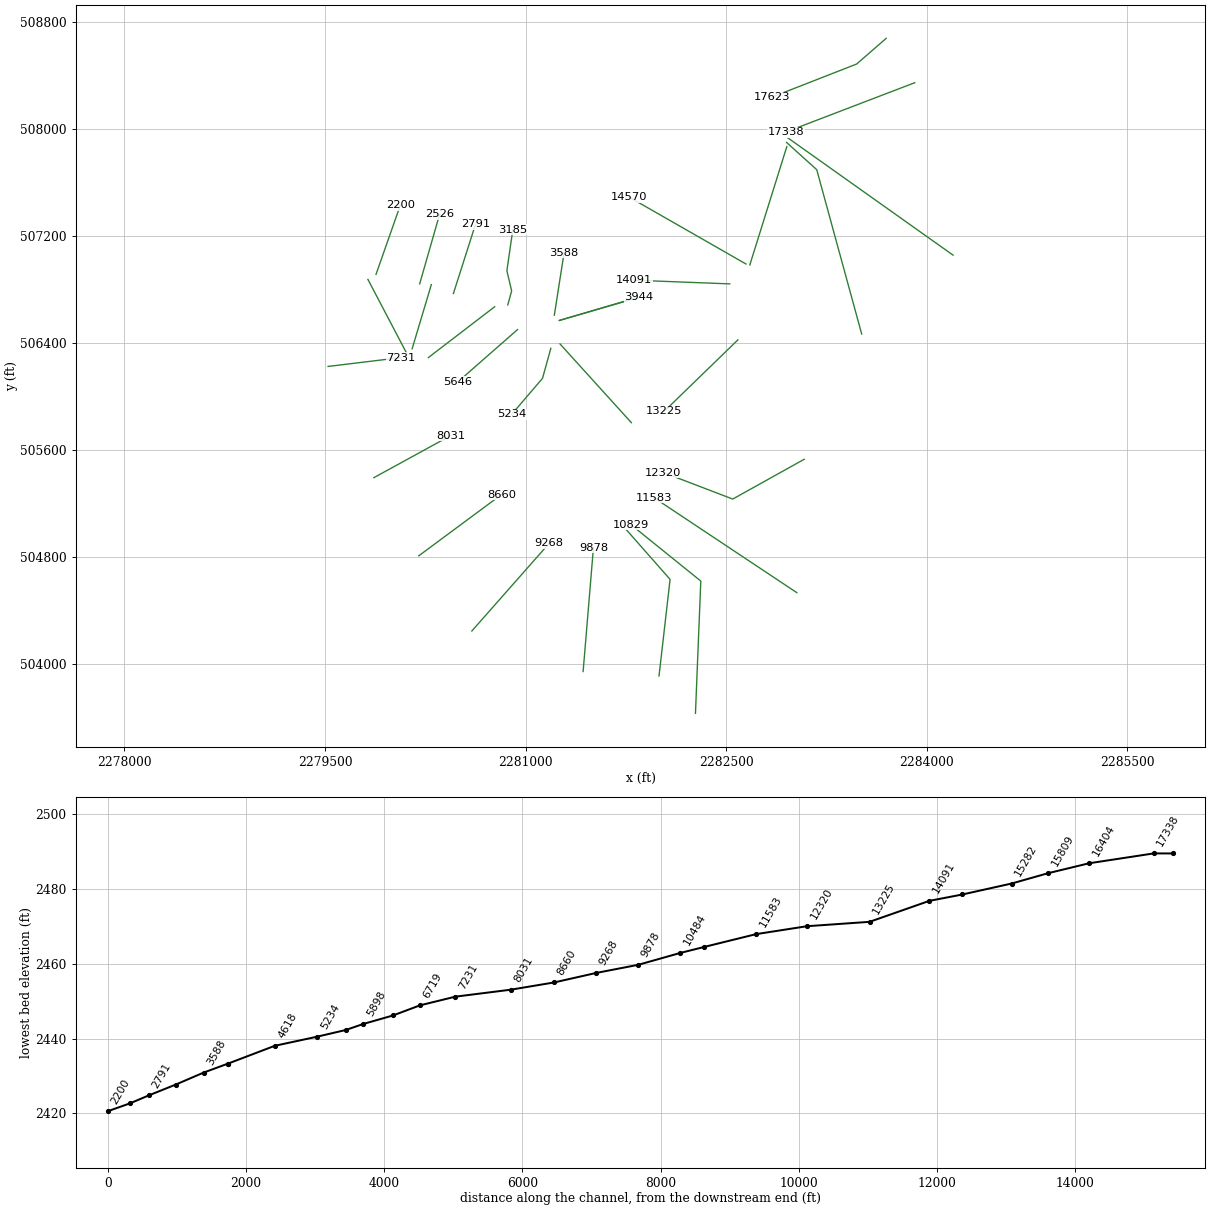
HEC-RAS study DEERCK.prj: DEERCK

--- DEERCK.g01 (geometry) --- (continued)

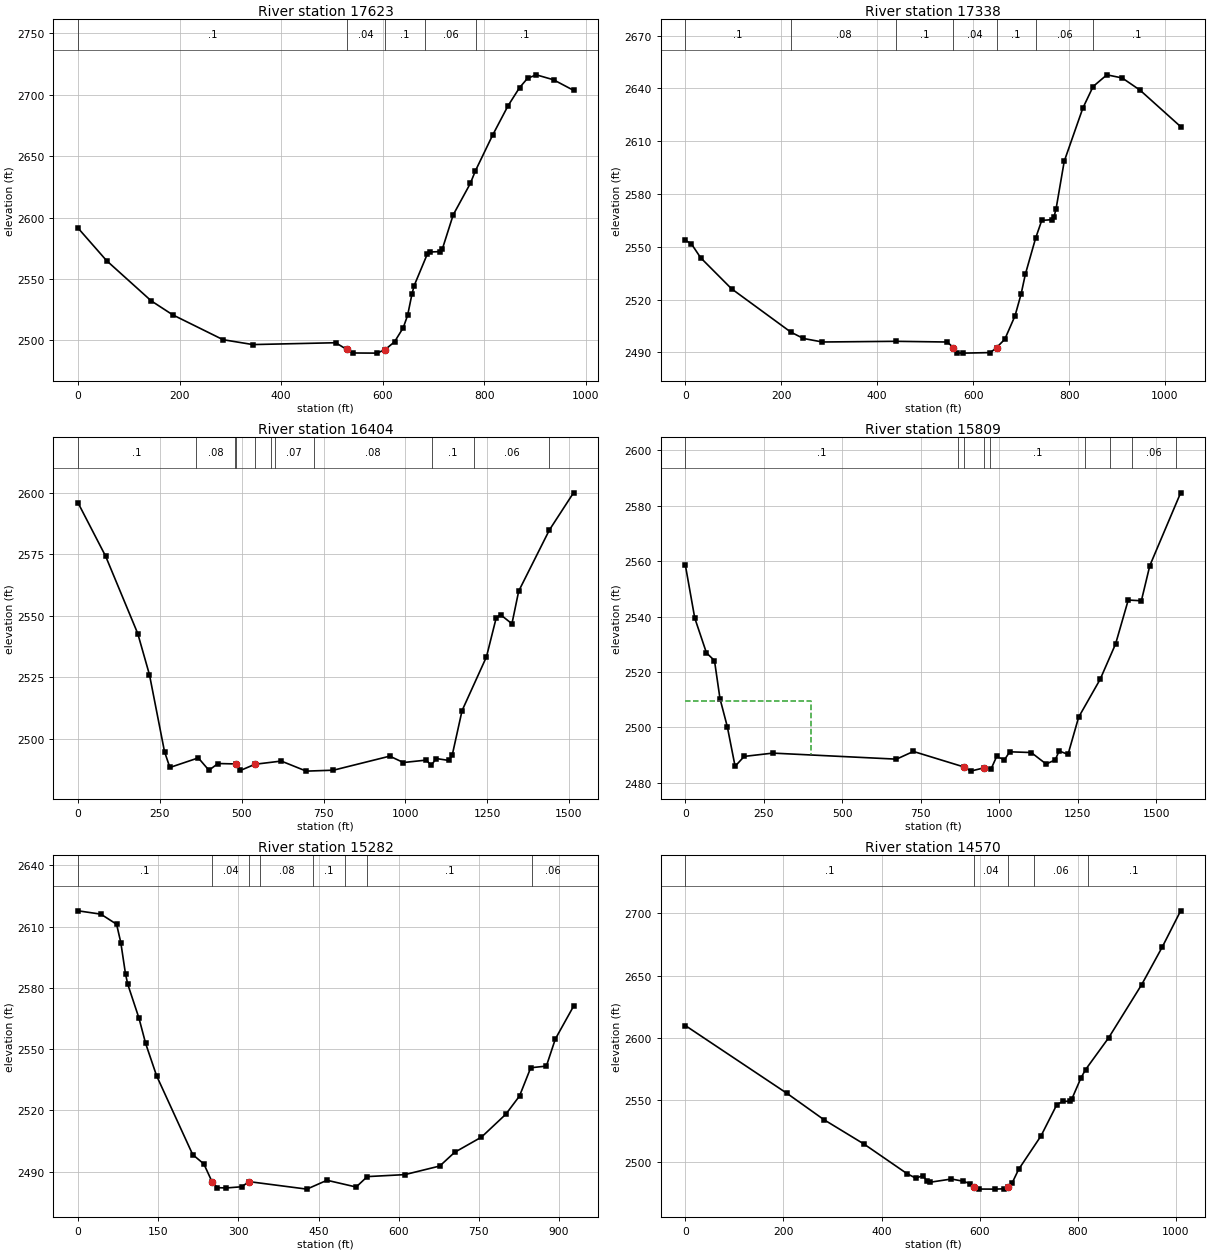
Type RM Length L Ch R = 1 ,17623   ,285.2,284.6,284.3
XS GIS Cut Line= 3
2283696.83398705508675.2023516642283475.27110473 508482.85655273
2282839.79954117 508234.51134398
#Sta/Elev= 30
       0 2591.26    55.8 2564.93   143.9 2532.08   186.1 2520.73   285.4 2500.44
     344 2496.47   507.2 2497.97   528.7 2492.59   541.5 2489.62   588.8  2489.5
   604.72492.406   623.1 2498.68   640.3  2510.2   648.9 2520.28   657.5 2537.67
   661.8 2544.47   687.5 2570.02   692.3 2571.89   713.3 2572.25   717.6 2574.68
   738.7 2602.15   772.6  2627.9   782.3 2637.92   816.4 2667.16   846.7 2691.03
   869.4 2705.84   885.1 2713.44   902.4 2716.29   936.3 2712.26   975.7 2703.67
#Mann= 5 ,-1,0
       0      .1       0   528.7     .04       0   604.7      .1       0
  683.41     .06       0  783.41      .1       0
Bank Sta=528.7,604.7
XS Rating Curve= 0 ,0
Exp/Cntr(USF)=0,0
Exp/Cntr=0.3,0.1

Type RM Length L Ch R = 1 ,17338   ,971.2,934.2,886.9
XS GIS Cut Line= 2
2283910.10409867508343.3945237482282945.72458487507974.174938464
#Sta/Elev= 30
       0 2553.71    12.5 2551.71      32 2543.73    96.3 2526.12     220 2501.45
   246.2 2497.84   285.9 2495.84   438.9 2496.23     546 2495.83   558.9 2492.65
   567.4 2489.64   579.3 2489.51     636 2489.82   648.8 2492.66     666 2497.39
   687.4 2510.78   700.1 2523.23   708.8 2534.31   730.2 2554.83     743 2564.98
   764.5 2565.42   768.7 2567.09     773 2571.72   789.9 2598.61   828.7 2628.84
   850.1 2641.12   878.8 2647.77   910.7 2645.99   947.9 2639.06  1032.6  2618.3
#Mann= 7 ,-1,0
       0      .1       0     220     .08       0   438.9      .1       0
   558.9     .04       0   648.8      .1       0   730.2     .06       0
   850.1      .1       0
Bank Sta=558.9,648.8
XS Rating Curve= 0 ,0
Exp/Cntr(USF)=0,0
Exp/Cntr=0.3,0.1

Type RM Length L Ch R = 1 ,16404   ,619.7,595,557.6
XS GIS Cut Line= 2
2284196.66258277507053.8813452952282962.25680511507930.089017833
#Sta/Elev= 30
       0 2595.85      84 2574.23   182.1  2542.8   217.9 2526.05   263.8 2494.83
   280.2 2488.36   367.1 2492.26   399.6 2487.23   427.3 2489.97   482.5  2489.8
     496 2487.16   540.2 2489.67   620.7 2490.97   697.1 2486.88   780.2 2487.26
   952.2 2492.97   993.9 2490.38  1064.2 2491.37  1078.5  2489.2  1094.5 2491.99
  1133.1 2491.22  1143.5  2493.6  1173.2 2511.48  1247.8 2533.36  1277.2 2549.02
  1290.7  2550.5  1325.6  2546.8  1346.3 2560.08    1440 2584.91  1513.8 2600.04
#Mann= 11 ,-1,0
       0      .1       0     360     .08       0     480     .07       0
   482.5     .04       0   540.2     .07       0     590     .08       0
     600     .07       0     720     .08       0    1080      .1       0
    1210     .06       0    1440      .1       0
Bank Sta=482.5,540.2
XS Rating Curve= 0 ,0
Exp/Cntr(USF)=0,0
Exp/Cntr=0.3,0.1

Type RM Length L Ch R = 1 ,15809   ,556.6,527.4,494.7
XS GIS Cut Line= 3
2283513.33081299506464.2321568572283177.17566818507693.127194442
2282951.23532495 507897.02457736
#Sta/Elev= 30
       0  2558.6      30 2539.49    67.3 2526.89    92.9  2524.1   110.5 2510.34
   133.7  2500.3   158.6 2485.96   187.6 2489.53   278.8 2490.72   672.8 2488.54
   726.7 2491.32   887.4 2485.74   909.2 2484.22   950.6 2485.37   974.6 2485.07
   992.1 2489.51    1017 2488.33  1033.9 2491.19  1102.3 2490.93  1149.7 2486.78
  1178.7 2488.27  1191.2  2491.5  1219.5 2490.25  1253.4  2503.7  1321.9 2517.34
  1371.1 2530.12  1411.4 2545.95  1453.2 2545.68  1480.1 2558.34  1578.4 2584.63
#Mann= 9 ,-1,0
       0      .1       0     870     .08       0   887.4     .04       0
   950.6     .08       0     970      .1       0 1274.04     .06       0
 1354.04      .1       0 1424.04     .06       0 1564.04      .1       0
#XS Ineff= 2 , 0
          400.84 2509.41
Permanent Ineff=
       F       F
Bank Sta=887.4,950.6
XS Rating Curve= 0 ,0
Exp/Cntr(USF)=0,0
Exp/Cntr=0.3,0.1

Type RM Length L Ch R = 1 ,15282   ,636.4,712,782.3
XS GIS Cut Line= 2
2282676.80046902506980.5885022472282953.43962099 507865.61335891
#Sta/Elev= 30
       0 2617.68    42.5 2616.05    71.9 2611.11    79.8 2602.12    88.6 2586.77
    92.8 2581.74   113.8 2565.14   126.3 2552.75   146.8 2536.94   214.4 2498.36
   235.3 2493.77  250.47 2485.14   260.5 2482.18   277.2 2482.03   306.6 2482.63
   319.42485.147   428.1 2481.46   465.8  2485.8   520.4 2482.49   541.2 2487.59
   611.5 2488.56   676.9 2492.77   704.7 2499.46     755 2506.92   800.5 2518.09
   826.2 2527.03   847.2 2540.87   876.5 2541.68   893.3 2554.95   927.3 2570.94
#Mann= 8 ,-1,0
       0      .1       0  250.47     .04       0   319.4      .1       0
     340     .08       0     440      .1       0     500     .08       0
     540      .1       0     850     .06       0
Bank Sta=250.47,319.4
XS Rating Curve= 0 ,0
Exp/Cntr(USF)=0,0
Exp/Cntr=0.3,0.1

Type RM Length L Ch R = 1 ,14570   ,453,479.3,504
XS GIS Cut Line= 2
2282648.14462061506987.7524643482281771.93694807507489.229811525
#Sta/Elev= 30
       0 2609.93   207.4  2555.4   282.4 2534.34   364.1 2514.76   451.6 2491.03
     470 2487.28   483.9  2489.4   493.1 2484.87   497.7 2483.99   542.4 2486.66
   566.6 2484.84   580.7 2482.87   588.8 2480.44   598.8  2478.6   631.4 2478.53
   649.8  2478.8   657.6 2480.31   666.4 2483.69   679.3 2494.34     725 2521.29
   757.3 2546.46     769 2548.93   783.7 2549.13   788.1 2551.18   806.5 2567.94
   815.7 2574.48   862.8 2600.05   930.2 2642.82   972.4 2673.21  1009.6 2702.06
#Mann= 5 ,-1,0
       0      .1       0   588.8     .04       0   657.6      .1       0
     710     .06       0     820      .1       0
Bank Sta=588.8,657.6
XS Rating Curve= 0 ,0
Exp/Cntr(USF)=0,0
Exp/Cntr=0.3,0.1

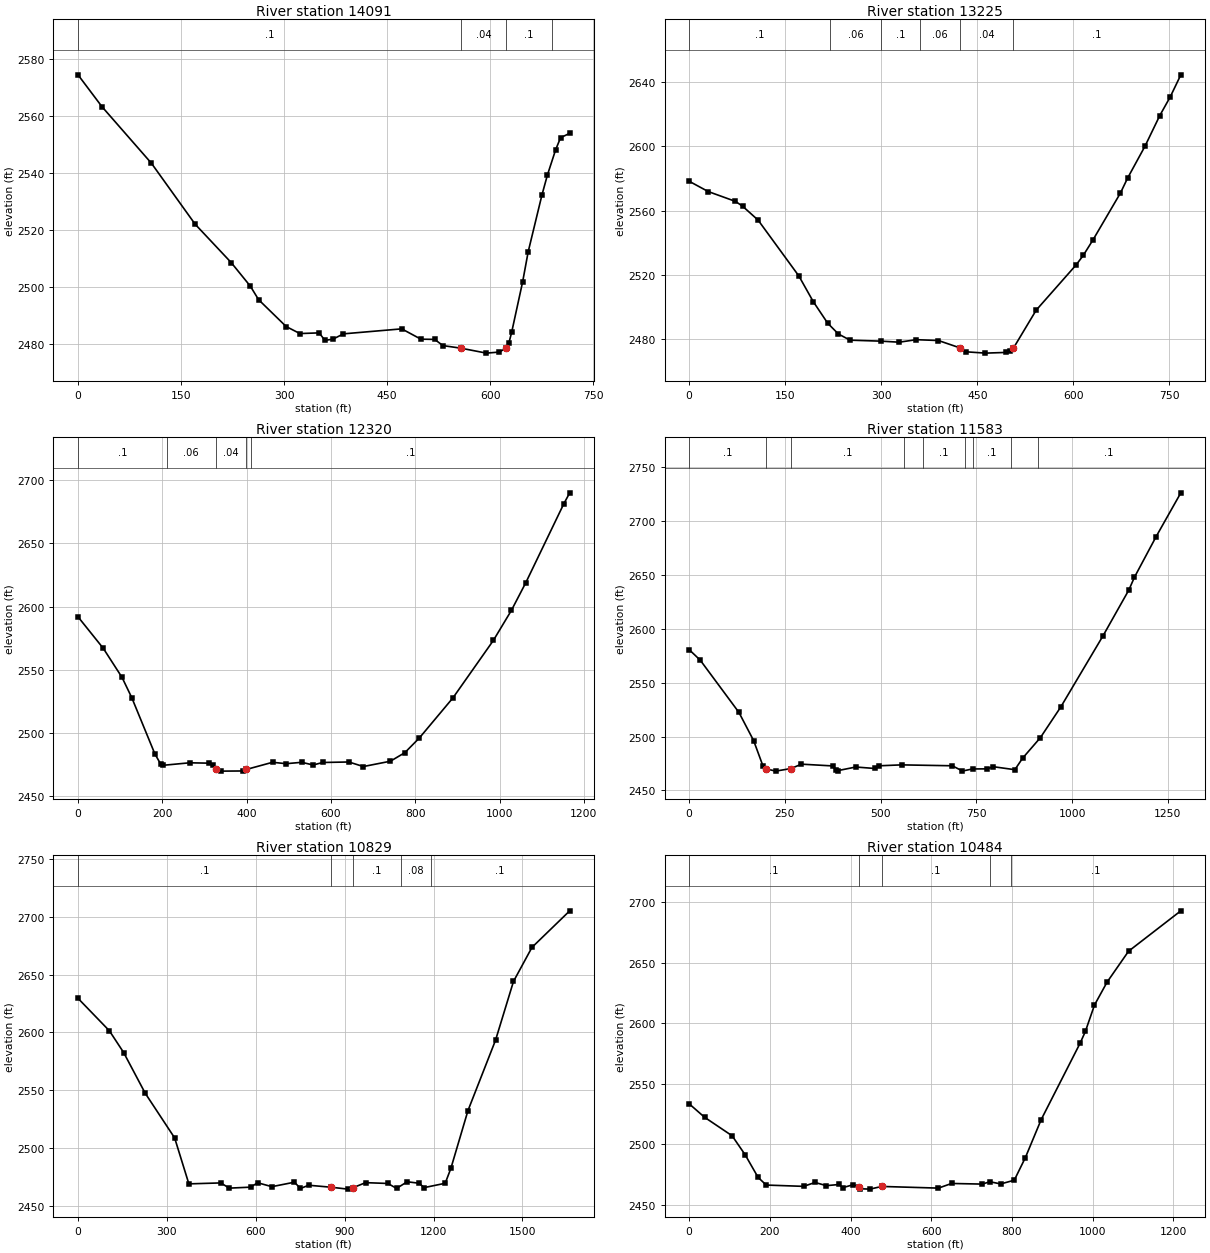
Type RM Length L Ch R = 1 ,14091   ,819.7,865.5,911.3
XS GIS Cut Line= 2
2282526.90833888506838.9624822192281811.72991064506866.516182613
#Sta/Elev= 30
       0 2574.52    34.8 2563.36   106.8  2543.5   170.5 2522.08   222.9 2508.63
   250.9 2500.31   262.9 2495.57     303 2486.15     323 2483.69     351 2483.93
   359.4  2481.3     371 2481.72   386.4 2483.59   471.2 2485.34   499.1 2481.72
   519.1 2481.64   531.1 2479.47   557.82478.535   594.5 2476.82   612.6 2477.18
   623.52478.557   627.2 2480.43   631.2 2484.14   647.2 2501.88   655.2 2512.35
   675.2 2532.27   683.2 2539.32   695.2 2548.21   702.4 2552.46   715.7 2553.98
#Mann= 4 ,-1,0
       0      .1       0   557.8     .04       0   623.5      .1       0
     690     .07       0
Bank Sta=557.8,623.5
XS Rating Curve= 0 ,0
Exp/Cntr(USF)=0,0
Exp/Cntr=0.3,0.1

Type RM Length L Ch R = 1 ,13225   ,920.8,905.5,889.6
XS GIS Cut Line= 2
2282587.52647975506420.1462362262282036.45247186505885.604448576
#Sta/Elev= 30
       0 2578.24    29.9  2571.8    72.4 2565.68    83.7 2562.62   107.7 2554.03
   171.4 2519.21   193.8 2503.29   216.4 2489.82   233.1 2483.11   251.3 2479.28
     300 2478.66   327.9 2478.02   354.7 2479.58   389.2 2479.06   423.6 2474.38
   431.6 2472.05   462.7 2471.21   495.1 2471.65   500.6 2472.24   506.2 2474.23
   541.9 2497.98   604.2 2526.12   615.5 2532.14   630.5 2541.68   673.4 2570.89
   684.5 2580.12   711.7 2600.01   734.7 2619.02   751.3 2630.88   767.7 2644.49
#Mann= 6 ,-1,0
       0      .1       0     220     .06       0     300      .1       0
     360     .06       0   423.6     .04       0   506.2      .1       0
Bank Sta=423.6,506.2
XS Rating Curve= 0 ,0
Exp/Cntr(USF)=0,0
Exp/Cntr=0.3,0.1

Type RM Length L Ch R = 1 ,12320   ,793.7,736.5,676.1
XS GIS Cut Line= 3
2283083.49308684 505527.406343452282548.95129919505229.826379192
2282030.94173178505428.213022031
#Sta/Elev= 30
       0 2591.96      60 2567.04   104.5 2544.07   127.6 2528.04   182.3 2483.69
   196.1 2475.63   200.7  2474.6   264.7 2476.62   310.5 2476.34   319.7 2474.92
   327.6 2471.34   339.3 2470.04   392.3 2470.17   399.3 2471.36   461.6 2477.02
   493.7 2475.92   530.9 2477.01   557.7 2474.88   580.6 2476.87   642.6 2477.26
   676.9 2473.66   741.1 2477.87   775.4 2484.64   810.1 2496.35   889.6 2527.97
   985.3 2573.27  1028.1    2597  1062.4 2618.98  1152.3 2681.14  1166.5 2689.91
#Mann= 5 ,-1,0
       0      .1       0     210     .06       0   327.6     .04       0
   399.3     .06       0     410      .1       0
Bank Sta=327.6,399.3
XS Rating Curve= 0 ,0
Exp/Cntr(USF)=0,0
Exp/Cntr=0.3,0.1

Type RM Length L Ch R = 1 ,11583   ,803.9,754.6,694.5
XS GIS Cut Line= 2
2283028.38568605504529.9623891772281959.30211076 505240.84785935
#Sta/Elev= 30
       0  2580.6    29.1 2570.78     130 2522.39   168.4 2496.28   192.4  2473.1
   200.7 2470.11     226 2467.92   265.9 2470.32   293.3 2474.38   374.7 2472.74
   383.3 2468.75   388.7 2468.42   435.2 2471.73   485.4 2470.36     497 2472.88
   554.8 2473.72   687.2 2472.88   713.8    2468     740 2469.94   778.6 2470.02
   793.2 2472.06   850.5 2469.25   870.9 2479.99   917.1 2498.91   970.6 2527.48
  1081.1  2593.6  1148.3 2635.95  1162.7 2647.62  1219.4 2685.35  1283.9 2725.94
#Mann= 9 ,-1,0
       0      .1       0   200.7     .04       0   265.9      .1       0
     560     .08       0     610      .1       0     720     .08       0
     740      .1       0     840     .08       0     910      .1       0
Bank Sta=200.7,265.9
XS Rating Curve= 0 ,0
Exp/Cntr(USF)=0,0
Exp/Cntr=0.3,0.1

Type RM Length L Ch R = 1 ,10829   ,335.2,344.5,340.4
XS GIS Cut Line= 3
2282270.28373755 503627.260722442282310.22918237504616.735984607
2281789.29081241 505037.18422964
#Sta/Elev= 30
       0 2629.46     106 2601.37     154 2582.62   226.8 2547.43   326.2 2508.76
   374.2 2469.03   482.3 2469.85   510.3 2465.34   582.4 2466.18   606.4 2469.98
   654.5 2466.61   730.5 2470.47   750.9 2465.05   778.6 2467.84   854.6 2466.12
   910.7 2464.48   927.2  2465.6   970.7 2470.08  1046.1 2469.37  1075.2  2465.1
  1111.1 2470.84  1152.3 2469.55  1167.7 2465.75  1239.4 2469.54  1258.5 2482.36
  1316.3 2532.42  1409.3 2593.24  1469.9 2644.09  1532.3 2673.53  1659.7 2705.13
#Mann= 5 ,-1,0
       0      .1       0   854.6     .04       0   927.2      .1       0
 1090.28     .08       0 1190.28      .1       0
Bank Sta=854.6,927.2
XS Rating Curve= 0 ,0
Exp/Cntr(USF)=0,0
Exp/Cntr=0.3,0.1

Type RM Length L Ch R = 1 ,10484   ,600.3,606,607
XS GIS Cut Line= 3
2281997.87729131503907.2487602652282080.53839249504629.155710596
2281755.40472784 504998.37529588
#Sta/Elev= 30
       0 2533.46    38.2 2522.31   106.6 2506.97   138.8 2491.32     171 2472.56
   191.2 2466.24   283.8 2465.17     312 2468.38   340.1 2465.76   372.3 2466.72
   380.4 2464.05     407 2466.57   420.7 2464.97   424.7 2463.19   448.2 2462.88
   477.3  2465.1   617.9 2463.72   650.5 2467.56   726.7 2467.04   745.3    2469
   772.2 2467.16   805.9 2470.28   833.3 2488.93   872.4 2520.27   969.3 2583.75
     982  2593.2  1004.6 2615.05  1035.8 2634.01  1089.1 2659.58  1218.6 2692.96
#Mann= 5 ,-1,0
       0      .1       0   420.7     .04       0   477.3      .1       0
  746.62     .08       0  796.62      .1       0
Bank Sta=420.7,477.3
XS Rating Curve= 0 ,0
Exp/Cntr(USF)=0,0
Exp/Cntr=0.3,0.1

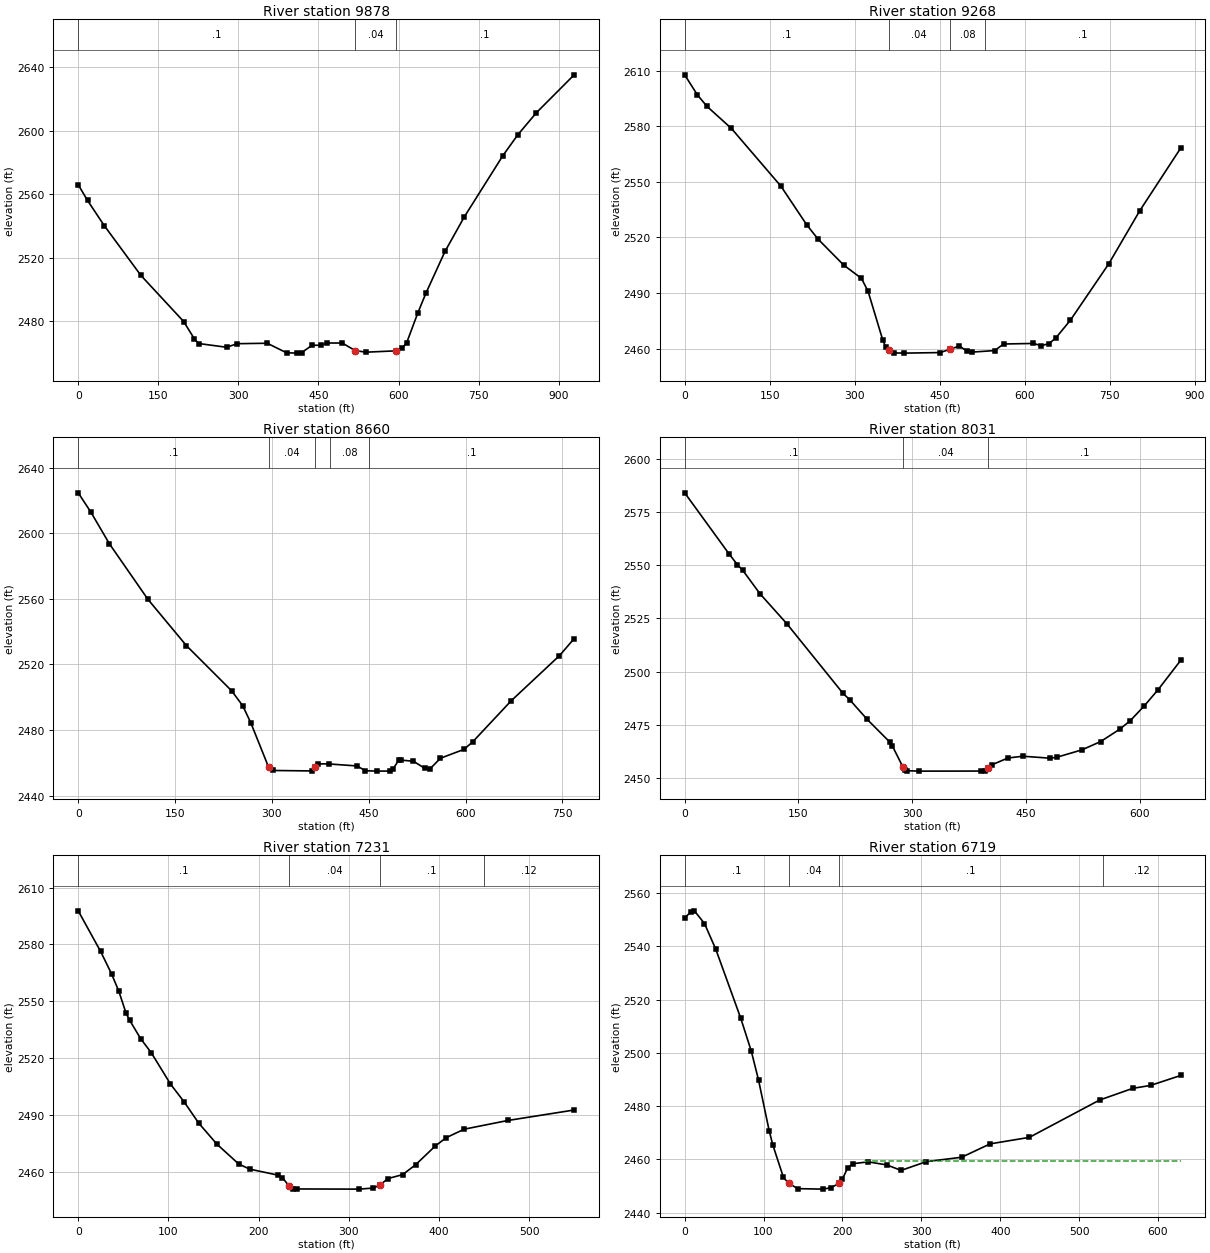
Type RM Length L Ch R = 1 ,9878    ,658.5,610,565.5
XS GIS Cut Line= 2
2281430.27106318503940.3132007392281507.42142429504866.117533987
#Sta/Elev= 30
       0 2566.04    17.4 2556.08      49  2540.1   117.4 2508.78   197.5 2479.68
   217.6 2468.73   225.6 2465.78   277.8 2463.43   297.9 2465.67   354.1 2465.96
   390.2 2459.94   410.1 2459.72   418.3 2460.02   438.4 2464.71   454.3 2464.68
   466.5  2466.1   494.6  2466.1   518.7 2461.36   538.7 2460.31   595.4 2461.17
     607 2463.09     615    2466   636.1 2485.06   651.3 2497.54   687.2 2523.99
   723.4  2545.8   795.6 2584.42   823.7 2597.62   858.4  2611.5     929 2635.36
#Mann= 3 ,-1,0
       0      .1       0   518.7     .04       0   595.4      .1       0
Bank Sta=518.7,595.4
XS Rating Curve= 0 ,0
Exp/Cntr(USF)=0,0
Exp/Cntr=0.3,0.1

Type RM Length L Ch R = 1 ,9268    ,622.3,608,595
XS GIS Cut Line= 2
2280598.14931128504243.4039050762281176.77701956 504899.18197446
#Sta/Elev= 30
       0 2607.86    22.5 2596.99    39.3 2590.84    82.4  2578.9   169.9 2547.65
   215.2 2526.86   235.1 2519.16   280.4  2505.1   311.8  2497.9   323.5 2490.85
   349.1 2464.81   354.4 2460.93   359.8 2459.34   368.3 2457.68   386.5 2457.54
   450.5 2457.84   467.5 2459.58   484.5 2461.38   498.5 2458.48   507.1  2458.1
   546.5 2458.92   562.5 2462.47   614.8 2462.77     629 2461.58   642.5 2462.66
   654.5 2465.73   680.2 2475.31     748 2505.84   802.5 2534.42   874.6 2568.22
#Mann= 4 ,-1,0
       0      .1       0   359.8     .04       0   467.5     .08       0
     530      .1       0
Bank Sta=359.8,467.5
XS Rating Curve= 0 ,0
Exp/Cntr(USF)=0,0
Exp/Cntr=0.3,0.1

Type RM Length L Ch R = 1 ,8660    ,636.9,629.1,622.2
XS GIS Cut Line= 2
 2280201.3760256 504805.499393122280818.57891443505262.890819665
#Sta/Elev= 30
       0 2624.65    19.6  2612.9    48.3 2593.58     108 2559.71   167.6 2531.51
   237.5 2504.03   254.8 2494.88   267.4 2484.41   295.1 2457.22   302.2  2455.4
   361.9 2455.11   366.9 2457.61   371.9 2459.44   387.8 2459.39   431.6 2458.16
     445 2455.25   462.2    2455   483.2 2455.04   487.9 2456.48   496.4 2461.61
   499.3 2461.76   519.3 2461.01   536.9 2456.68   545.1 2456.44   561.1 2462.86
   597.4 2468.24   610.9 2472.78   670.6 2497.85   745.3 2525.34   768.2 2535.77
#Mann= 5 ,-1,0
       0      .1       0   295.1     .04       0   366.9      .1       0
     390     .08       0     450      .1       0
Bank Sta=295.1,366.9
XS Rating Curve= 0 ,0
Exp/Cntr(USF)=0,0
Exp/Cntr=0.3,0.1

Type RM Length L Ch R = 1 ,8031    ,823.7,799.7,770
XS GIS Cut Line= 2
2279865.22088079505389.6378414792280438.33784899505703.750025974
#Sta/Elev= 30
       0  2584.2    58.1  2555.6    69.6 2550.28    76.4 2547.76    99.2 2536.66
   134.4 2522.61   208.6 2489.74   217.8 2486.58   240.5 2477.45     270 2466.87
   273.7 2464.93   287.6 2454.99   290.7 2453.57   293.5 2453.25     309 2453.06
   391.1 2453.09   395.6 2453.25   400.2 2454.68   404.8 2456.03   426.1 2459.26
   445.8 2460.08   482.1 2459.14     491 2459.66   523.4 2463.06   548.3 2467.01
   573.5 2472.85   587.2 2476.82   605.5 2483.73   623.7 2491.34   653.6 2505.21
#Mann= 3 ,-1,0
       0      .1       0   287.6     .04       0   400.2      .1       0
Bank Sta=287.6,400.2
XS Rating Curve= 0 ,0
Exp/Cntr(USF)=0,0
Exp/Cntr=0.3,0.1

Type RM Length L Ch R = 1 ,7231    ,572.8,512.3,436.9
XS GIS Cut Line= 2
 2279523.5549959506221.7595933872280069.11826371506287.888474333
#Sta/Elev= 30
       0 2597.72    24.8 2576.35    36.9 2564.59    44.9 2555.52      53 2543.88
      57  2540.1    69.1  2530.5    81.2 2522.84   102.2 2506.56   117.5 2497.05
   133.6 2485.91   153.7 2474.88   177.9 2464.42     190 2461.73   221.5 2458.56
   226.3 2457.21   233.6 2452.91   238.4 2451.39   242.4 2451.29   310.9  2451.2
   326.9 2451.75   334.2 2453.23   343.1 2456.74   359.4 2458.82   373.8 2463.98
   395.5 2473.82   407.6 2478.24   427.7 2482.75   476.1 2487.34   549.6 2492.86
#Mann= 4 ,-1,0
       0      .1       0   233.6     .04       0   334.2      .1       0
     450     .12       0
Bank Sta=233.6,334.2
XS Rating Curve= 0 ,0
Exp/Cntr(USF)=0,0
Exp/Cntr=0.3,0.1

Type RM Length L Ch R = 1 ,6719    ,426.6,390.5,345.1
XS GIS Cut Line= 2
2279821.13496016506872.0269226922280113.20418434506315.442174727
#Sta/Elev= 30
       0  2550.6     7.7 2552.94    12.3 2553.33    25.1 2548.57    39.4 2538.93
      71 2513.07    84.4  2500.7    93.6 2489.84   107.1 2470.81   111.6 2465.57
   125.2 2453.25   131.8 2451.09   143.3 2449.06   174.9 2448.88   185.1 2449.37
   195.9 2451.07   199.9 2452.61   206.5 2456.81   213.1 2458.42   232.5 2459.11
   256.2 2457.97   274.3 2455.91   306.5 2459.21     351 2460.84   387.2 2465.87
   436.9 2468.31   525.8  2482.3   567.9  2486.7   590.5  2487.8   628.6 2491.53
#Mann= 4 ,-1,0
       0      .1       0   131.8     .04       0   195.9      .1       0
     530     .12       0
#XS Ineff= 2 , 0
                          229.12         2459.38
Permanent Ineff=
       F       F
Bank Sta=131.8,195.9
XS Rating Curve= 0 ,0
Exp/Cntr(USF)=0,0
Exp/Cntr=0.3,0.1

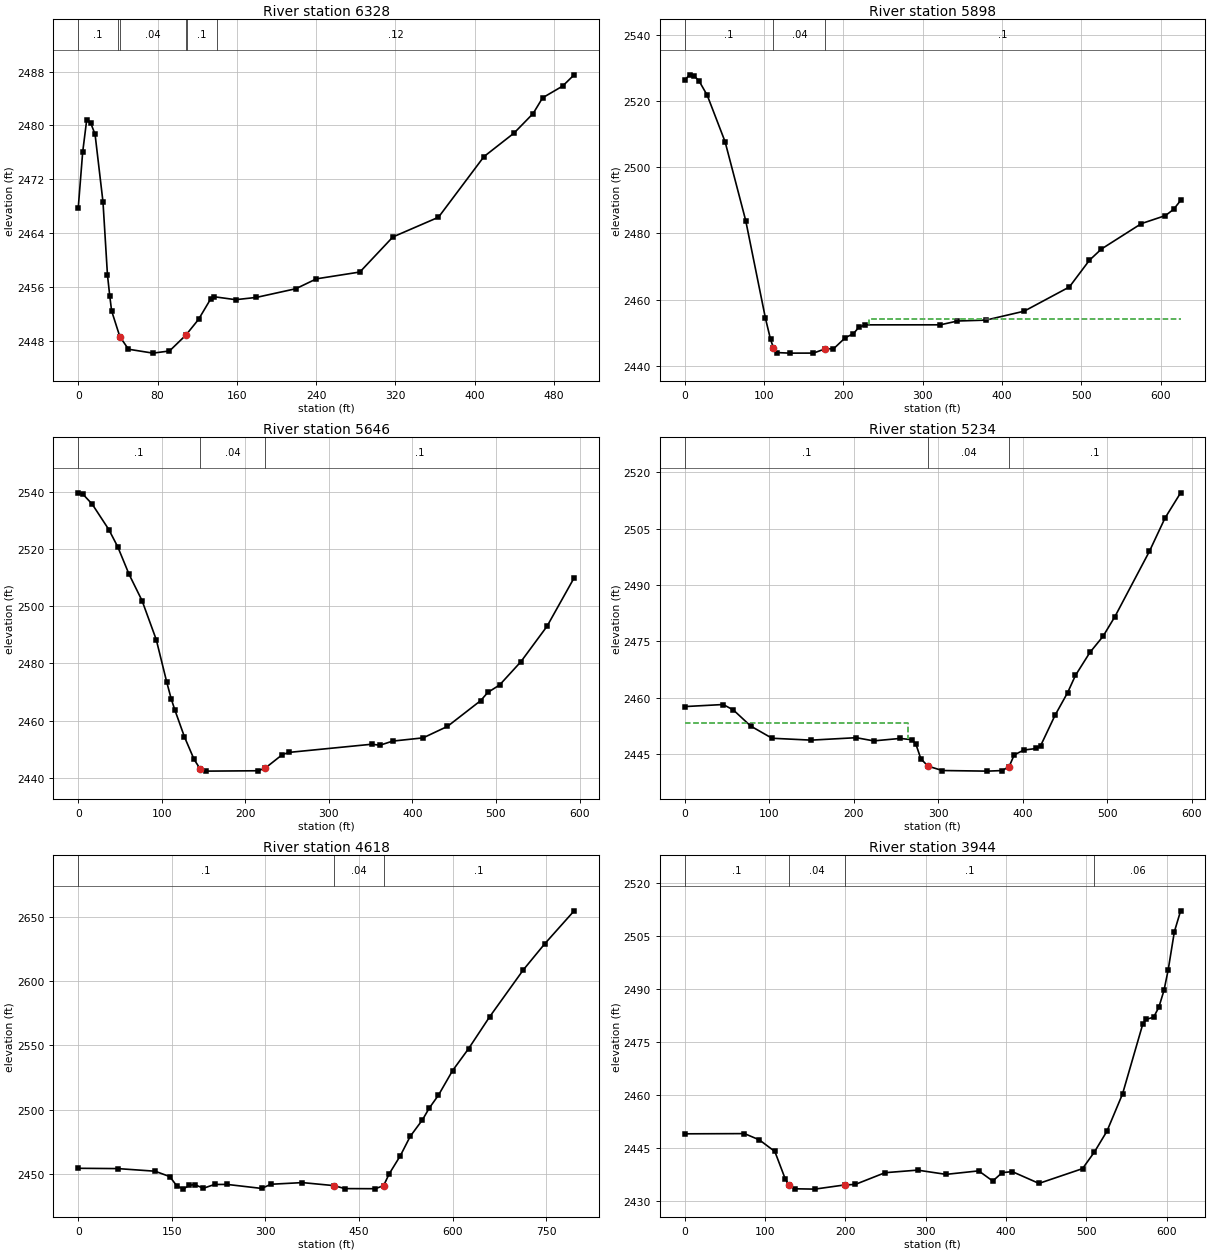
Type RM Length L Ch R = 1 ,6328    ,463.1,430,397
XS GIS Cut Line= 2
2280295.05860694 506833.451742142280151.77936489506354.017355279
#Sta/Elev= 30
       0 2467.68     4.5 2476.03     8.6 2480.86    12.8 2480.29      17 2478.68
      25 2468.63    29.5 2457.81    31.8  2454.7    33.7 2452.45      42 2448.62
    50.7 2446.75    75.4 2446.17    92.1 2446.49   108.6 2448.84   121.4 2451.18
   133.9 2454.28   137.5 2454.54   158.9 2454.11   179.8 2454.45   219.6 2455.74
   240.4 2457.21   284.2 2458.22   317.5 2463.43   363.5 2466.36   409.4 2475.37
   439.7 2478.86     459 2481.77   468.6 2484.11   488.7 2485.84   500.4 2487.52
#Mann= 6 ,-1,0
       0      .1       0      40     .12       0      42     .04       0
   108.6     .12       0     110      .1       0     140     .12       0
Bank Sta=42,108.6
XS Rating Curve= 0 ,0
Exp/Cntr(USF)=0,0
Exp/Cntr=0.3,0.1

Type RM Length L Ch R = 1 ,5898    ,247.8,252.4,255.9
XS GIS Cut Line= 2
2280768.98225372506668.1295397742280273.01564662506287.888474333
#Sta/Elev= 30
       0 2526.25     6.1 2527.86    11.4 2527.65      18 2526.06    28.4  2521.7
    50.9 2507.69    76.9  2483.9   101.8  2454.4   108.2 2448.04   111.9  2445.5
   116.9 2444.06   132.1  2443.9   162.3 2443.91   177.4 2445.23   187.5 2445.18
   202.4 2448.55   212.7 2449.77   219.5 2451.71   227.8 2452.43   322.2 2452.44
   343.8 2453.59   379.6 2453.86   427.8 2456.55   484.8 2463.86   510.1 2471.93
   525.2 2475.31   575.6 2482.98   605.9  2485.4   616.1 2487.27     625 2489.95
#Mann= 3 ,-1,0
       0      .1       0   111.9     .04       0   177.4      .1       0
#XS Ineff= 2 , 0
                          232.83          2454.1
Permanent Ineff=
       F       F
Bank Sta=111.9,177.4
XS Rating Curve= 0 ,0
Exp/Cntr(USF)=0,0
Exp/Cntr=0.3,0.1

Type RM Length L Ch R = 1 ,5646    ,402.6,412.4,422.7
XS GIS Cut Line= 2
2280939.81519617 506497.296597332280493.44524978506106.034051731
#Sta/Elev= 30
       0 2539.69     5.5 2539.25    16.8  2535.7    36.6 2526.85    47.4 2520.74
    60.9 2511.15    76.4 2501.96    93.4 2488.32   105.9 2473.51   111.2  2467.7
   115.5 2463.83   127.2 2454.25   138.7 2446.38   145.8 2443.15   152.9 2442.29
   215.3 2442.42   223.8 2443.33   244.2 2448.04   252.1 2448.84   351.3  2451.7
   361.2 2451.36   376.4  2452.8   412.8 2453.93     442 2457.95   481.7 2466.96
   490.2 2469.82   504.4 2472.45   529.9  2480.6   561.1 2492.97   593.6 2509.95
#Mann= 3 ,-1,0
       0      .1       0   145.8     .04       0   223.8      .1       0
Bank Sta=145.8,223.8
XS Rating Curve= 0 ,0
Exp/Cntr(USF)=0,0
Exp/Cntr=0.3,0.1

Type RM Length L Ch R = 1 ,5234    ,518.7,616,702.9
XS GIS Cut Line= 3
2281188.64573669506356.8397170252281126.73150182506132.667487333
2280896.15435128505863.660811702
#Sta/Elev= 30
       0 2457.67    45.6 2458.22    57.7 2456.75    78.1  2452.5   103.4 2449.25
   149.7 2448.75     203  2449.4   223.7 2448.55   254.9  2449.2   268.8 2448.87
   273.4 2447.83   279.5 2443.78   287.9 2441.84   304.9 2440.67   358.3 2440.51
   375.9 2440.66     384 2441.74     390 2444.83   401.4 2446.12   416.3 2446.53
   421.2 2447.25   438.3 2455.36   453.2 2461.39   462.4 2465.94   479.5 2472.05
     495 2476.32   509.2 2481.61     550 2498.96   568.4 2507.78   586.9  2514.5
#Mann= 3 ,-1,0
       0      .1       0   287.9     .04       0     384      .1       0
#XS Ineff= 2 , 0
           264.1 2453.27
Permanent Ineff=
       F       F
Bank Sta=287.9,384
XS Rating Curve= 0 ,0
Exp/Cntr(USF)=0,0
Exp/Cntr=0.3,0.1

Type RM Length L Ch R = 1 ,4618    ,599.8,673.5,734.2
XS GIS Cut Line= 2
2281257.52435173506389.8546923692281791.12541001505801.099147791
#Sta/Elev= 30
       0 2454.28    63.5 2454.04   123.1 2452.01   146.7 2447.81   157.5 2440.87
   168.3 2438.06   177.9 2441.03   186.4 2441.61   200.6 2438.75   218.4 2441.69
   238.4 2441.73     294  2438.6   308.6 2441.85   359.2 2443.14   410.1 2440.77
   427.1 2438.47     476 2438.38   489.4 2440.79   497.9 2449.67   516.2 2464.13
   531.9  2479.1   551.5 2491.96   562.3 2501.03   577.2 2511.21   599.9 2530.39
   625.4 2547.36   659.1 2572.13   713.1 2608.71   747.1 2628.81   794.6 2654.69
#Mann= 3 ,-1,0
       0      .1       0   410.1     .04       0   489.4      .1       0
Bank Sta=410.1,489.4
XS Rating Curve= 0 ,0
Exp/Cntr(USF)=0,0
Exp/Cntr=0.3,0.1

Type RM Length L Ch R = 1 ,3944    ,0.5,0.7,1
XS GIS Cut Line= 2
2281252.70683581506565.6157530462281845.51175183506737.497586443
#Sta/Elev= 30
       0 2448.98    74.4 2449.04    92.8 2447.28   112.2 2443.98   125.1 2436.24
   129.9 2434.46   136.9 2433.42   161.9 2433.32   199.2 2434.51   212.3 2434.65
   249.3 2437.97   289.8  2438.7   325.3  2437.5   365.9 2438.49   383.4 2435.61
   395.1 2437.99   407.6 2438.28   440.9 2434.94   495.1 2439.12     510 2443.86
   525.5 2449.72   544.9 2460.26     570 2479.97   574.2 2481.39   583.6 2481.99
   590.1 2484.82   596.5 2489.59   601.7 2495.36   609.4 2506.18   617.2 2512.12
#Mann= 4 ,-1,0
       0      .1       0   129.9     .04       0   199.2      .1       0
     510     .06       0
Bank Sta=129.9,199.2
XS Rating Curve= 0 ,0
Exp/Cntr=0.3,0.1

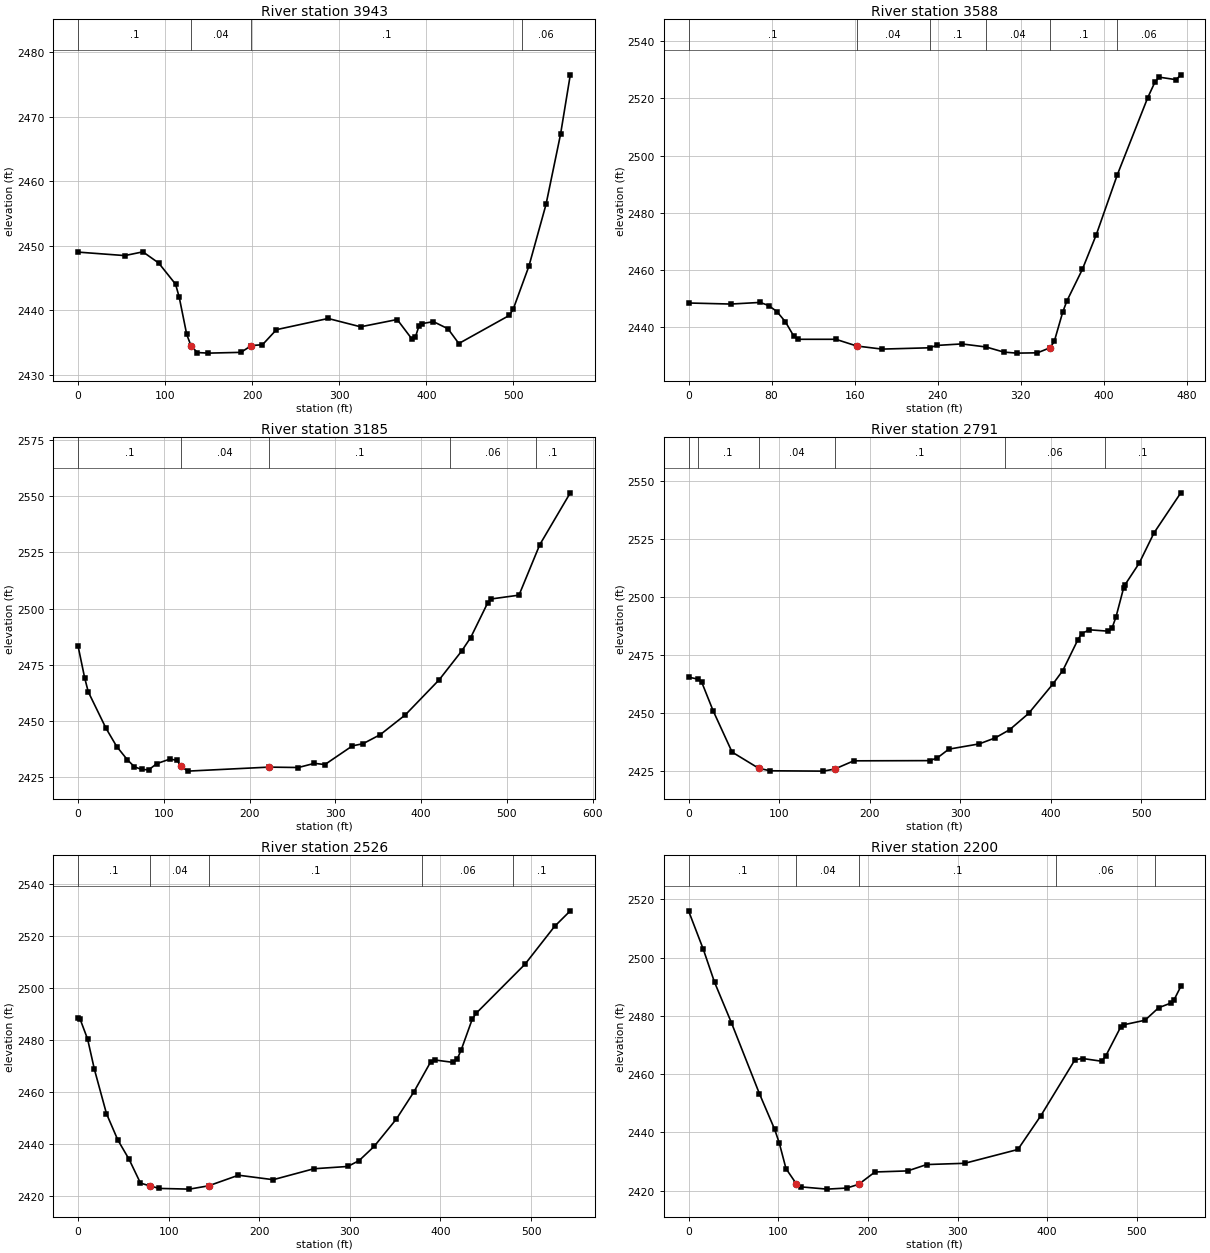
Type RM Length L Ch R = 1 ,3943    ,187.2,355.1,404.4
XS GIS Cut Line= 2
2281252.70683581506565.6157530462281794.91633305506725.354685936
#Sta/Elev= 30
       0 2448.98    53.7 2448.44    74.5 2449.02    92.6 2447.29     112 2444.01
   116.2 2441.99   124.8 2436.23   129.82434.433   137.1 2433.41   149.6 2433.32
   187.1 2433.44   199.12434.497   211.8 2434.62   227.9 2436.96   287.2 2438.69
   324.5  2437.4   366.5 2438.53   383.1 2435.57   387.3 2435.76   391.4 2437.48
   394.8 2437.89   408.1  2438.2   424.8  2437.1   437.3 2434.81   495.3 2439.17
   499.8 2440.15   517.8 2446.81   537.4 2456.36   554.1 2467.24   565.3 2476.46
#Mann= 4 ,-1,0
       0      .1       0   129.8     .04       0   199.1      .1       0
     510     .06       0
Bank Sta=129.8,199.1
XS Rating Curve= 0 ,0
Exp/Cntr(USF)=0,0
Exp/Cntr=0.3,0.1

Type RM Length L Ch R = 1 ,3588    ,348,402.9,419.7
XS GIS Cut Line= 2
2281214.97494005  506605.00339792281288.19077051507073.584712822
#Sta/Elev= 30
       0 2448.44    40.7 2448.07      69 2448.64    77.1 2447.56    85.1 2445.46
    93.3 2441.88   101.4 2436.84   105.4 2435.74   141.9 2435.74   162.1 2433.39
   186.4 2432.31   232.3 2432.77     239 2433.59   263.3 2434.12   286.7 2433.05
   303.8 2431.26   316.3  2430.9   336.2 2431.01   348.4 2432.79   352.4 2435.01
   360.5 2445.22   364.5 2449.13   379.4 2460.17   392.9 2472.37   413.1 2493.26
   442.4 2520.25   449.6  2525.9   453.6 2527.45   469.8 2526.57   474.3 2528.27
#Mann= 6 ,-1,0
       0      .1       0   162.1     .04       0   232.3      .1       0
   286.7     .04       0   348.4      .1       0   413.1     .06       0
Bank Sta=162.1,348.4
XS Rating Curve= 0 ,0
Exp/Cntr(USF)=0,0
Exp/Cntr=0.3,0.1

Type RM Length L Ch R = 1 ,3185    ,416.5,393.9,351.6
XS GIS Cut Line= 4
2280866.79463861506681.7222719312280895.70542892 506786.24589843
2280860.12291777506937.4715708122280904.60105671507244.370729469
#Sta/Elev= 30
       0 2483.39     7.7 2469.25    11.9 2462.99    32.6 2446.77    45.1 2438.65
    57.5 2432.76    65.7 2429.64    74.1 2428.44    82.4 2428.27    91.7 2431.01
   107.3 2433.08   115.6 2432.46   119.7 2429.98   127.9  2427.7   222.4 2429.48
   256.9 2429.31   275.6 2431.16   287.8 2430.62   319.9 2438.94   332.2 2439.89
   352.4 2443.94   381.6 2452.73   421.1 2468.35   447.2 2481.09   457.8 2487.12
   477.7 2502.62   481.8 2504.28   514.1 2505.97   538.3  2528.4   573.9 2551.48
#Mann= 5 ,-1,0
       0      .1       0   119.7     .04       0   222.4      .1       0
   433.8     .06       0   533.8      .1       0
Bank Sta=119.7,222.4
XS Rating Curve= 0 ,0
Exp/Cntr(USF)=0,0
Exp/Cntr=0.3,0.1

Type RM Length L Ch R = 1 ,2791    ,264.2,265.3,267.8
XS GIS Cut Line= 2
 2280460.3808093506767.3228611942280625.70301167507285.332428607
#Sta/Elev= 30
       0  2465.4    10.3 2464.55    14.5 2463.28    27.1 2450.93    48.1 2433.01
    77.5 2426.01    90.1 2424.93   148.9 2424.78   161.5 2425.68   182.5 2429.23
   266.5 2429.32   274.9 2430.52   287.5 2434.27   321.1 2436.55   338.7 2439.13
   354.7 2442.67   375.6 2449.69   402.4 2462.38   413.4 2468.23   430.2 2481.63
   434.4 2484.24   442.8 2485.86   463.8 2485.26     468 2486.78   472.2 2491.41
   480.6 2503.92   481.9 2505.16   497.9 2514.69   514.2 2527.74   543.8 2545.06
#Mann= 6 ,-1,0
       0     .12       0      10      .1       0    77.5     .04       0
   161.5      .1       0     350     .06       0     460      .1       0
Bank Sta=77.5,161.5
XS Rating Curve= 0 ,0
Exp/Cntr(USF)=0,0
Exp/Cntr=0.3,0.1

Type RM Length L Ch R = 1 ,2526    ,328.2,325.8,321
XS GIS Cut Line= 2
2280208.04840806506838.9485589982280357.55003187507361.233452575
#Sta/Elev= 30
       0 2488.51     2.3 2487.94    10.6 2480.25    18.1 2468.63    31.4 2451.67
    43.9 2441.57    56.4 2434.11    68.9 2425.02    79.5 2423.92    89.7 2422.97
     123  2422.7   144.2 2423.98   177.1 2428.04   215.4 2426.32   260.3 2430.52
   297.7  2431.4   310.2 2433.65   326.9 2439.13   351.3 2449.58   370.7 2460.03
   389.3 2471.61   393.6 2472.28   414.2 2471.34   418.4 2472.59   422.8 2476.04
     435 2487.85   439.2 2490.13   493.3 2509.02   525.9 2523.52   543.3 2529.52
#Mann= 5 ,-1,0
       0      .1       0    79.5     .04       0   144.2      .1       0
     380     .06       0     480      .1       0
Bank Sta=79.5,144.2
XS Rating Curve= 0 ,0
Exp/Cntr(USF)=0,0
Exp/Cntr=0.3,0.1

Type RM Length L Ch R = 1 ,2200    ,374.8,375.4,377.8
XS GIS Cut Line= 2
2279881.75310102506910.6021032442280063.60752363507428.611670657
#Sta/Elev= 30
       0 2516.03    16.5  2502.8      29 2491.53    47.9 2477.58      79 2453.34
      96  2441.1   101.2 2436.38   108.7 2427.58     120 2422.48   125.7 2421.32
   154.5 2420.56   176.4 2420.93   189.7  2422.2   207.9 2426.44   244.4 2426.81
   265.6 2428.99     308 2429.42   367.3 2434.16     393 2445.79   430.9 2464.91
   439.4 2465.37   460.6 2464.44   465.2 2466.18   481.8 2476.08     486 2476.98
   509.1  2478.5   524.2 2482.77   538.6 2484.47   541.1 2485.27     549 2490.09
#Mann= 5 ,-1,0
       0      .1       0     120     .04       0   189.7      .1       0
     410     .06       0     520      .1       0
Bank Sta=120,189.7
XS Rating Curve= 0 ,0
Exp/Cntr(USF)=0,0
Exp/Cntr=0.3,0.1