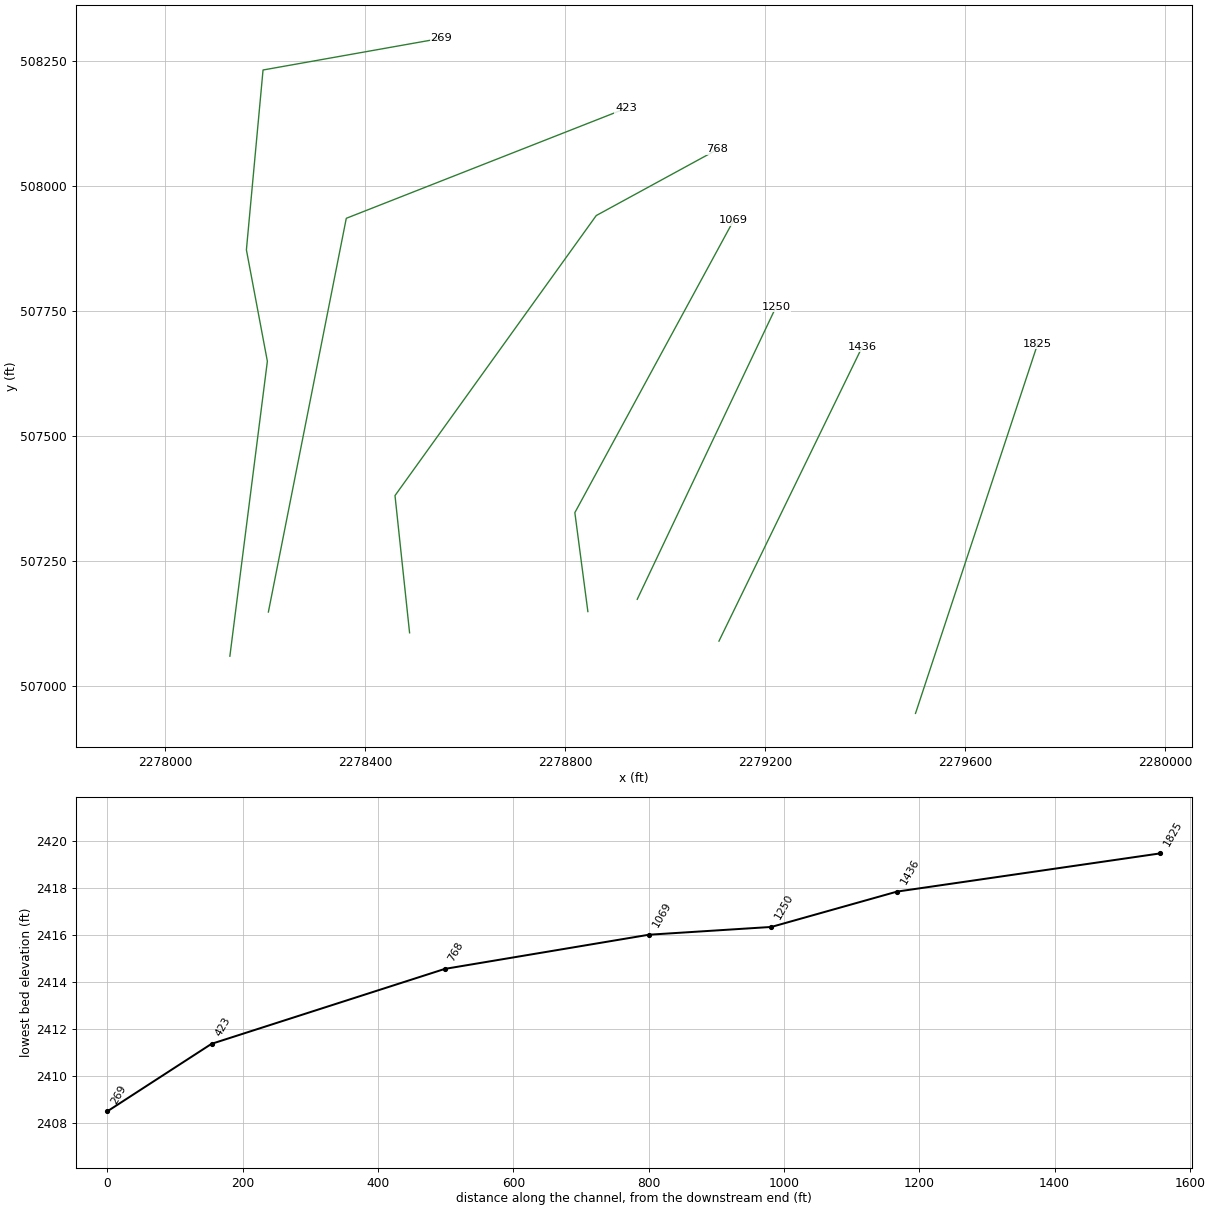
HEC-RAS study DEERCK.prj: DEERCK

--- DEERCK.g01 (geometry) --- (continued)

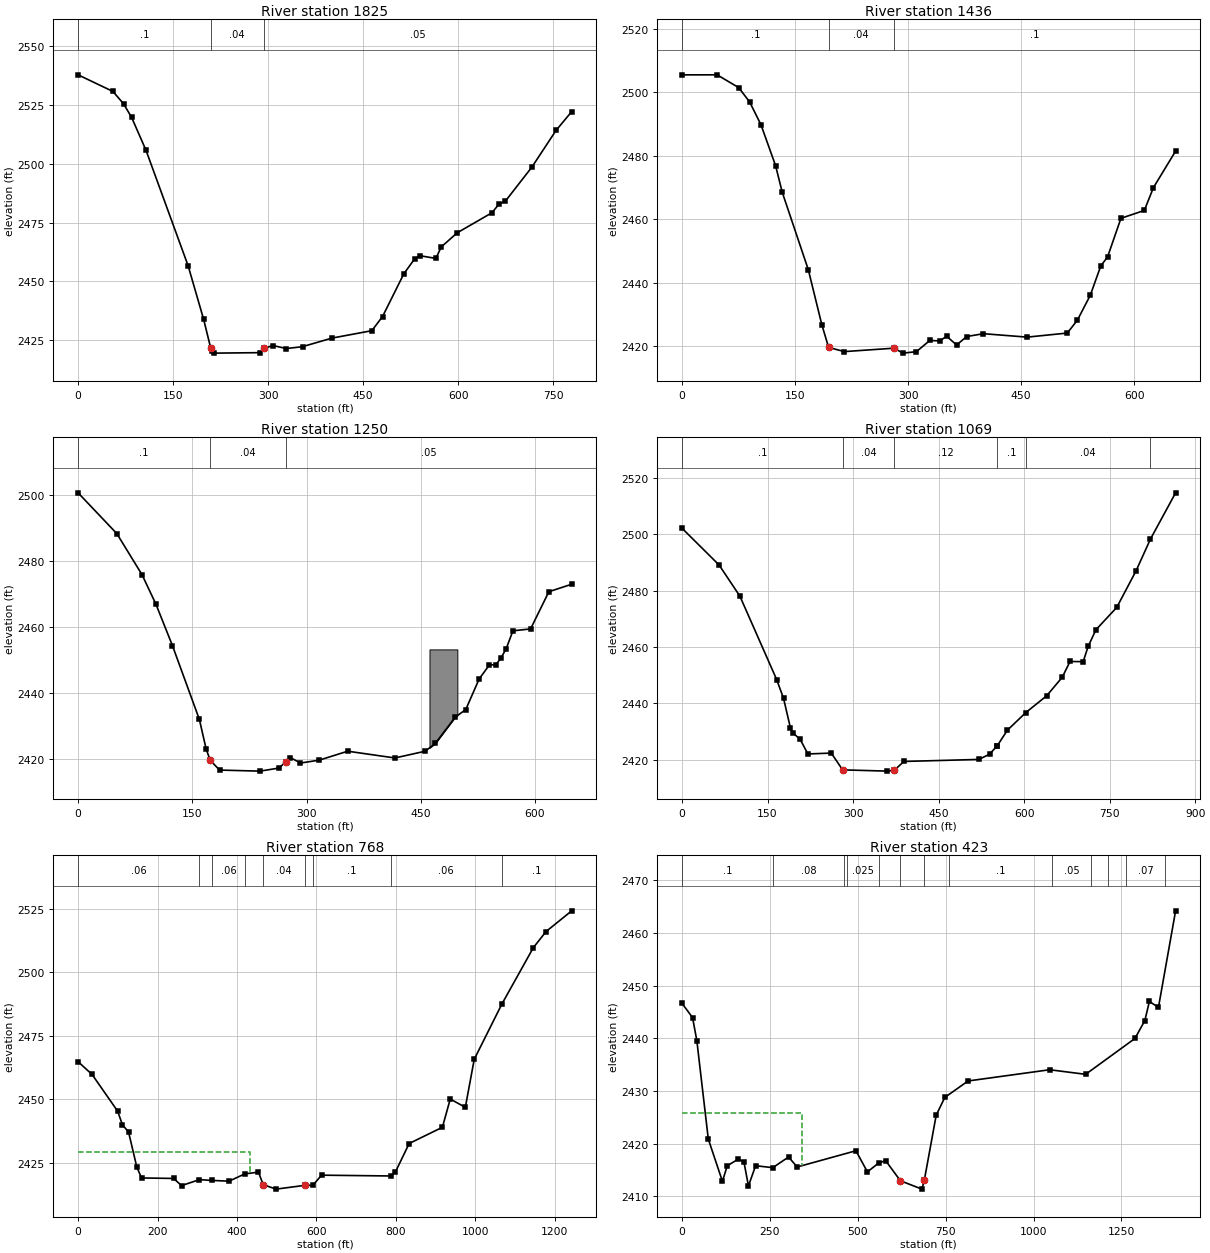
Type RM Length L Ch R = 1 ,1825    ,393.6,388.8,372.4
XS GIS Cut Line= 2
2279501.00409491506944.9598291172279745.43251092507684.677403879
#Sta/Elev= 30
       0 2537.91      55 2530.83    71.8 2525.57    84.5 2519.77   107.2 2505.78
   173.7 2456.61   198.2 2433.78   209.3 2421.64   210.9  2420.2   215.1 2419.46
   286.7 2419.66   293.1  2421.5   307.8 2422.68   328.8 2421.41   354.2 2422.21
   400.4 2425.84   463.6 2429.01   480.5 2435.01   514.2 2453.26     531 2459.49
   539.5 2460.92   564.7 2459.78   573.2 2464.66   598.4 2470.68   653.2  2479.2
   664.5 2482.94   674.3  2484.1   716.4 2498.69   754.3 2514.22   779.1 2522.26
#Mann= 3 ,-1,0
       0      .1       0   209.3     .04       0   293.1     .05       0
Bank Sta=209.3,293.1
XS Rating Curve= 0 ,0
Exp/Cntr(USF)=0,0
Exp/Cntr=0.3,0.1

Type RM Length L Ch R = 1 ,1436    ,186.1,185.8,187
Node Name=A
XS GIS Cut Line= 2
2279107.78803828 507089.586168172279394.34819441507678.337034415
#Sta/Elev= 30
       0 2505.48    46.6 2505.49    75.2 2501.47    89.8 2496.92   104.7  2489.8
   124.1 2476.92     133 2468.49   167.6 2444.08   185.5 2426.78   194.5 2419.64
   215.4 2418.32   281.12419.395   293.2 2417.84     311  2418.3   328.7 2421.83
   342.1 2421.68     351 2423.17   364.3  2420.4   377.7 2423.07   399.9 2423.96
   457.9 2422.88   511.1 2424.16   524.5 2428.21   541.6 2436.06   555.6 2445.33
   564.5 2448.11   582.3  2460.3   613.3 2462.78   625.4 2469.98   654.8 2481.47
#Mann= 3 ,-1,0
       0      .1       0   194.5     .04       0   281.1      .1       0
Bank Sta=194.5,281.1
XS Rating Curve= 0 ,0
Exp/Cntr(USF)=0,0
Exp/Cntr=0.5,0.3

Type RM Length L Ch R = 1 ,1250    ,184.4,180.9,174.1
XS GIS Cut Line= 2
2278944.30663655507173.2932335832279222.32624475507758.955139793
#Sta/Elev= 30
       0 2500.74    50.9 2488.36    83.9 2475.94   102.3 2466.93   123.9 2454.41
   159.3    2432   168.1 2423.13   173.42419.665   185.8 2416.66     239 2416.34
     264 2417.28   272.92419.243   278.8 2420.44   292.1 2418.79   316.8 2419.68
   354.1 2422.38   416.1 2420.33   455.9 2422.38   469.2 2424.75   495.2 2432.69
   509.1 2434.99   526.8 2444.32   540.1 2448.51   548.9 2448.65   555.3 2450.63
   562.2 2453.43   571.1 2458.89   594.3 2459.47   618.3 2470.75   648.3 2473.02
#Mann= 3 ,-1,0
       0      .1       0   173.4     .04       0   272.9     .05       0
#Block Obstruct= 1 ,-1
   461.5  498.13 2453.26
Bank Sta=173.4,272.9
XS Rating Curve= 0 ,0
Exp/Cntr(USF)=0,0
Exp/Cntr=0.3,0.1

Type RM Length L Ch R = 1 ,1069    ,321.1,301.7,284.6
XS GIS Cut Line= 3
2278845.54207721507148.6349276172278819.49115392507346.621944584
  2279137.312418507931.899354391
#Sta/Elev= 30
       0 2502.16    65.1  2489.1   101.5 2478.08     166  2448.5   178.1 2441.81
   190.2  2431.3   194.2 2429.62   207.2 2427.29   220.8  2422.1   261.8 2422.41
   281.7 2416.46   360.4 2416.01   372.52416.342   389.2 2419.44   520.7 2420.16
   539.4 2422.01   553.1 2425.06   553.1 2425.07   570.8 2430.55   602.8 2436.74
   639.6 2442.74   666.9  2449.3   680.5  2454.9   703.6 2454.83   712.3 2460.24
     726 2466.15   762.5 2474.08   796.3 2487.03   821.4 2498.23   865.7 2514.71
#Mann= 6 ,-1,0
       0      .1       0   281.7     .04       0   372.5     .12       0
   553.1      .1       0   602.8     .04       0   821.4      .1       0
Bank Sta=281.7,372.5
XS Rating Curve= 0 ,0
Exp/Cntr(USF)=0,0
Exp/Cntr=0.3,0.1

Type RM Length L Ch R = 1 ,768     ,261,344.9,373.5
XS GIS Cut Line= 4
 2278488.8540301507106.2079715322278459.69844578507380.765709191
2278862.26618644507941.1104979912279104.73874991508073.368259884
#Sta/Elev= 30
       0 2464.76    35.2 2459.73    99.5 2445.28   111.6 2439.91     127 2437.06
   147.8 2423.22   159.7 2418.96   240.3 2418.77   260.4 2415.95   305.4  2418.3
   336.9 2417.99   379.9 2417.69   419.4 2420.56   453.9 2421.25   465.9 2416.32
   498.2 2414.56   571.7 2416.07   590.7 2416.05   612.8 2420.06   786.9 2419.74
   798.4 2421.24   833.2 2432.53   916.9 2438.93   936.6 2450.05   974.6 2446.79
     997 2465.71  1066.4 2487.43  1145.9 2509.73  1177.8 2516.04  1242.3  2524.2
#Mann= 9 ,-1,0
       0     .06       0   305.4      .1       0   336.9     .06       0
   419.4      .1       0   465.9     .04       0   571.7    .055       0
   590.7      .1       0   786.9     .06       0  1066.4      .1       0
#XS Ineff= 2 , 0
          432.21 2429.17
Permanent Ineff=
       F       F
Bank Sta=465.9,571.7
XS Rating Curve= 0 ,0
Exp/Cntr(USF)=0,0
Exp/Cntr=0.3,0.1

Type RM Length L Ch R = 1 ,423     ,95.4,153.8,173.2
XS GIS Cut Line= 3
2278206.37768261507147.7986995772278362.23075658507935.603963924
  2278921.593844508155.506246384
#Sta/Elev= 30
       0 2446.63      30 2443.93    42.2 2439.57    74.8 2420.88     115 2412.86
   128.7  2415.8   160.4 2417.09   176.3 2416.51     189 2411.98   209.4 2415.82
   258.3 2415.45   303.1 2417.47   327.6 2415.58   494.8 2418.66   527.4 2414.65
     560 2416.37  579.49 2416.77   621.2 2412.97   682.4 2411.38   689.4 2413.11
   723.1 2425.41   747.6 2428.78   813.8  2431.9  1045.9 2434.03  1148.2 2433.16
  1288.4 2439.96  1316.6 2443.36  1329.5 2446.98  1355.3 2445.86  1404.1 2464.18
#Mann= 13 ,-1,0
       0      .1       0     260     .08       0     460     .12       0
     470    .025       0     560      .1       0   621.2     .04       0
   689.4     .08       0     760      .1       0 1053.07     .05       0
 1163.07      .1       0 1213.07     .06       0 1263.07     .07       0
 1373.07      .1       0
#XS Ineff= 2 , 0
          341.48 2425.83
Permanent Ineff=
       F       F
Bank Sta=621.2,689.4
XS Rating Curve= 0 ,0
Exp/Cntr(USF)=0,0
Exp/Cntr=0.3,0.1

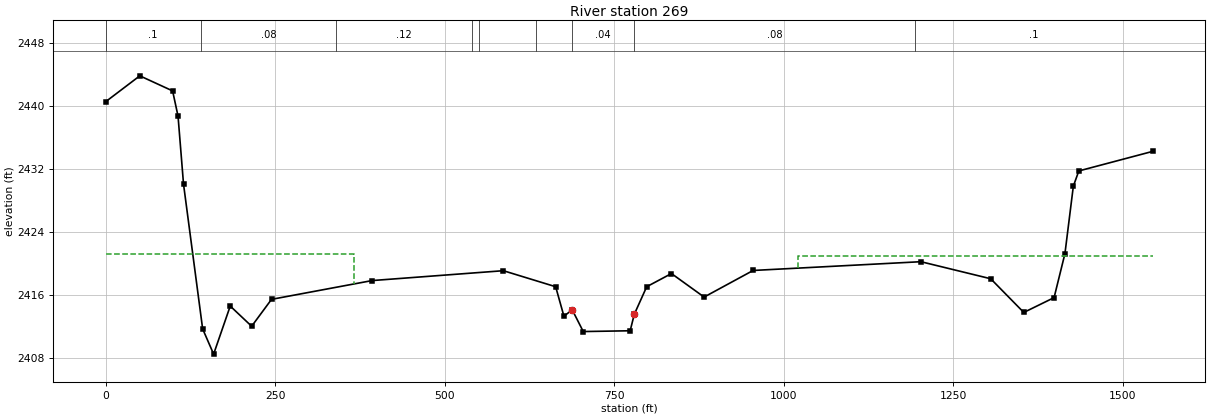
Type RM Length L Ch R = 1 ,269     ,,,
XS GIS Cut Line= 5
2278129.33775595507059.3920853732278204.35314343 507649.53354135
2278162.40219642507872.4797833542278195.70281453508232.365296564
2278551.89118563508295.731880039
#Sta/Elev= 30
       0 2440.51    50.2 2443.78    98.6 2441.87   106.6 2438.67   114.7 2430.05
   142.9 2411.72   159.1 2408.52   183.6 2414.61   215.2 2412.05   244.5 2415.46
   392.9 2417.84   586.5 2419.09   663.7 2417.06   675.9 2413.32   688.1 2414.14
   704.4 2411.38   773.6 2411.48   779.7 2413.57     798 2417.06   834.5 2418.73
   882.7 2415.75     955 2419.12  1202.5 2420.23  1305.5 2418.07  1354.3  2413.8
    1399 2415.68    1415 2421.25  1427.4  2429.8  1435.5 2431.73    1545 2434.22
#Mann= 9 ,-1,0
       0      .1       0     140     .08       0     340     .12       0
     540    .025       0     550     .12       0  634.89    .025       0
   688.1     .04       0   779.7     .08       0 1193.17      .1       0
#XS Ineff= 2 , 0
          366.27 2421.17 1021.69            2421
Permanent Ineff=
       F       F
Bank Sta=688.1,779.7
XS Rating Curve= 0 ,0
Exp/Cntr(USF)=0,0
Exp/Cntr=0.3,0.1
LCMann Table=0

Chan Stop Cuts=-1
Use User Specified Reach Order=0
Composite Channel Slope=5